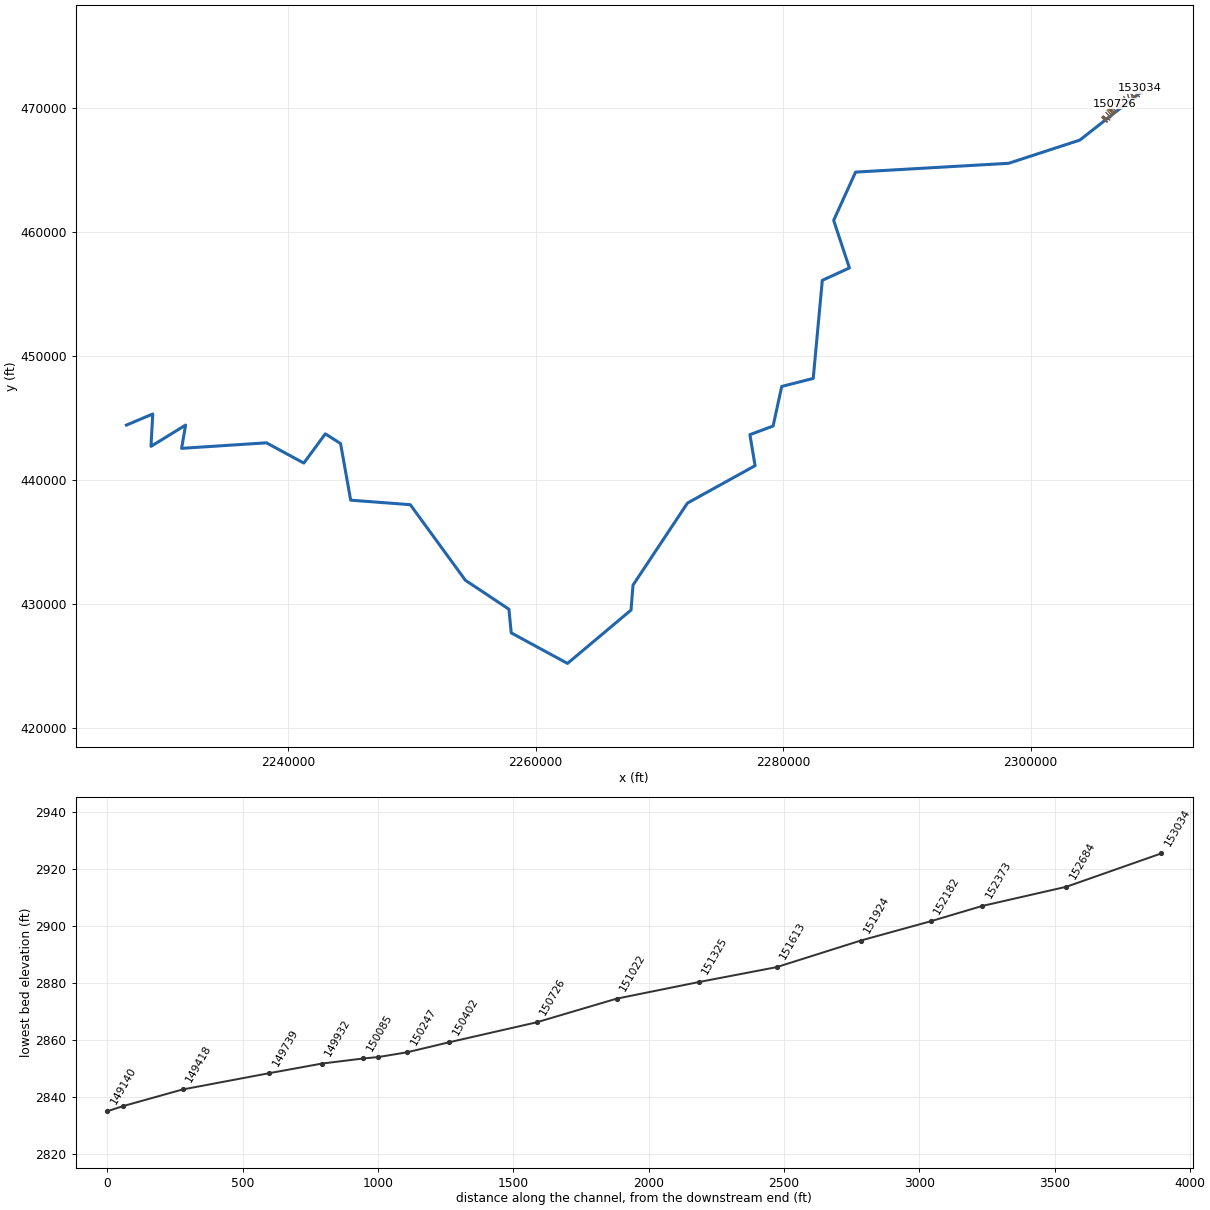
--- KNAPPCK.prj (project) ---

Proj Title=KNAPPCK
Current Plan=p01
Default Exp/Contr=0,0
English Units
Geom File=g01
Flow File=f01
Plan File=p01
Background Map Layer=Inundation Boundary (01pct Value_0)
Background Map Layer=FWY
Background Map Layer=Inundation Boundary (01pct Value_0)
Background Map Layer=Inundation Boundary (01pct Value_0)
Y Axis Title=Elevation
X Axis Title(PF)=Main Channel Distance
X Axis Title(XS)=Station
BEGIN DESCRIPTION:
Stream Name: Knapp Creek
Flood Zone: Detailed Zone AE from confluence with Greenbrier River to XS 130898, Approximate Zone A elsewhere
Pocahontas County, WV
HEC-RAS Version: RAS 6.1
Vertical Datum: NAVD88
Projection: NAD 1983 StatePlane West Virginia S FIPS 4702 (US Feet)
Terrain: 1-meter LIDAR (FEMA Region III 3DEP collected 2016-2018)
Land Use: 2019 NLCD
Hydrologic Method:
WV SIR2010-5033 regression equations weighted with gage 03182000 (Knapp Creek at Marlington, WV)
Model Notes:
Coincident peak at confluence with Douthat Creek.
END DESCRIPTION:
DSS File=dss
DSS Export Rating Curves= 0
DSS Export Rating Curve Sorted= 0
DSS Export Volume Flow Curves= 0
DXF OffsetX= 0
DXF OffsetY= 0
DXF ScaleX= 0
DXF ScaleY= 0

--- KNAPPCK.p01 (plan) ---

Plan Title=Floodplain
Program Version=6.10
Short Identifier=Floodplain
Geom File=g01
Flow File=f01
Subcritical Flow
K Sum by GR= 0
Std Step Tol= 0.01
Critical Tol= 0.01
Num of Std Step Trials= 20
Max Error Tol= 0.3
Flow Tol Ratio= 0.001
Split Flow NTrial= 30
Split Flow Tol= 0.02
Split Flow Ratio= 0.02
Log Output Level= 0
Friction Slope Method= 1
Unsteady Friction Slope Method= 2
Unsteady Bridges Friction Slope Method= 1
Parabolic Critical Depth
Global Vel Dist= 0 , 0 , 0
Global Log Level= 0
CheckData=True
Encroach Param=-1 ,0,0, 2
Encroach River=KNAPPCK
Encroach Reach=Main
Encroach Node=131423
       1   320.2  551.08
Encroach Node=131037
       1  418.39  475.04
Encroach Node=130824
       1  439.77  477.61
Encroach Node=130502
       1  511.55  595.24
Encroach Node=130248
       1  513.07   614.6
Encroach Node=129973
       1   605.4     678
Encroach Node=129804
       1  643.37     727
Encroach Node=129344
       1   322.5  499.53
Encroach Node=128979
       1  226.92   410.7
Encroach Node=128885
       1   234.6   442.1
Encroach Node=128359
       1     280  489.89
Encroach Node=128018
       1   298.5     535
Encroach Node=127909
       1  290.52  490.55
Encroach Node=127623
       1  339.76  541.25
Encroach Node=127302
       1   321.8   543.7
Encroach Node=126957
       1  433.37  568.91
Encroach Node=126537
       1  381.56  578.69
Encroach Node=126069
       1   591.5  631.79
Encroach Node=125865
       1     598     666
Encroach Node=125784
       1     625     682
Encroach Node=125515
       1   555.1   711.3
Encroach Node=124820
       1  832.01   923.9
Encroach Node=124313
       1   778.2   831.4
Encroach Node=123813
       1  728.75   882.4
Encroach Node=123292
       1  706.36  911.04
Encroach Node=123114
       1  764.32  958.54
Encroach Node=122836
       1  796.33   980.4
Encroach Node=122324
       1  967.64  1069.5
Encroach Node=122168
       1    1129  1248.5
Encroach Node=121807
       1 1071.75  1261.8
Encroach Node=121417
       1   989.4  1107.2
Encroach Node=121191
       1  930.04    1050
Encroach Node=120843
       1  1193.3  1248.6
Encroach Node=120500
       1 1166.91 1254.22
Encroach Node=120366
       1  987.55  1083.8
Encroach Node=120039
       1  665.55  803.66
Encroach Node=119702
       1   417.2   634.2
Encroach Node=119234
       1  401.01  689.55
Encroach Node=118844
       1  372.46  598.02
Encroach Node=118541
       1     435  641.95
Encroach Node=118167
       1   545.4   750.7
Encroach Node=117722
       1   296.5  595.63
Encroach Node=117386
       1   247.2  393.42
Encroach Node=117100
       1   146.2  387.91
Encroach Node=116037
       1  469.78  775.09
Encroach Node=115767
       1  427.65     758
Encroach Node=115028
       1   509.4  802.19
Encroach Node=114527
       1   221.5     362
Encroach Node=114348
       1  216.96  509.92
Encroach Node=113771
       1   250.4   811.2
Encroach Node=112849
       1  512.08   775.7
Encroach Node=112358
       1  480.16  657.08
Encroach Node=111885
       1  643.97   857.9
Encroach Node=111205
       1  834.71 1034.46
Encroach Node=111019
       1     926    1005
Encroach Node=110935
       1   945.5  1019.6
Encroach Node=110735
       1     779   870.5
Encroach Node=110251
       1   484.6   556.8
Encroach Node=109796
       1     660     826
Encroach Node=109585
       1   638.6   822.8
Encroach Node=109452
       1   663.1   842.3
Encroach Node=109264
       1   574.8  664.32
Encroach Node=109083
       1   784.8  898.61
Encroach Node=108888
       1  713.37   895.6
Encroach Node=108738
       1   840.9  1033.7
Encroach Node=108391
       1  730.86  1109.8
Encroach Node=108073
       1  828.16 1148.83
Encroach Node=107662
       1  939.82 1245.29
Encroach Node=107054
       1 1195.16  1384.2
Encroach Node=106598
       1   820.4  1233.2
Encroach Node=106455
       1  897.41  1274.2
Encroach Node=105846
       1  656.63 1117.78
Encroach Node=105433
       1     705 1084.04
Encroach Node=104846
       1  646.18 1089.37
Encroach Node=103937
       1     730  1172.5
Encroach Node=103386
       1   618.2 1017.33
Encroach Node=102732
       1   333.1  687.68
Encroach Node=102095
       1   311.7  604.22
Encroach Node=101584
       1   233.2  415.78
Encroach Node=101341
       1  251.22  609.48
Encroach Node=101180
       1  212.05  644.65
Encroach Node=100667
       1   285.6  712.48
Encroach Node=99710
       1   439.4   842.8
Encroach Node=99157
       1  333.74  568.43
Encroach Node=99075
       1  365.67  612.52
Encroach Node=99019
       1  425.59  672.45
Encroach Node=98875
       1  434.03  653.46
Encroach Node=98757
       1   559.9  784.29
Encroach Node=98600
       1   673.4  895.67
Encroach Node=98326
       1  640.48     758
Encroach Node=98087
       1   938.8    1013
Encroach Node=98011
       1   926.8    1015
Encroach Node=97952
       1   914.2    1015
Encroach Node=97815
       1 1000.88  1128.1
Encroach Node=97691
       1 1124.19    1277
Encroach Node=97235
       1 1078.68 1390.42
Encroach Node=96527
       1  1186.8  1295.3
Encroach Node=96219
       1  901.87 1171.71
Encroach Node=95649
       1   494.1  893.99
Encroach Node=95292
       1  407.93  807.26
Encroach Node=95030
       1   376.5   714.8
Encroach Node=94484
       1     450  806.16
Encroach Node=93966
       1   411.9  652.79
Encroach Node=93302
       1  295.83  603.73
Encroach Node=92826
       1  360.04  558.43
Encroach Node=92329
       1   189.7  628.92
Encroach Node=91582
       1  459.68   767.2
Encroach Node=91046
       1   561.3 1077.85
Encroach Node=90556
       1  504.58   985.3
Encroach Node=90063
       1  548.27 1006.07
Encroach Node=88878
       1     975  1150.5
Encroach Node=88560
       1  914.51 1088.69
Encroach Node=88178
       1  588.36  869.35
Encroach Node=87757
       1  443.69  664.07
Encroach Node=87201
       1   565.6  653.58
Encroach Node=86580
       1  1178.9  1511.6
Encroach Node=85792
       1 1362.17  1575.7
Encroach Node=84629
       1     887 1151.71
Encroach Node=83903
       1 1249.48  1526.8
Encroach Node=83171
       1 1207.43  1521.6
Encroach Node=82380
       1   889.4 1388.31
Encroach Node=81752
       1  1028.2 1306.06
Encroach Node=81030
       1   707.4  935.35
Encroach Node=80123
       1  1233.2 1426.07
Encroach Node=79650
       1   637.6 1085.48
Encroach Node=78754
       1   507.9  858.09
Encroach Node=78060
       1   826.4 1100.77
Encroach Node=77819
       1   531.3  685.63
Encroach Node=77326
       1   871.2 1042.34
Encroach Node=76774
       1  810.64    1211
Encroach Node=76427
       1   628.1  880.64
Encroach Node=76011
       1  1135.4 1494.47
Encroach Node=75502
       1 1210.58    1608
Encroach Node=75205
       1 1041.75  1280.6
Encroach Node=74763
       1 1178.26 1453.99
Encroach Node=74199
       1  906.24 1255.61
Encroach Node=73662
       1     455 1021.68
Encroach Node=73412
       1     827 1463.56
Encroach Node=73015
       1  953.36 1577.85
Encroach Node=72405
       1 1073.04 1600.13
Encroach Node=71974
       1  1208.8 1550.17
Encroach Node=71524
       1  863.93 1245.81
Encroach Node=70782
       1    1181 1697.57
Encroach Node=69967
       1  978.41  1558.3
Encroach Node=69501
       1 1084.66 1588.24
Encroach Node=68972
       1  775.45  1340.4
Encroach Node=68433
       1 1037.33 1700.92
Encroach Node=67598
       1   349.5  963.48
Encroach Node=67039
       1 1019.55 1659.61
Encroach Node=65560
       1 1632.55 1995.17
Encroach Node=65130
       1  741.92  1315.7
Encroach Node=64702
       1 1389.03 1962.63
Encroach Node=63545
       1   976.3 1775.62
Encroach Node=62565
       1  1126.5 1757.98
Encroach Node=61889
       1  815.88 1475.98
Encroach Node=61438
       1  870.91 1471.98
Encroach Node=60854
       1     682 1121.28
Encroach Node=60512
       1  409.85   801.6
Encroach Node=60103
       1  381.15   901.8
Encroach Node=59853
       1   396.9  933.25
Encroach Node=59511
       1   541.7 1102.96
Encroach Node=58942
       1   394.9  1287.9
Encroach Node=58445
       1   308.9  1267.9
Encroach Node=57598
       1   351.7 1266.52
Encroach Node=56823
       1  157.03  819.59
Encroach Node=56462
       1  387.25  780.89
Encroach Node=56211
       1  514.16   907.8
Encroach Node=55921
       1  446.07   558.3
Encroach Node=55688
       1   517.7  687.02
Encroach Node=55369
       1  355.47   489.4
Encroach Node=55078
       1   334.5   409.5
Encroach Node=54703
       1  536.43   633.7
Encroach Node=54328
       1  188.57     338
Encroach Node=53963
       1   182.6  329.03
Encroach Node=53426
       1   329.7     429
Encroach Node=52916
       1   487.9  760.79
Encroach Node=52046
       1   384.9  729.28
Encroach Node=51700
       1  427.93  640.29
Encroach Node=51256
       1  562.04  695.25
Encroach Node=50816
       1  384.17  571.46
Encroach Node=50403
       1  467.65   624.3
Encroach Node=49980
       1  246.98  491.39
Encroach Node=49521
       1     367   469.8
Encroach Node=48975
       1   417.8  584.68
Encroach Node=48647
       1   500.8  692.78
Encroach Node=48204
       1   335.4   442.6
Encroach Node=47706
       1     376   461.8
Encroach Node=47212
       1   452.8   540.8
Encroach Node=46740
       1     394     495
Encroach Node=46183
       1   276.7  413.39
Encroach Node=45788
       1  496.29     742
Encroach Node=45596
       1  453.52     712
Encroach Node=45154
       1   602.7   684.8
Encroach Node=44955
       1   683.1   766.1
Encroach Node=44420
       1     972    1084
Encroach Node=43978
       1 1115.27    1282
Encroach Node=43616
       1    1035 1377.63
Encroach Node=43136
       1 1027.38  1509.1
Encroach Node=42683
       1  987.15  1618.9
Encroach Node=41995
       1 1066.59  1739.4
Encroach Node=41412
       1  1021.9 1840.74
Encroach Node=40161
       1   916.4 1617.47
Encroach Node=39561
       1 1242.03 2083.83
Encroach Node=39138
       1  1383.4 2151.38
Encroach Node=38854
       1  971.57 1963.58
Encroach Node=37760
       1  844.87  1620.1
Encroach Node=37238
       1   792.1  1433.7
Encroach Node=36800
       1  693.66  1294.7
Encroach Node=35906
       1    1385 1591.95
Encroach Node=35739
       1    1435    1668
Encroach Node=34458
       1  395.77 1172.26
Encroach Node=34063
       1   368.1   997.6
Encroach Node=33708
       1  274.04  978.27
Encroach Node=33075
       1   394.9  928.58
Encroach Node=32726
       1   379.3     864
Encroach Node=32311
       1  406.51   926.3
Encroach Node=31717
       1   179.4  537.37
Encroach Node=31479
       1     205  546.03
Encroach Node=31126
       1   274.4  510.65
Encroach Node=30875
       1     270  416.61
Encroach Node=30596
       1   258.6     413
Encroach Node=30034
       1   269.9   718.5
Encroach Node=29551
       1     282  718.18
Encroach Node=29006
       1   186.5  800.28
Encroach Node=28529
       1   222.1   824.5
Encroach Node=28107
       1   274.3   803.3
Encroach Node=27830
       1  187.03  827.31
Encroach Node=27446
       1  155.65  699.99
Encroach Node=27168
       1   122.6  466.28
Encroach Node=26746
       1   213.7  454.55
Encroach Node=26294
       1   296.9  505.18
Encroach Node=25891
       1   380.6  552.39
Encroach Node=25398
       1  351.48   573.3
Encroach Node=24907
       1  399.01  579.36
Encroach Node=24406
       1   251.8  421.45
Encroach Node=23908
       1  331.92  491.52
Encroach Node=23547
       1     275  416.71
Encroach Node=23190
       1   298.1  499.98
Encroach Node=22762
       1   150.7   367.4
Encroach Node=22438
       1     185  391.27
Encroach Node=22194
       1   191.7  380.93
Encroach Node=21603
       1   202.7  349.25
Encroach Node=21048
       1  284.84  451.18
Encroach Node=20556
       1  370.66     550
Encroach Node=20017
       1  363.95   502.4
Encroach Node=19562
       1  332.42   474.3
Encroach Node=19079
       1   284.5   451.8
Encroach Node=18596
       1   198.3   396.5
Encroach Node=18185
       1   180.6   414.2
Encroach Node=17853
       1   214.5   460.7
Encroach Node=17720
       1   202.2   476.9
Encroach Node=17356
       1   206.7  426.38
Encroach Node=16894
       1   205.7  377.03
Encroach Node=16588
       1  361.98  493.28
Encroach Node=16248
       1  382.74   507.2
Encroach Node=15874
       1  368.06     538
Encroach Node=15264
       1   315.8  513.13
Encroach Node=14416
       1     304  485.61
Encroach Node=13776
       1   298.6  556.85
Encroach Node=13119
       1   281.3  675.43
Encroach Node=12003
       1   198.3   760.4
Encroach Node=11087
       1   162.9  559.02
Encroach Node=10589
       1    96.5  345.04
Encroach Node=10056
       1  455.84  589.53
Encroach Node=9410
       1  377.46   478.1
Encroach Node=8901
       1   493.2   659.8
Encroach Node=8320
       1  334.68  872.13
Encroach Node=7865
       1  337.25   942.3
Encroach Node=7454
       1     342   743.6
Encroach Node=6763
       1   452.6  629.35
Encroach Node=5308
       1   211.3  836.75
Encroach Node=4427
       1  272.21  525.04
Encroach Node=3969
       1   527.2  779.28
Encroach Node=3346
       1  829.94  985.54
Encroach Node=3050
       1   849.4    1152
Encroach Node=2664
       1  897.22  1288.9
Encroach Node=2062
       1   742.9 1108.91
Encroach Node=1913
       1     660     930
Encroach Node=1824
       1     620     840
Encroach Node=1579
       1   569.9  832.77
Encroach Node=1315
       1 1267.48    1545
Encroach Node=1111
       1    1175    1489
Encroach Node=735
       1 1099.51 1322.01
Encroach Node=135
       1   967.4 1384.25
Computation Interval=0.1SEC
Output Interval=1SEC
Instantaneous Interval=Max Profile
Mapping Interval=1HOUR
Computation Time Step Use Courant=        0
Computation Time Step Use Time Series=    0
Computation Time Step Count To Double=0
Computation Time Step Max Doubling=0
Computation Time Step Max Halving=0
Computation Time Step Residence Courant=0
Run HTab= 0
Run UNet= 0
Run Sediment= 0
Run PostProcess= 0
Run WQNet= 0
Run RASMapper=-1
UNET Theta= 0
UNET Theta Warmup= 0
UNET ZTol= 0
UNET ZSATol= 0
UNET MxIter= 0
UNET Max Iter WO Improvement= 0
UNET MaxInSteps= 0
UNET DtIC= 0
UNET DtMin= 0
UNET MaxCRTS= 0
UNET WFStab= 0
UNET SFStab= 0
UNET WFX= 1
UNET SFX= 1
UNET Gravity=32.174
UNET 1D Methodology=Finite Difference
UNET DSS MLevel= 1
UNET Pardiso=0
UNET DZMax Abort= 0
UNET Use Existing IB Tables= 0
UNET Froude Reduction=False
UNET Froude Limit= 0
UNET Froude Power= 0
UNET D1 Cores= 0
UNET WindReference=Eulerian
UNET WindDragFormulation=Hsu (1988)
UNET D2 Coriolis=0
UNET D2 Cores= 0
UNET D2 Theta= 1
UNET D2 Theta Warmup= 1
UNET D2 Z Tol= 0.01
UNET D2 Volume Tol= 0.01
UNET D2 Max Iterations= 20
UNET D2 Equation= 0
UNET D2 RampUpFraction=0.1
UNET D2 TimeSlices= 1
UNET D2 Turbulence Formulation=Non-Conservative (original)
UNET D2 Eddy Viscosity=0.3
UNET D2 Transverse Eddy Viscosity=0.1
UNET D2 Smagorinsky Mixing=0
UNET D2 BCVolumeCheck=0
UNET D2 Cores=0
UNET D2 SolverType=PARDISO (Direct)
UNET D2 Minimum Iterations= 2147483647
UNET D2 Maximum Iterations= 2147483647
UNET D2 Restart Number= 10
UNET D2 Relaxation Coeff=1.3
UNET D2 SOR Precondition Iterations= 10
UNET D2 ILUT Maximum Fill= 8
UNET D2 ILUT Tolerance=1E-08
UNET D1D2 MaxIter= 0
UNET D1D2 ZTol=0.01
UNET D1D2 QTol=0.1
UNET D1D2 MinQTol=1
DSS File=dss
Write IC File= 0
Write IC File at Fixed DateTime=0
Write IC File at Sim End=0
Echo Input=False
Echo Parameters=False
Echo Output=False
Write Detailed= 0
HDF Write Warmup=0
HDF Write Time Slices=0
HDF Flush=0
HDF Compression= 1
HDF Chunk Size= 1
HDF Spatial Parts= 1
HDF Use Max Rows=0
HDF Fixed Rows= 1
Calibration Method= 0
Calibration Iterations= 20
Calibration Max Change=0.05
Calibration Tolerance=0.2
Calibration Maximum=1.5
Calibration Minimum=0.5
Calibration Optimization Method= 1
WQ AD Non Conservative
WQ ULTIMATE=-1
WQ Max Comp Step=1HOUR
WQ Output Interval=15MIN
WQ Output Selected Increments= 0
WQ Output face flow=0
WQ Output face velocity=0
WQ Output face area=0
WQ Output face dispersion=0
WQ Output cell volume=0
WQ Output cell surface area=0
WQ Output cell continuity=0
WQ Output cumulative cell continuity=0
WQ Output face conc=0
WQ Output face dconc_dx=0
WQ Output face courant=0
WQ Output face peclet=0
WQ Output face adv mass=0
WQ Output face disp mass=0
WQ Output cell mass=0
WQ Output cell source sink temp=0
WQ Output nsm pathways=0
WQ Output nsm derived pathways=0
WQ Create Restart=0
WQ Fixed Restart=0
WQ System Summary=0
WQ Write To DSS=0
Sorting and Armoring Iterations= 10
XS Update Threshold= 0.02
Bed Roughness Predictor= 0
Hydraulics Update Threshold= 0.02
Energy Slope Method= 1
Volume Change Method= 1
Sediment Retention Method= 0
Sediment TS Multiplier= 1
Warm Up Method= 0
XS Weighting Method= 0
Number of US Weighted Cross Sections= 1
Number of DS Weighted Cross Sections= 1
Upstream XS Weight=0
Main XS Weight=1
Downstream XS Weight=0
Number of DS XS's Weighted with US Boundary= 1
Upstream Boundary Weight= 1
Weight of XSs Associated with US Boundary= 0
Number of US XS's Weighted with DS Boundary= 1
Downstream Boundary Weight= 0.5
Weight of XSs Associated with DS Boundary= 0.5
Percentile Method= 0
Sediment Output Level= 3
Mass or Volume Output= 0
Output Increment Type= 1
Profile and TS Output Increment= 1
Transport Output Increment 1
XS Output Flag= 0
XS Output Increment= 10
Read HDF5 Sediment Hotstart= 0
Sediment Hotstart Type= 0
Write Gradation File= 0
Read Gradation Hotstart= 0
Write HDF5 File= 1
Write Binary Output= 1
Write DSS Sediment File= 0
DSS Sediment Output Type= 1
SV Curve= 0
Specific Gage Flag= 0
Subcell Erosion Methods= 0
Subcell Deposition Methods= 0
Advection Scheme= 1
Matrix Solver= 0
Implicit Weighting Factor= 1
Maximum Outer Loop Convergence Iterations= 5
Convergence Maximum Absolute= 0.001
Convergence RMSE= 0.0001
Grain Fractions Max Abs Error= 0.001
Max Subgrid Regions= 1
Max Subgrid Length Scale= 3.402823E+38
Initial Layer Thickness= 3.402823E+38
Min Layer Thickness= 3.402823E+38
Max Layer Thickness= 3.402823E+38
Number of Layers= 5

--- KNAPPCK.f01 (steady flow) ---

Flow Title=Flow
Program Version=6.10
Number of Profiles= 7
Profile Names=01pct,FWY,10pct,04pct,02pct,0_2pct,01plus
River Rch & RM=KNAPPCK,Main            ,153034
     620     620     328     436     525     864     916
River Rch & RM=KNAPPCK,Main            ,150726
     882     882     474     625     750    1220    1300
River Rch & RM=KNAPPCK,Main            ,147783
     992     992     536     705     844    1370    1470
River Rch & RM=KNAPPCK,Main            ,141873
    1120    1120     606     796     952    1540    1650
River Rch & RM=KNAPPCK,Main            ,138464
    1690    1690     929    1210    1440    2310    2490
River Rch & RM=KNAPPCK,Main            ,134610
    1900    1900    1050    1360    1620    2590    2800
River Rch & RM=KNAPPCK,Main            ,124820
    2880    2880    1620    2090    2470    3900    4260
River Rch & RM=KNAPPCK,Main            ,124313
    3200    3200    1810    2330    2750    4320    4730
River Rch & RM=KNAPPCK,Main            ,111205
    3820    3820    2170    2790    3290    5150    5650
River Rch & RM=KNAPPCK,Main            ,108391
    4330    4330    2480    3170    3730    5830    6410
River Rch & RM=KNAPPCK,Main            ,107054
    4840    4840    2780    3550    4170    6490    7160
River Rch & RM=KNAPPCK,Main            ,95030
    5380    5380    3100    3950    4640    7200    7950
River Rch & RM=KNAPPCK,Main            ,84629
    5980    5980    3460    4400    5170    7990    8840
River Rch & RM=KNAPPCK,Main            ,73662
    8060    8060    4580    5870    6930   11400   11800
River Rch & RM=KNAPPCK,Main            ,56462
   11600   11600    6670    8500    9990   16300   17000
River Rch & RM=KNAPPCK,Main            ,49521
   12900   12900    7460    9480   11100   18000   19000
River Rch & RM=KNAPPCK,Main            ,37760
   14500   14500    8400   10700   12500   20200   21300
Boundary for River Rch & Prof#=KNAPPCK,Main            , 1
Up Type= 0
Dn Type= 3
Dn Slope=0.002742
Boundary for River Rch & Prof#=KNAPPCK,Main            , 2
Up Type= 0
Dn Type= 3
Dn Slope=0.002742
Boundary for River Rch & Prof#=KNAPPCK,Main            , 3
Up Type= 0
Dn Type= 3
Dn Slope=0.002742
Boundary for River Rch & Prof#=KNAPPCK,Main            , 4
Up Type= 0
Dn Type= 3
Dn Slope=0.002742
Boundary for River Rch & Prof#=KNAPPCK,Main            , 5
Up Type= 0
Dn Type= 3
Dn Slope=0.002742
Boundary for River Rch & Prof#=KNAPPCK,Main            , 6
Up Type= 0
Dn Type= 3
Dn Slope=0.002742
DSS Import GetInterval= 0
DSS Import GetPeak= 0
DSS Import FillOption= 0

--- KNAPPCK.g01 (geometry) ---

Geom Title=Geometry
Program Version=6.10

River Reach=KNAPPCK         ,Main
Reach XY= 30
      2308924.83      471244.993     2303985.043      467373.032
     2298230.646      465502.379     2285860.322      464791.886
 2284090.8191895460902.351339548     2285363.708      457066.507
     2283173.455      456068.672      2282439.27      448160.276
     2279893.519      447511.797      2279197.21      444323.058
     2277322.299      443626.957     2277739.714      441126.621
     2272276.779      438111.241      2267876.39      431498.085
     2267713.377      429483.186     2262580.422      425185.118
     2258034.733      427644.259     2257846.221      429555.325
     2254327.735       431887.54     2249876.716      437979.359
     2245058.223      438345.882     2244241.895       442907.58
 2243009.2154724443692.250251512     2241271.541       441333.89
2238251.48119718 442968.31762866     2231393.998      442522.286
2231717.09068057444398.632423812     2228919.846      442681.708
     2229063.823      445292.972     2226937.205      444396.827

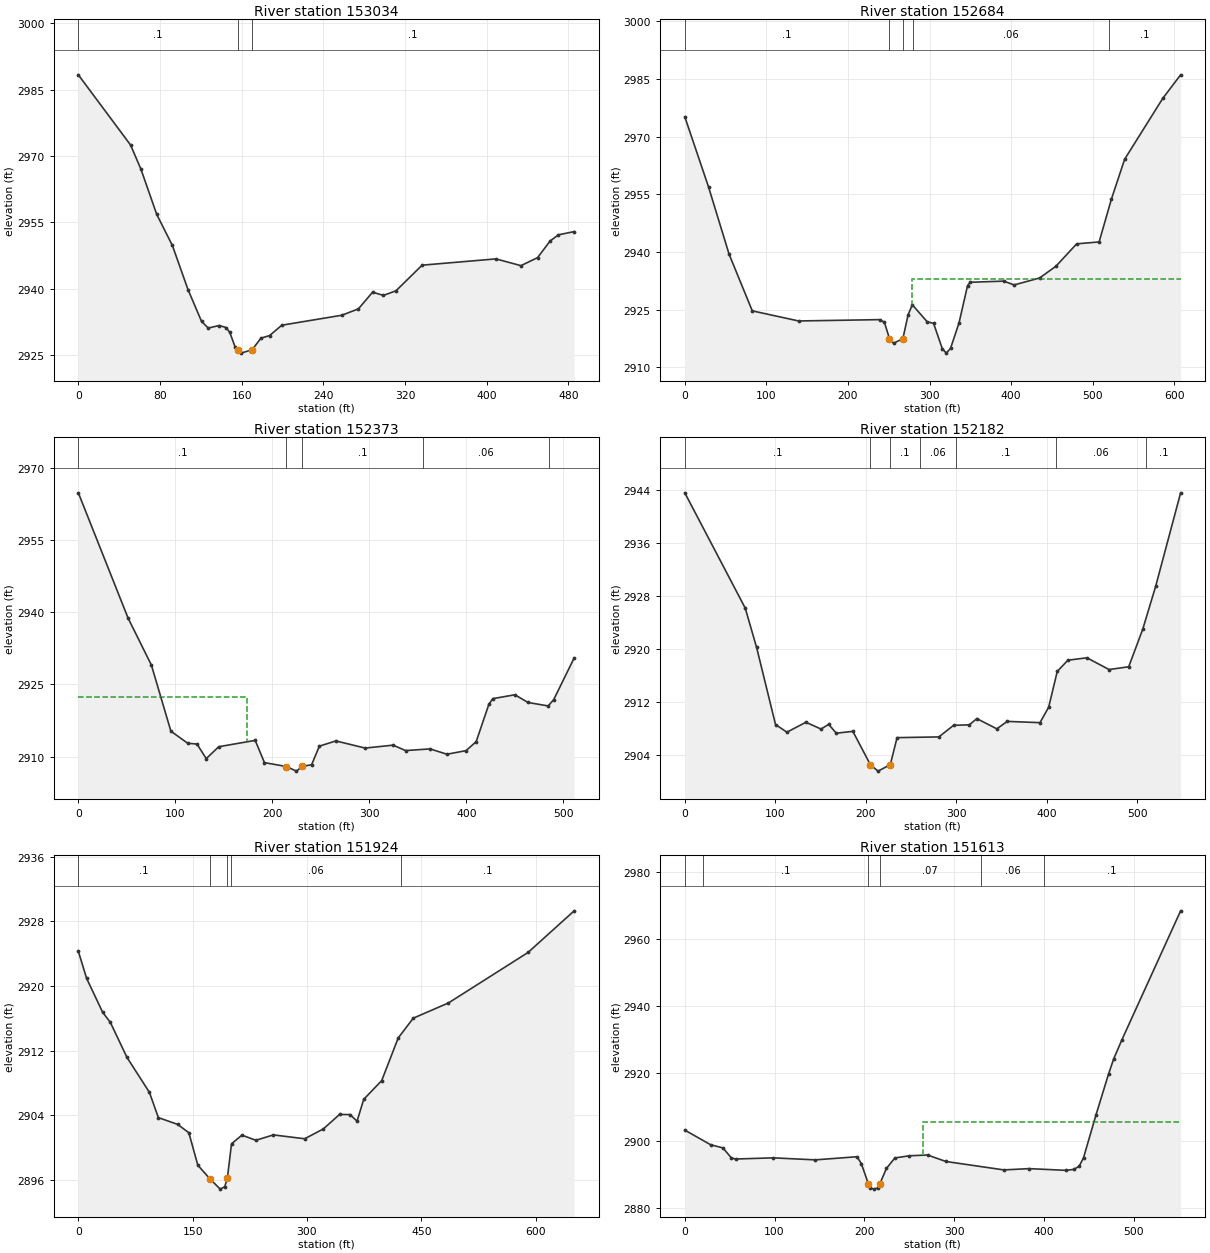
Type RM Length L Ch R = 1 ,153034  ,349.8,350.4,350.9
XS GIS Cut Line= 3
2309023.23376885471117.0526664742308881.94394492 471295.04114597
2308830.56582713471548.261869375
#Sta/Elev= 30
       0 2988.36    51.2 2972.47    61.4 2966.96    76.8 2956.78    92.1 2949.76
   107.4 2939.78   120.7 2932.57   127.2 2931.08   138.1 2931.65   144.6 2931.19
   148.3 2930.11   153.4 2926.88     156 2926.04   159.3  2925.4   170.2 2926.17
   178.9 2928.79   187.3 2929.37   199.3 2931.72     258 2933.97   274.3 2935.41
   288.2 2939.19   298.8 2938.46   311.1  2939.5   336.7  2945.3     409 2946.72
   433.5 2945.19   449.8 2947.01   462.1 2950.78   470.2 2952.17   485.6 2952.89
#Mann= 3 ,-1,0
       0      .1       0     156    .045       0   170.2      .1       0
Bank Sta=156,170.2
XS Rating Curve= 0 ,0
Exp/Cntr(USF)=0,0
Exp/Cntr=0.3,0.1

Type RM Length L Ch R = 1 ,152684  ,307.1,311.5,318.6
XS GIS Cut Line= 2
  2308786.291138470878.8493452612308397.54144953 471345.90832349
#Sta/Elev= 30
       0 2975.17    29.1 2956.92    54.3 2939.44    82.7 2924.72   139.5 2922.09
   238.9 2922.44   244.6 2921.77   250.82917.528   255.9  2916.3   267.3  2917.5
   273.7 2923.71   278.9 2926.29   297.2 2921.85   304.9 2921.48   315.6 2914.89
   320.5 2913.73   325.7 2914.97   336.1 2921.58   346.5 2931.25   349.7 2932.15
     391 2932.45   403.6 2931.46   434.9 2933.27   454.8 2936.31   480.3 2942.14
   507.8 2942.64   522.9 2953.79   539.1 2964.14   585.9 2979.99   607.7 2986.08
#Mann= 5 ,-1,0
       0      .1       0   250.8    .045       0   267.3      .1       0
     280     .06       0     520      .1       0
#XS Ineff= 2 , 0
                          278.03         2933.12
Permanent Ineff=
       F       F
Bank Sta=250.8,267.3
XS Rating Curve= 0 ,0
Exp/Cntr(USF)=0,0
Exp/Cntr=0.3,0.1

Type RM Length L Ch R = 1 ,152373  ,202.4,190.9,175.1
XS GIS Cut Line= 4
2308504.41339852470725.8165920652308411.63558353470872.465396418
2308291.92227385470947.2862149662308172.20896417471102.913517545
#Sta/Elev= 30
       0 2964.83    51.3 2938.78    75.3 2929.03    95.4 2915.28   112.8 2912.78
   122.3 2912.62   131.8 2909.59   144.7 2912.06   182.3 2913.38   191.8 2908.76
   214.3 2907.95   224.8 2906.99  230.86 2907.99   240.4 2908.31   248.4 2912.18
   265.4 2913.27   295.6 2911.78   324.4 2912.39   337.3 2911.26   362.5 2911.61
   379.9  2910.5   399.6 2911.25     410 2913.11   423.1 2920.88   427.1 2922.05
   449.9 2922.86   463.4 2921.26   484.2 2920.54   489.9 2921.84     511 2930.51
#Mann= 5 ,-1,0
       0      .1       0   214.3    .045       0  230.86      .1       0
   354.7     .06       0   484.7      .1       0
#XS Ineff= 2 , 0
          173.41 2922.34
Permanent Ineff=
       F       F
Bank Sta=214.3,230.86
XS Rating Curve= 0 ,0
Exp/Cntr(USF)=0,0
Exp/Cntr=0.3,0.1

Type RM Length L Ch R = 1 ,152182  ,252.8,257.7,260.8
XS GIS Cut Line= 2
2308294.06131663470593.5797896962308127.43213007471115.841432169
#Sta/Elev= 30
       0 2943.59    66.8 2926.21    79.4 2920.27   100.3 2908.65   112.9 2907.49
   133.9 2908.99   150.6 2907.97   159.1 2908.67   167.5 2907.34   185.8 2907.62
   205.3 2902.56   213.7 2901.62   227.2  2902.6   234.7 2906.67   280.9 2906.78
   297.2 2908.53   314.5  2908.6   322.9 2909.54     345    2908   356.5 2909.12
   392.7 2908.93   402.3 2911.26   411.8 2916.66   423.6 2918.35   444.6 2918.71
   469.1 2916.94   490.8 2917.36   506.3 2923.01   520.6 2929.49   548.2 2943.59
#Mann= 7 ,-1,0
       0      .1       0   205.3    .045       0   227.2      .1       0
     260     .06       0     300      .1       0     410     .06       0
     510      .1       0
Bank Sta=205.3,227.2
XS Rating Curve= 0 ,0
Exp/Cntr(USF)=0,0
Exp/Cntr=0.3,0.1

Type RM Length L Ch R = 1 ,151924  ,310.9,310.8,309.1
XS GIS Cut Line= 3
2308097.38814563470513.3254673892307896.86835192 470875.45822916
2307857.96152627471108.899183028
#Sta/Elev= 30
       0 2924.31    10.8 2920.97    31.8 2916.78      42 2915.51    63.8 2911.18
    93.3 2906.85     105 2903.73   130.3 2902.89     145 2901.86   156.8 2897.84
   172.52896.172   186.2 2894.88   192.1 2895.18   195.62896.254     201 2900.49
   214.7 2901.56     233 2900.92   255.9 2901.59     297 2901.11   321.5 2902.33
   342.8 2904.12   356.5  2904.1   365.7 2903.29   374.5 2905.99   398.1 2908.31
   419.7 2913.58   439.5 2916.03   485.6 2917.91   590.1 2924.16   650.6 2929.31
#Mann= 5 ,-1,0
       0      .1       0   172.5    .045       0   195.6      .1       0
     200     .06       0  423.94      .1       0
Bank Sta=172.5,195.6
XS Rating Curve= 0 ,0
Exp/Cntr(USF)=0,0
Exp/Cntr=0.3,0.1

Type RM Length L Ch R = 1 ,151613  ,288,288.4,289.5
XS GIS Cut Line= 2
2307831.15185912 470400.771462142307545.71449793470873.781946391
#Sta/Elev= 30
       0 2903.14    28.7 2898.79    42.5 2897.84    51.9 2894.86    56.5 2894.53
    98.6 2894.88   145.3 2894.28   191.9 2895.21   196.7 2893.19   204.62887.093
     206 2886.04   210.7 2885.57   215.2 2885.94     2172886.955   224.7 2891.74
   234.1 2894.85   250.1 2895.49   270.5 2895.73   290.9  2893.8   355.5 2891.29
   383.6 2891.67   424.9 2891.16   433.7 2891.45   439.5 2892.41   444.3  2894.9
   458.3 2907.75   472.3 2919.92     478 2924.39   487.2  2930.1   552.5  2968.4
#Mann= 6 ,-1,0
       0     .06       0      20      .1       0   204.6    .045       0
     217     .07       0     330     .06       0     400      .1       0
#XS Ineff= 2 , 0
                          265.69         2905.63
Permanent Ineff=
       F       F
Bank Sta=204.6,217
XS Rating Curve= 0 ,0
Exp/Cntr(USF)=0,0
Exp/Cntr=0.3,0.1

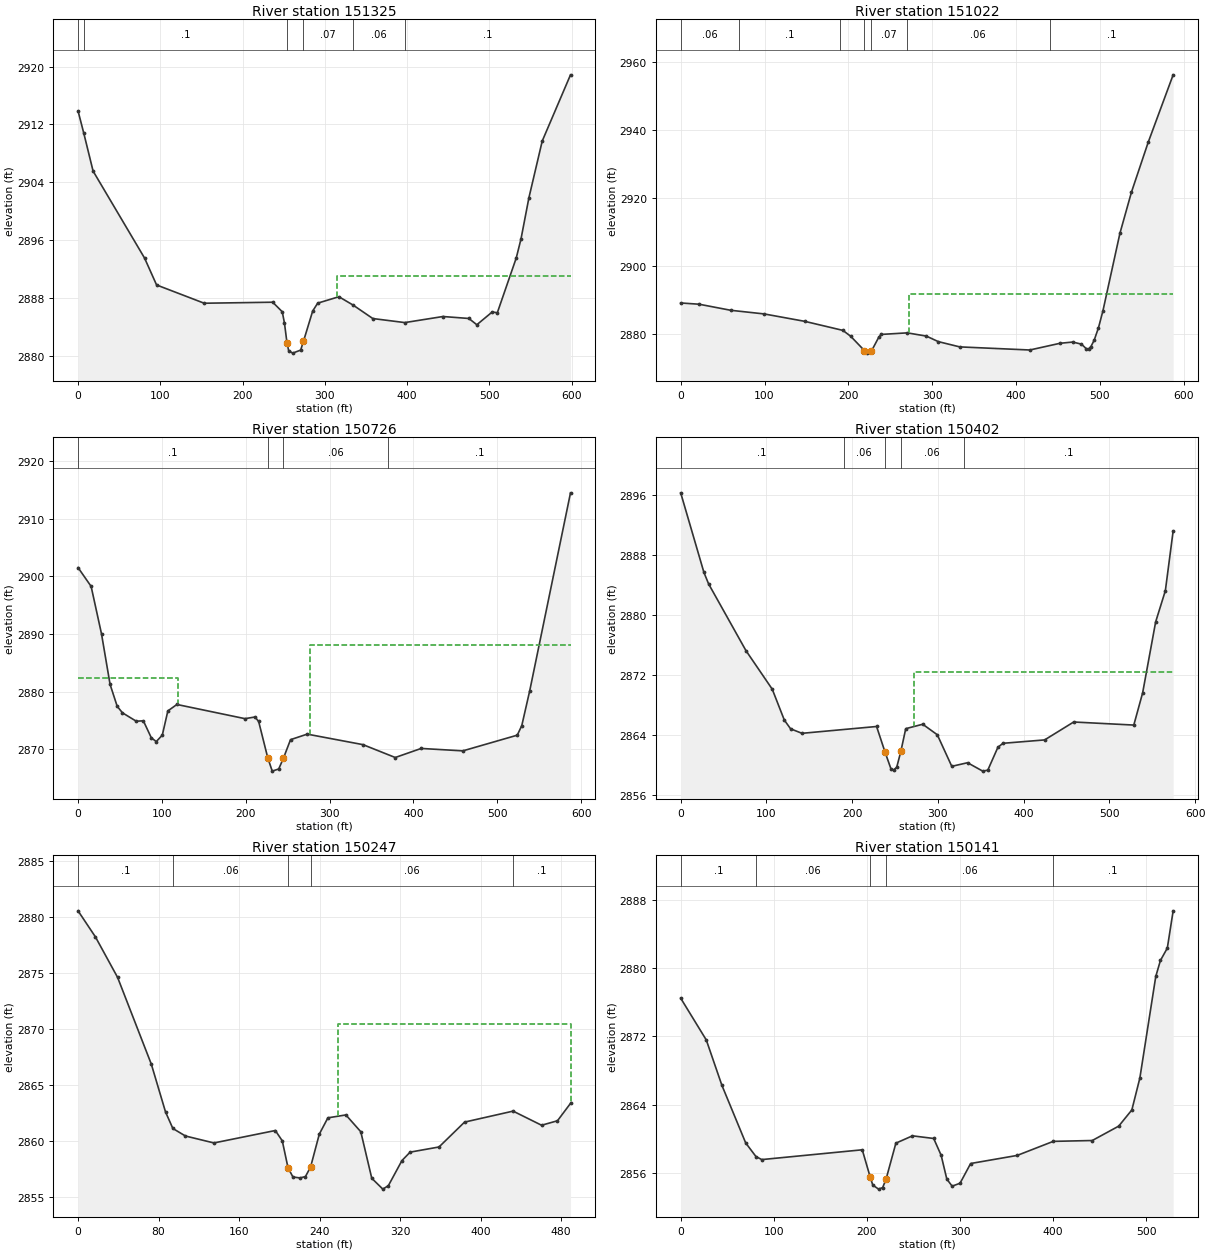
Type RM Length L Ch R = 1 ,151325  ,301.9,303.1,304.3
XS GIS Cut Line= 2
2307647.21516593470186.7291799162307305.93021229470678.739349675
#Sta/Elev= 30
       0 2913.87     6.8 2910.87    18.3 2905.54    80.9 2893.49    95.5 2889.77
   153.4 2887.24   236.7 2887.38   248.3 2886.06     251 2884.49     254  2881.8
   256.1 2880.67     261 2880.33   270.7 2880.75   274.1 2881.97   285.3 2886.16
   291.4 2887.25   317.2 2888.14   334.5 2886.98   358.4 2885.12   397.3 2884.56
   443.7  2885.4   475.2 2885.13   484.9 2884.26   503.6 2886.03   509.8 2885.92
   532.8  2893.5   538.6 2896.14   548.2 2901.84   564.4  2909.7  598.79 2918.87
#Mann= 6 ,-1,0
       0     .06       0     6.8      .1       0     254    .045       0
   274.1     .07       0   334.5     .06       0   397.3      .1       0
#XS Ineff= 2 , 0
                           314.7         2891.01
Permanent Ineff=
       F       F
Bank Sta=254,274.1
XS Rating Curve= 0 ,0
Exp/Cntr(USF)=0,0
Exp/Cntr=0.3,0.1

Type RM Length L Ch R = 1 ,151022  ,293.9,295.4,296.7
XS GIS Cut Line= 2
2307398.91814075470043.974760657 2307031.9272478470502.713376849
#Sta/Elev= 30
       0 2889.25      22 2888.88    59.7  2887.1    99.6 2886.03   147.9 2883.86
   193.5  2881.2   202.9 2879.45   219.1 2875.29   222.1 2874.52   227.6 2875.14
   236.2 2879.14     239 2880.01   270.3 2880.47   293.1 2879.52   307.3  2877.9
   332.9 2876.35   416.5 2875.44   452.5 2877.41   467.7 2877.77   478.1 2877.16
   483.8 2875.83   486.6 2875.77   489.4 2876.44   493.3 2878.32   498.4 2881.96
   503.7 2886.91     524 2909.71   537.8 2921.82   557.7 2936.41   587.5 2956.24
#Mann= 7 ,-1,0
       0     .06       0      70      .1       0     190     .07       0
   219.1    .045       0   227.6     .07       0     270     .06       0
     440      .1       0
#XS Ineff= 2 , 0
                          271.78         2891.76
Permanent Ineff=
       F       F
Bank Sta=219.1,227.6
XS Rating Curve= 0 ,0
Exp/Cntr(USF)=0,0
Exp/Cntr=0.3,0.1

Type RM Length L Ch R = 1 ,150726  ,324.3,324.2,324.6
XS GIS Cut Line= 2
2307187.02469699469862.0085670492306791.45201926 470296.05747357
#Sta/Elev= 30
       0 2901.51    15.6 2898.25      28 2890.01    38.2 2881.27    46.7 2877.47
      53 2876.34    69.4 2874.89    77.9 2874.96    87.4 2872.01    93.3 2871.36
   100.5 2872.48   107.1 2876.67   117.9 2877.79   199.1 2875.33     211 2875.62
   215.4 2874.84   226.2 2868.58   231.6 2866.24   239.3 2866.61   244.9 2868.46
   253.4 2871.69   273.3 2872.65   339.8 2870.83   378.3  2868.6   409.2 2870.17
   458.9 2869.75   523.8 2872.47   529.2 2874.13   538.7 2880.19   587.3 2914.46
#Mann= 4 ,-1,0
       0      .1       0   226.2    .045       0   244.9     .06       0
     370      .1       0
#XS Ineff= 2 , 0
          119.32 2882.39  276.17         2888.12
Permanent Ineff=
       F       F
Bank Sta=226.2,244.9
XS Rating Curve= 0 ,0
Exp/Cntr(USF)=0,0
Exp/Cntr=0.3,0.1

Type RM Length L Ch R = 1 ,150402  ,154.3,154.6,154.7
XS GIS Cut Line= 2
2306939.10957014469657.236167881 2306549.5225579470079.313743435
#Sta/Elev= 30
       0 2896.33    27.1 2885.72    32.6 2884.18    76.1  2875.3   106.8 2870.15
   120.9 2866.03   128.2 2864.87   141.5 2864.27   228.5 2865.18   238.22861.815
   245.5 2859.46   248.3 2859.38     252 2859.75   256.8 2861.87   262.5 2864.89
   282.3 2865.48   299.3 2864.08   316.2 2859.87   334.6 2860.35   352.3 2859.23
   358.2 2859.36     370 2862.41   375.9 2862.94   424.5 2863.39   458.4 2865.78
   528.5 2865.37   538.8 2869.66     554 2879.13   565.3 2883.28   574.4 2891.25
#Mann= 5 ,-1,0
       0      .1       0     190     .06       0   238.2    .045       0
   256.8     .06       0     330      .1       0
#XS Ineff= 2 , 0
                          271.77         2872.47
Permanent Ineff=
       F       F
Bank Sta=238.2,256.8
XS Rating Curve= 0 ,0
Exp/Cntr(USF)=0,0
Exp/Cntr=0.3,0.1

Type RM Length L Ch R = 1 ,150247  ,107.8,106.7,105.7
BEGIN DESCRIPTION:
structure xs 4
END DESCRIPTION:
XS GIS Cut Line= 2
2306806.44615691469576.5823827832306471.28450512469932.986674471
#Sta/Elev= 30
       0 2880.57    17.3 2878.24    39.3 2874.63    72.8 2866.89    86.9 2862.63
    94.2 2861.15   106.7 2860.48     135 2859.86     196 2860.97   202.9 2860.05
   208.6 2857.65   213.5 2856.82   220.5 2856.74   225.9 2856.86     231 2857.71
   239.7 2860.65   248.2  2862.1   266.1 2862.36   280.9 2860.86   291.8 2856.71
   302.8 2855.74   308.3 2856.05   321.8 2858.29   329.9 2859.04   358.6  2859.5
     384 2861.72   432.2  2862.7   460.5 2861.44   476.3 2861.84489.2416 2863.39
#Mann= 5 ,-1,0
       0      .1       0    94.2     .06       0   208.6    .045       0
     231     .06       0   432.2      .1       0
#XS Ineff= 2 , 0
                          258.59         2870.45
Permanent Ineff=
       F       F
Bank Sta=208.6,231
XS Rating Curve= 0 ,0
Exp/Cntr(USF)=0,0
Exp/Cntr=0.5,0.3

Type RM Length L Ch R = 1 ,150141  ,54.5,55.6,56.4
BEGIN DESCRIPTION:
structure xs 3
END DESCRIPTION:
XS GIS Cut Line= 2
2306713.21457067469503.4132897882306372.15218558469907.613521255
#Sta/Elev= 30
       0  2876.5    27.5 2871.59    44.2 2866.28    69.8  2859.5    80.8  2857.9
    87.1 2857.54     195 2858.69   203.5 2855.49   206.3 2854.55   212.5 2854.07
   216.9 2854.25   220.6 2855.26   231.1 2859.47   248.9 2860.33   271.7 2860.02
   279.7 2858.05   285.8 2855.25   291.5 2854.42     300 2854.76   311.4 2857.08
   361.4 2858.03   400.1 2859.68     442 2859.78   470.4 2861.47   484.5 2863.37
   493.1 2867.11   510.2 2879.05   515.2 2880.93   522.6 2882.38 528.868 2886.76
#Mann= 5 ,-1,0
       0      .1       0    80.8     .06       0   203.5    .045       0
   220.6     .06       0   400.1      .1       0
#XS Ineff= 2 , 0
           185.5 2857.72   238.6         2859.82
Permanent Ineff=
       F       F
Bank Sta=203.5,220.6
XS Rating Curve= 0 ,0
Exp/Cntr(USF)=0,0
Exp/Cntr=0.5,0.3

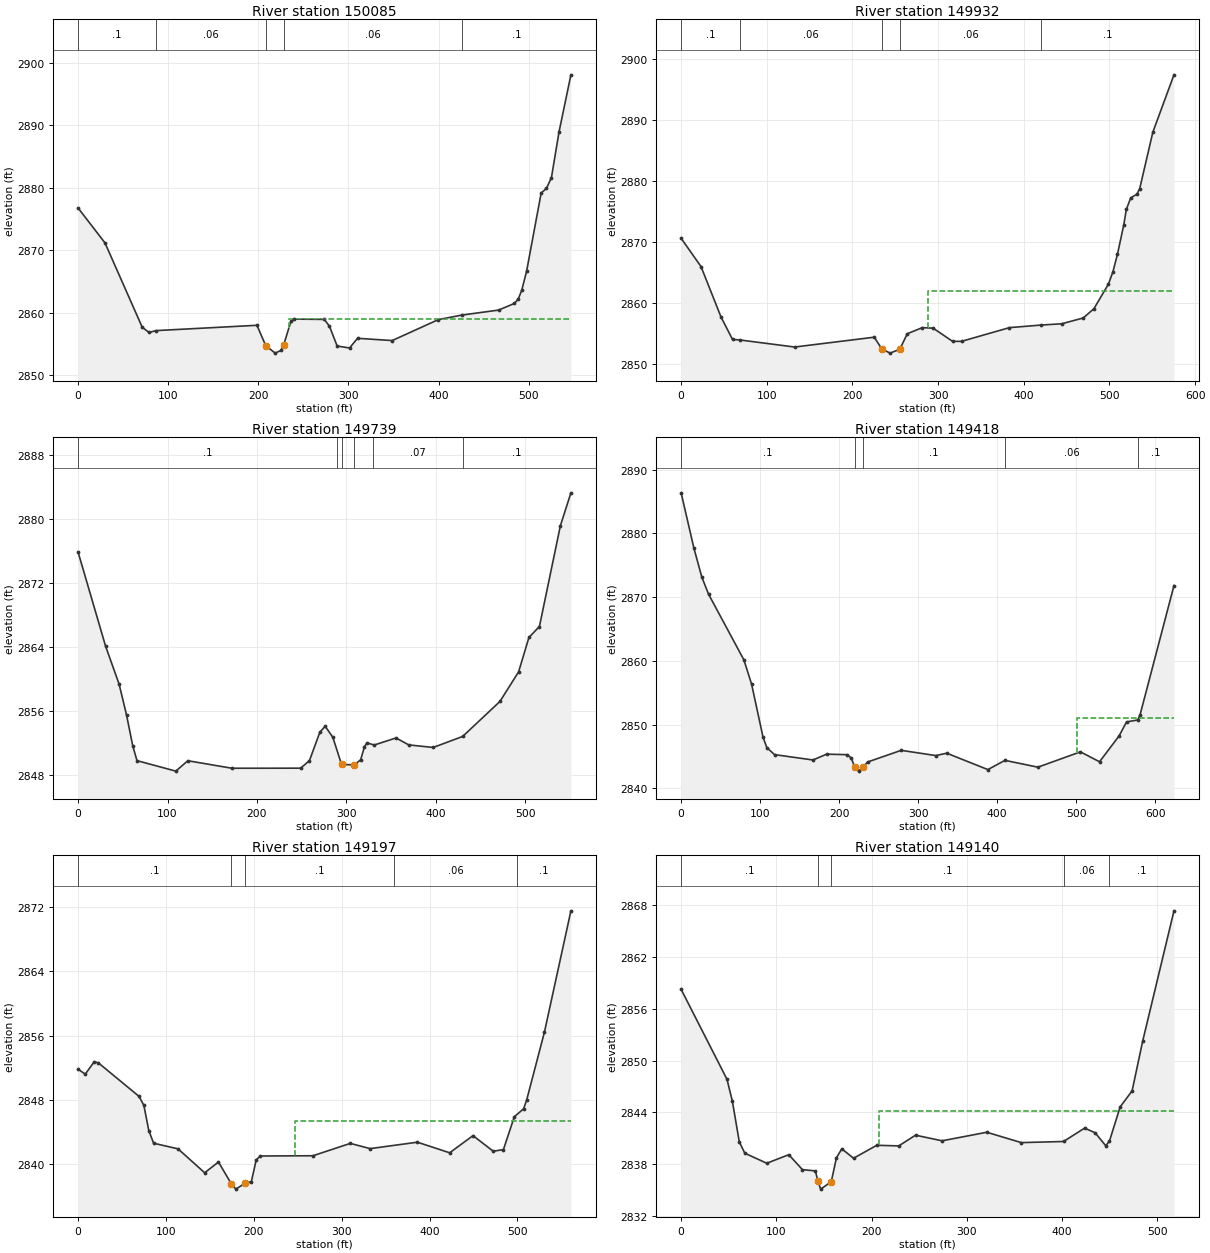
Type RM Length L Ch R = 1 ,150085  ,153.9,153,152.1
BEGIN DESCRIPTION:
structure xs 2
END DESCRIPTION:
XS GIS Cut Line= 2
2306680.42738452469471.2251111432306309.75136317 469873.30685195
#Sta/Elev= 30
       0 2876.78    29.9 2871.19    71.2 2857.71    78.8 2856.87    86.5 2857.17
   198.5 2858.02   208.2 2854.78   218.7 2853.57   225.2 2854.01     228  2854.8
   236.4 2858.74   239.3 2859.01   273.3 2858.96     279 2857.86   287.5 2854.71
   301.3 2854.39   310.1 2855.94   348.6 2855.58   399.8 2858.93   426.2 2859.66
   466.6 2860.45   484.3 2861.52   488.5 2862.24   492.3  2863.6   497.7 2866.64
   513.9 2879.17   519.7 2879.89   525.3 2881.64   533.7 2888.92   546.9 2898.06
#Mann= 5 ,-1,0
       0      .1       0    86.5     .06       0   208.2    .045       0
     228     .06       0   426.2      .1       0
#XS Ineff= 2 , 0
           202.2  2856.6     234            2859
Permanent Ineff=
       F       F
Bank Sta=208.2,228
XS Rating Curve= 0 ,0
Exp/Cntr(USF)=0,0
Exp/Cntr=0.5,0.3

Type RM Length L Ch R = 1 ,149932  ,191.8,193.1,193.9
BEGIN DESCRIPTION:
structure xs 1
END DESCRIPTION:
XS GIS Cut Line= 3
2306589.29917124469369.4666437392306424.07863867469522.885709698
2306200.44084637469791.959148455
#Sta/Elev= 30
       0  2870.6    23.2 2865.97    46.6 2857.69      60 2854.02    68.5 2853.94
   132.5 2852.78   225.5 2854.39  234.34 2852.44   244.1 2851.78   255.4 2852.44
     264 2854.96   281.6 2855.96   294.2 2855.87   316.9 2853.71   327.3 2853.71
   383.3 2855.96   420.2 2856.38   444.3 2856.59   469.4 2857.54   481.9 2859.06
   498.9 2863.11   504.1 2865.13   509.3 2867.95   516.8 2872.84   519.7 2875.32
   524.9 2877.24     532 2877.82   535.3 2878.72   550.7 2888.01575.3444 2897.39
#Mann= 5 ,-1,0
       0      .1       0    68.5     .06       0  234.34    .045       0
   255.4     .06       0   420.2      .1       0
#XS Ineff= 2 , 0
                          288.68         2861.93
Permanent Ineff=
       F       F
Bank Sta=234.34,255.4
XS Rating Curve= 0 ,0
Exp/Cntr(USF)=0,0
Exp/Cntr=0.3,0.1

Type RM Length L Ch R = 1 ,149739  ,313.7,320.7,322.4
XS GIS Cut Line= 2
2306473.28555519469191.7403536892306096.10047076469593.391497643
#Sta/Elev= 30
       0 2875.85    30.8 2864.06    45.9 2859.32    54.2 2855.46    61.2 2851.57
    65.9 2849.75   109.3 2848.44   122.7 2849.74   172.1  2848.8   248.9 2848.81
   258.7 2849.76   270.4 2853.33   276.3 2854.05   284.8 2852.68   294.6 2849.27
   308.72849.223   315.9 2849.85   320.2 2851.49     323 2851.97   331.2 2851.71
   355.5 2852.59   369.7 2851.72   397.1  2851.4     430 2852.78   471.6 2857.15
   492.5 2860.85   504.1 2865.17   515.8 2866.53   539.2 2879.12     551 2883.25
#Mann= 6 ,-1,0
       0      .1       0     290     .06       0   294.6    .045       0
   308.7     .06       0     330     .07       0     430      .1       0
Bank Sta=294.6,308.7
XS Rating Curve= 0 ,0
Exp/Cntr(USF)=0,0
Exp/Cntr=0.3,0.1

Type RM Length L Ch R = 1 ,149418  ,223.3,221,219
XS GIS Cut Line= 4
 2306401.5444641468994.3043138962306126.84775772469183.452617429
2306042.08420261469182.6677696972305881.97526518469311.382797828
#Sta/Elev= 30
       0 2886.36    16.2 2877.67    26.1 2873.18    34.7 2870.47    79.4 2860.17
    89.1  2856.4   103.7 2848.02   108.5  2846.4   118.2 2845.31   166.8 2844.47
   184.2 2845.38   210.1  2845.3   215.4 2844.76  219.61 2843.34   224.5 2842.72
   229.9 2843.33     236 2844.15   278.5 2845.98   322.3 2845.16   336.2 2845.53
   388.2 2842.96   409.8 2844.41   451.5 2843.34   505.3 2845.74   529.5 2844.19
   554.2 2848.23   563.7 2850.44   577.9 2850.74   580.8 2851.55623.7191 2871.82
#Mann= 5 ,-1,0
       0      .1       0  219.61    .045       0   229.9      .1       0
   409.8     .06       0   577.9      .1       0
#XS Ineff= 2 , 0
                          501.24         2851.12
Permanent Ineff=
       F       F
Bank Sta=219.61,229.9
XS Rating Curve= 0 ,0
Exp/Cntr(USF)=0,0
Exp/Cntr=0.3,0.1

Type RM Length L Ch R = 1 ,149197  ,56.8,57.3,57.6
XS GIS Cut Line= 2
2306208.23657694 468851.254358562305818.81846275469254.944340808
#Sta/Elev= 30
       0 2851.83     8.2  2851.2    18.4 2852.75    23.1 2852.61    69.4 2848.43
    74.9 2847.31    80.5 2844.17      86 2842.59   113.8 2841.89   144.1 2838.91
   159.8 2840.25   174.42837.533   179.6 2836.87   190.2 2837.61   197.2 2837.79
   202.8 2840.53   207.5    2841   267.3 2841.03   309.8 2842.57   332.4 2841.92
   386.2 2842.72   422.9  2841.4   449.5 2843.54   472.5 2841.59   484.1  2841.8
   496.5 2845.89   507.1 2846.89   510.6    2848   530.7 2856.41   560.9 2871.56
#Mann= 5 ,-1,0
       0      .1       0   174.4    .045       0   190.2      .1       0
     360     .06       0     500      .1       0
#XS Ineff= 2 , 0
                           246.7         2845.33
Permanent Ineff=
       F       F
Bank Sta=174.4,190.2
XS Rating Curve= 0 ,0
Exp/Cntr(USF)=0,0
Exp/Cntr=0.3,0.1

Type RM Length L Ch R = 1 ,149140  ,286.6,285.2,283.7
XS GIS Cut Line= 2
 2306149.9464154468838.8543046942305776.48377054469197.311754001
#Sta/Elev= 30
       0 2858.25    48.2 2847.82    53.8  2845.3    61.1 2840.58    66.9 2839.26
      90  2838.1   113.1 2839.09   127.4 2837.36   141.1 2837.21  143.61 2836.02
   146.6  2835.1   157.7 2835.96   163.2 2838.75   168.8 2839.77   181.1 2838.68
   205.5 2840.18   228.6 2840.11   246.2 2841.35   274.1  2840.7   321.1 2841.69
   357.3 2840.49   401.7 2840.62   423.8 2842.17   434.9 2841.63     446 2840.13
   449.9 2840.66   461.2 2844.64   473.7 2846.48   484.8 2852.24   517.7 2867.35
#Mann= 5 ,-1,0
       0      .1       0  143.61    .045       0   157.7      .1       0
   401.7     .06       0   449.9      .1       0
#XS Ineff= 2 , 0
                          207.55         2844.15
Permanent Ineff=
       F       F
Bank Sta=143.61,157.7
XS Rating Curve= 0 ,0
Exp/Cntr(USF)=0,0
Exp/Cntr=0.3,0.1