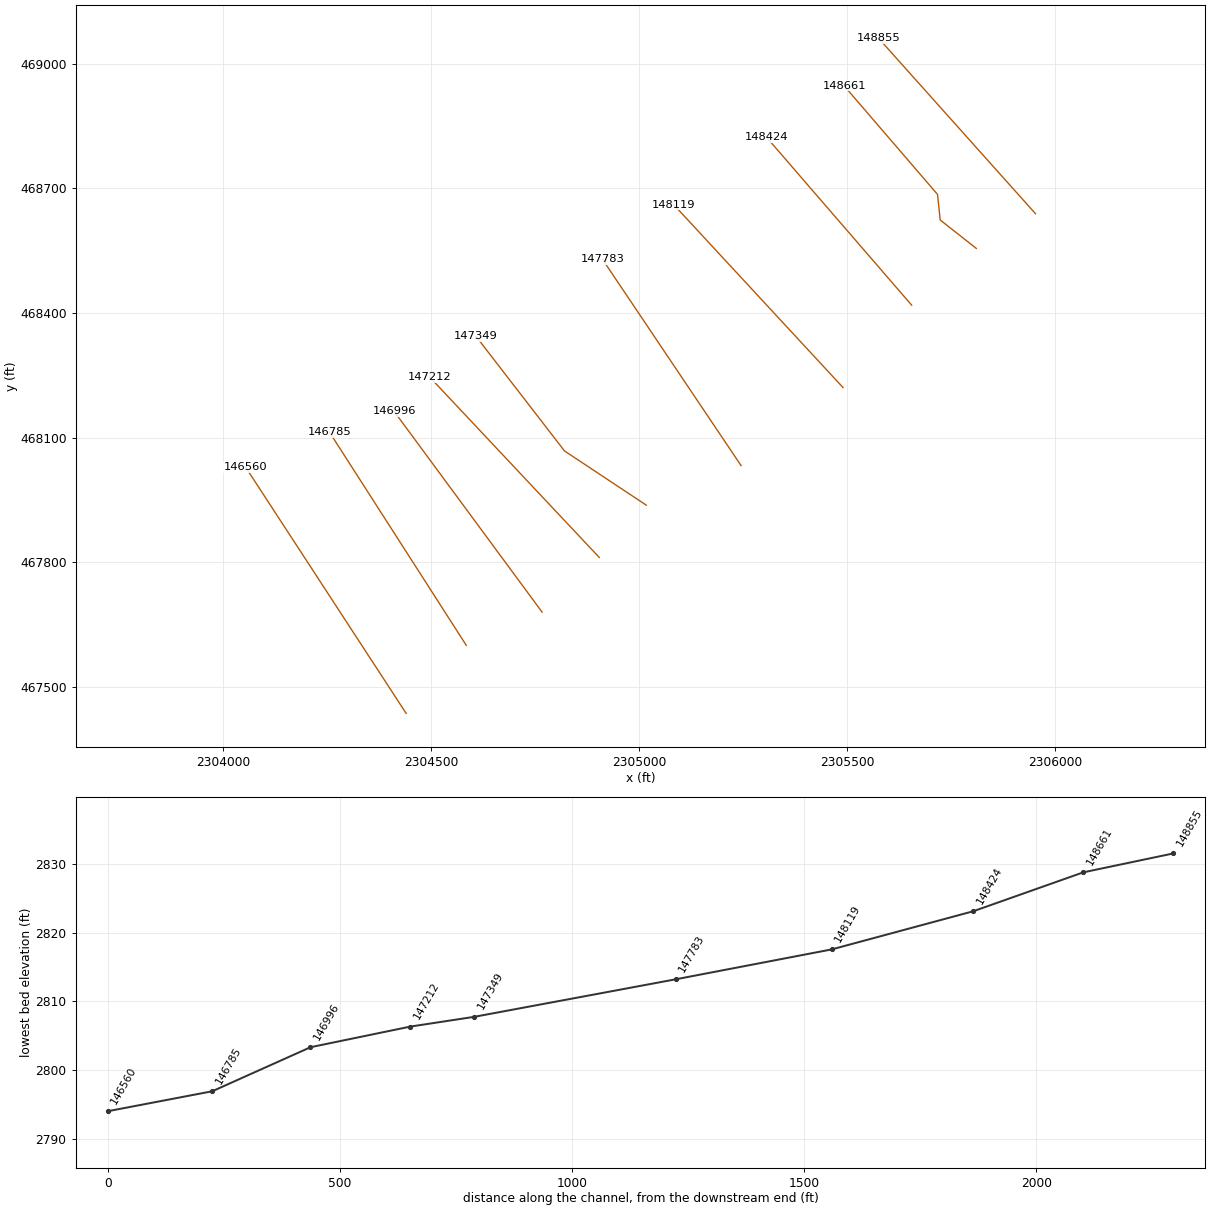
HEC-RAS study KNAPPCK.prj: KNAPPCK

--- KNAPPCK.g01 (geometry) --- (continued)

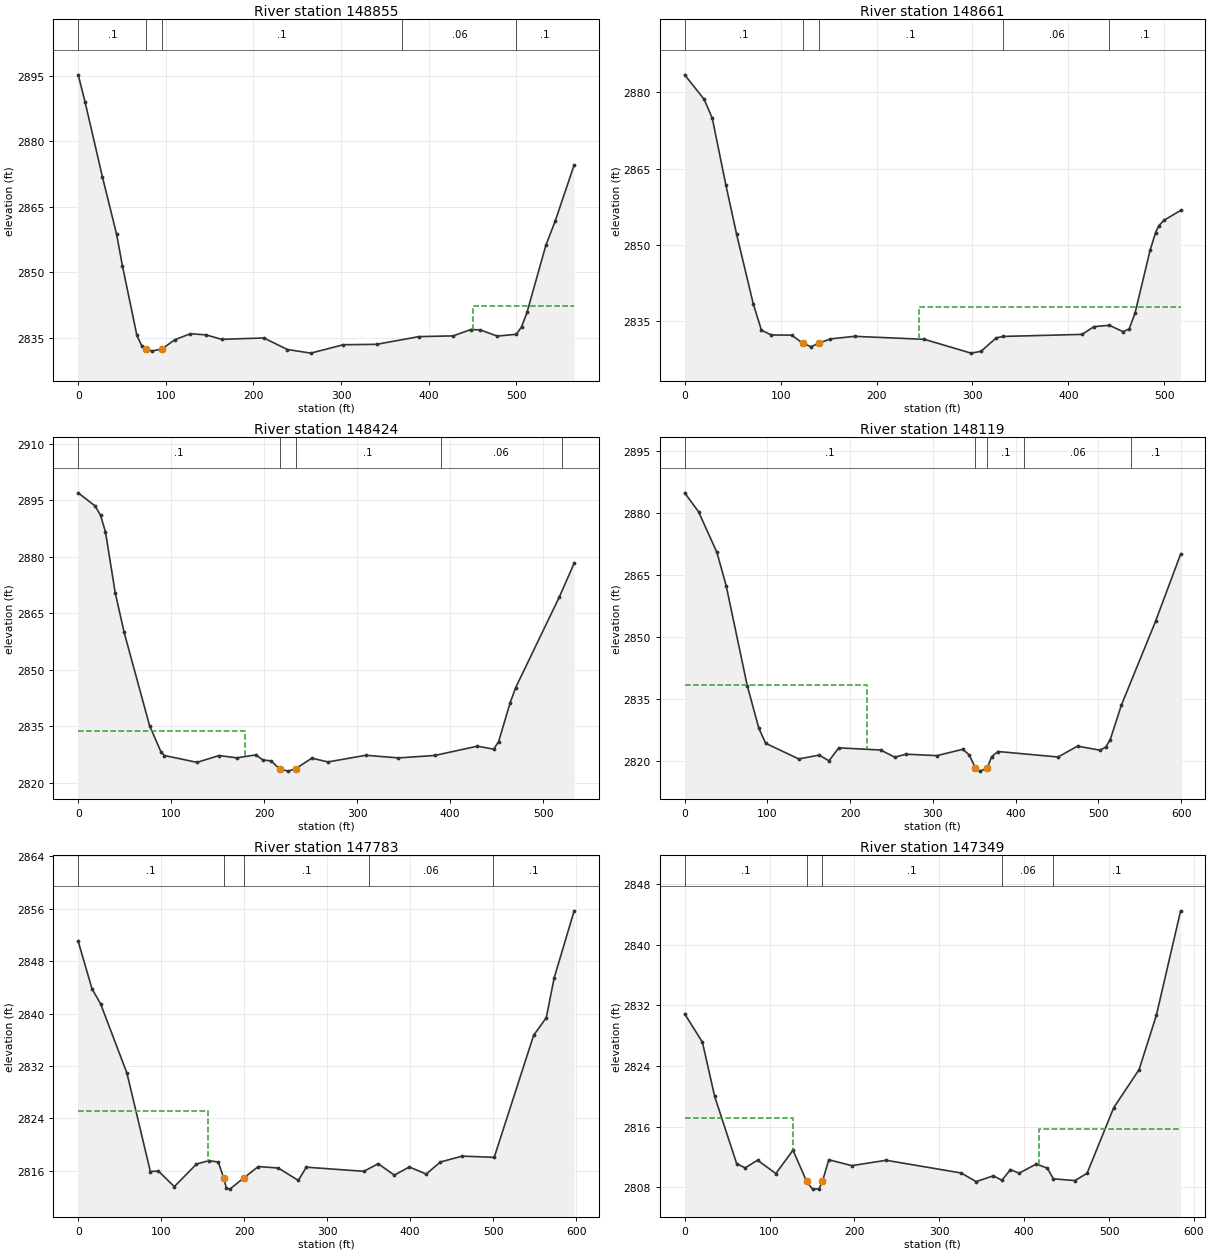
Type RM Length L Ch R = 1 ,148855  ,205.9,194.1,184
XS GIS Cut Line= 2
2305953.38179017468639.2151759652305576.19670575469061.254702861
#Sta/Elev= 30
       0 2895.22     7.8 2889.02    27.7 2871.79    43.8 2858.73    50.4 2851.55
      67 2835.54    72.4 2833.22    77.7 2832.44    84.4    2832    95.7 2832.45
   109.9 2834.53   127.9 2835.94   145.9 2835.68   163.6 2834.66   211.9 2834.97
   238.7 2832.33   265.5  2831.5   302.5 2833.42   340.6 2833.52   388.9 2835.28
     428 2835.45   447.9 2836.89   458.6 2836.83   478.2  2835.4     500 2835.81
     506 2837.52   512.2 2840.83   533.7 2856.17   544.5  2861.8     566 2874.59
#Mann= 5 ,-1,0
       0      .1       0    77.7    .045       0    95.7      .1       0
     370     .06       0     500      .1       0
#XS Ineff= 2 , 0
                          450.93          2842.4
Permanent Ineff=
       F       F
Bank Sta=77.7,95.7
XS Rating Curve= 0 ,0
Exp/Cntr(USF)=0,0
Exp/Cntr=0.3,0.1

Type RM Length L Ch R = 1 ,148661  ,222.6,236.8,245.5
BEGIN DESCRIPTION:
IFA placed to uncross profiles at this xs
END DESCRIPTION:
XS GIS Cut Line= 4
2305811.08768879468555.636551747 2305724.2050448468624.153758795
2305717.84777817 468685.607336252305493.22435712468946.961631174
#Sta/Elev= 30
       0 2883.41    20.3  2878.6    28.8 2874.88      43 2861.72    54.2 2852.06
    71.5 2838.44      80 2833.26    90.3 2832.32   111.7 2832.28  122.91 2830.71
   131.8    2830   139.8  2830.7   151.9 2831.54   177.1 2832.05   249.9 2831.46
   298.5 2828.75     309 2829.11   324.8 2831.75   332.2 2832.03   414.3 2832.43
   426.6 2833.94   442.8 2834.22     457 2832.96   463.4  2833.5   469.6 2836.67
   485.3 2849.01     491 2852.44   494.1 2853.72   499.5 2854.82517.0488 2856.78
#Mann= 5 ,-1,0
       0      .1       0  122.91    .045       0   139.8      .1       0
   332.2     .06       0   442.8      .1       0
#XS Ineff= 2 , 0
                          244.73         2837.76
Permanent Ineff=
       F       F
Bank Sta=122.91,139.8
XS Rating Curve= 0 ,0
Exp/Cntr(USF)=0,0
Exp/Cntr=0.3,0.1

Type RM Length L Ch R = 1 ,148424  ,304.4,305.1,305.2
XS GIS Cut Line= 2
2305655.71139922468419.0206401932305307.07005091468822.710622441
#Sta/Elev= 30
       0 2897.03    18.2 2893.53      24 2891.07    29.3 2886.68    39.8 2870.49
    49.4 2859.95    76.8 2835.14    89.1 2828.16    92.7 2827.25   127.8 2825.43
   151.5 2827.24   170.6 2826.63   191.2 2827.42   198.4 2826.08   207.4 2825.82
   216.7 2823.67   225.7  2823.1   233.8 2823.74   251.3 2826.54   268.6 2825.54
   309.4 2827.31   344.4 2826.61   383.4 2827.26   429.4 2829.73   446.8 2828.93
   452.2 2830.97   464.4 2841.13   470.5 2845.28   517.4 2869.34   533.4 2878.32
#Mann= 5 ,-1,0
       0      .1       0   216.7    .045       0   233.8      .1       0
     390     .06       0     520      .1       0
#XS Ineff= 2 , 0
          179.83 2833.77
Permanent Ineff=
       F       F
Bank Sta=216.7,233.8
XS Rating Curve= 0 ,0
Exp/Cntr(USF)=0,0
Exp/Cntr=0.3,0.1

Type RM Length L Ch R = 1 ,148119  ,341.2,335.7,327.6
XS GIS Cut Line= 2
2305490.63082743 468220.815587092305083.60557453 468660.76200015
#Sta/Elev= 30
       0  2884.9    16.8 2880.31      39 2870.46    50.1 2862.46    75.6 2838.26
    89.7 2827.88    97.9 2824.28   137.9  2820.5   162.6 2821.43   174.4 2820.05
   186.2 2823.18   236.9 2822.66   253.9 2820.92   267.5 2821.65   304.9  2821.3
     336 2822.83   343.8 2821.51   351.32818.382     357 2817.55   365.6 2818.25
     371 2821.03   378.5  2822.3   451.3 2820.97   474.8  2823.6   501.8 2822.62
   508.7 2823.31   514.3 2825.16   527.8 2833.52   569.1 2853.81   599.4 2870.06
#Mann= 5 ,-1,0
       0      .1       0   351.3    .045       0   365.6      .1       0
     410     .06       0     540      .1       0
#XS Ineff= 2 , 0
          220.06 2838.34
Permanent Ineff=
       F       F
Bank Sta=351.3,365.6
XS Rating Curve= 0 ,0
Exp/Cntr(USF)=0,0
Exp/Cntr=0.3,0.1

Type RM Length L Ch R = 1 ,147783  ,421.9,434.5,439.8
XS GIS Cut Line= 2
2305245.45182691468033.0005898272304912.44157219468529.117908079
#Sta/Elev= 30
       0 2851.04    16.6  2843.8      27 2841.49    58.7 2830.92    86.9  2815.9
    96.6 2815.97   115.8 2813.59   142.5 2817.04   157.2 2817.55   168.8 2817.35
  175.16 2814.94   178.5 2813.36   182.7 2813.21     200 2814.97     217 2816.66
   241.1 2816.43   265.2 2814.54   274.8 2816.56   344.1 2815.93   361.4 2817.09
   380.8 2815.35   398.9 2816.59   419.3 2815.51   436.3 2817.35   462.7 2818.25
   501.2 2818.06   548.7  2836.7   563.9 2839.37   573.5  2845.5   597.5  2855.7
#Mann= 5 ,-1,0
       0      .1       0  175.16    .045       0     200      .1       0
     350     .06       0     500      .1       0
#XS Ineff= 2 , 0
          155.83 2825.08
Permanent Ineff=
       F       F
Bank Sta=175.16,200
XS Rating Curve= 0 ,0
Exp/Cntr(USF)=0,0
Exp/Cntr=0.3,0.1

Type RM Length L Ch R = 1 ,147349  ,141.8,136.9,132.4
XS GIS Cut Line= 3
 2305017.6348886467937.7339786182304820.80747781468068.334754722
2304608.23387415468343.893129835
#Sta/Elev= 30
       0 2830.89    20.9 2827.15    35.3    2820    61.3 2811.09    71.3 2810.56
    85.8 2811.57   107.4 2809.81   127.6 2812.89   143.7 2808.76   150.6 2807.75
   158.2 2807.79   162.3 2808.79   169.8 2811.63   196.9 2810.85   237.3 2811.56
   325.7 2809.88   343.4 2808.74   363.6 2809.51   373.7 2808.92   383.8 2810.34
   393.9 2809.85   414.1 2811.06   427.2 2810.52   434.3 2809.11   459.7 2808.88
     474 2809.84   505.3 2818.48   535.3 2823.54   555.6 2830.69   584.2 2844.49
#Mann= 5 ,-1,0
       0      .1       0   143.7    .045       0   162.3      .1       0
   373.7     .06       0   434.3      .1       0
#XS Ineff= 2 , 0
           127.1 2817.11  416.79         2815.75
Permanent Ineff=
       F       F
Bank Sta=143.7,162.3
XS Rating Curve= 0 ,0
Exp/Cntr(USF)=0,0
Exp/Cntr=0.3,0.1

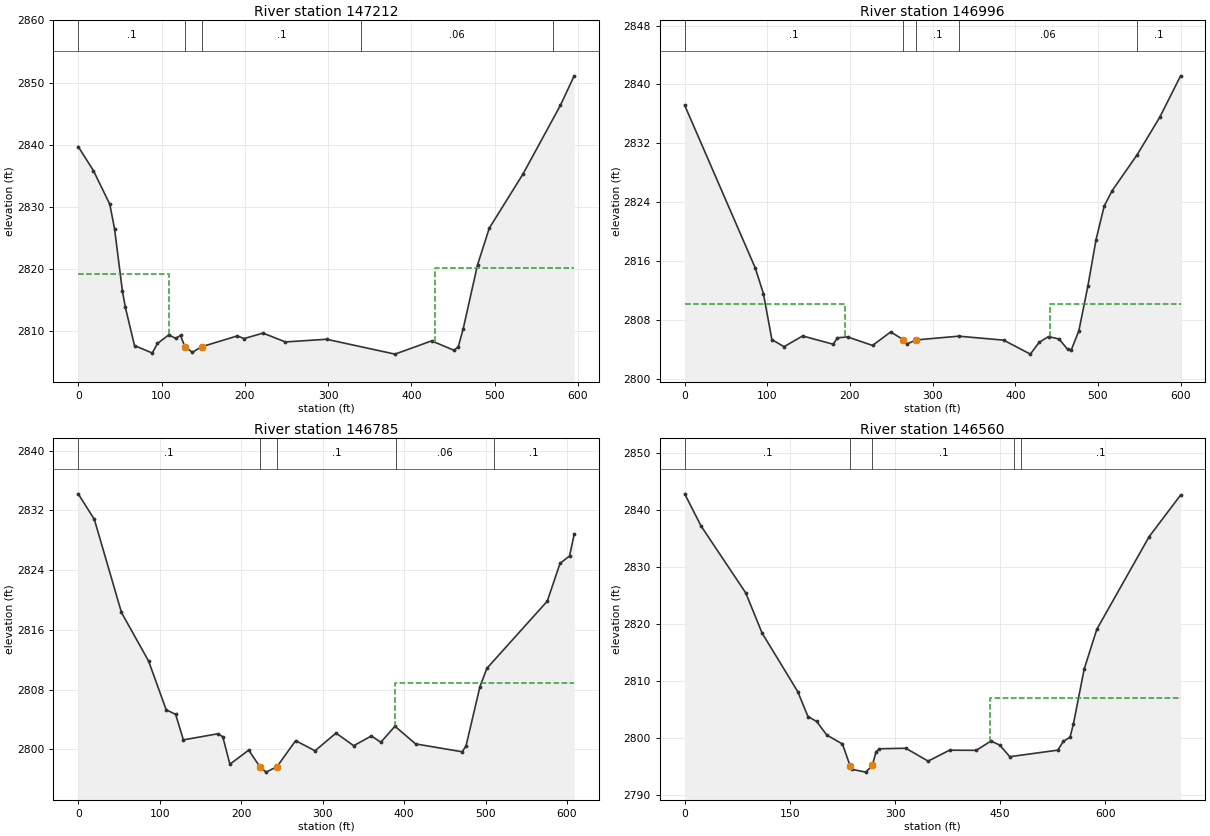
Type RM Length L Ch R = 1 ,147212  ,219.6,215.2,211.7
XS GIS Cut Line= 2
2304904.52255204467811.8872208162304496.92090381468245.862917471
#Sta/Elev= 30
       0 2839.71    18.2 2835.86    37.9 2830.45    43.6 2826.51    53.1 2816.46
    56.6 2813.87    67.6 2807.71    88.9 2806.52    95.1 2808.05   108.7 2809.43
     117 2808.88   122.8 2809.34     128 2807.56     137 2806.64   148.3 2807.53
   190.8 2809.26   199.3 2808.85   221.9 2809.72   248.7  2808.3   298.1 2808.73
   380.3 2806.34   424.3 2808.47   451.1 2806.96   456.2 2807.49   462.1 2810.36
   479.4 2820.69   493.5 2826.59   534.1 2835.33   578.9 2846.35   595.4 2851.09
#Mann= 5 ,-1,0
       0      .1       0     128    .045       0   148.3      .1       0
     340     .06       0     570      .1       0
#XS Ineff= 2 , 0
          108.85 2819.22  427.94          2820.2
Permanent Ineff=
       F       F
Bank Sta=128,148.3
XS Rating Curve= 0 ,0
Exp/Cntr(USF)=0,0
Exp/Cntr=0.3,0.1

Type RM Length L Ch R = 1 ,146996  ,209.4,211.6,208
XS GIS Cut Line= 2
2304766.96359212467680.4210720242304411.16595338468163.538454032
#Sta/Elev= 30
       0 2837.17    85.4 2815.05    95.3 2811.54   105.5 2805.32   120.2 2804.35
   142.7 2805.81   179.8 2804.68   184.7 2805.56   197.1 2805.68   227.3 2804.52
   249.3 2806.36   264.2 2805.32   269.2 2804.73     280 2805.27   331.5 2805.78
   385.9 2805.24   418.2 2803.34   428.8 2804.94   440.2 2805.73     453 2805.39
   463.4 2803.97   467.9 2803.96   476.9 2806.52   487.8 2812.59   497.7 2818.91
   507.6 2823.49   517.3 2825.58   547.4 2830.44   574.8 2835.55599.9953 2841.17
#Mann= 5 ,-1,0
       0      .1       0   264.2    .045       0     280      .1       0
   331.5     .06       0   547.4      .1       0
#XS Ineff= 2 , 0
          194.32  2810.2  442.39         2810.11
Permanent Ineff=
       F       F
Bank Sta=264.2,280
XS Rating Curve= 0 ,0
Exp/Cntr(USF)=0,0
Exp/Cntr=0.3,0.1

Type RM Length L Ch R = 1 ,146785  ,222,225.2,219.4
XS GIS Cut Line= 2
 2304584.6895261467600.4798068922304256.06360342468112.933197268
#Sta/Elev= 30
       0 2834.23    19.8 2830.81    53.1 2818.33    86.4 2811.82     108 2805.29
   119.6 2804.68   129.1 2801.26   171.9 2802.09   177.5 2801.66   186.2    2798
   209.3 2799.89   223.3 2797.61   230.7 2796.94   244.1 2797.68   266.9 2801.16
   290.7  2799.8   316.5 2802.17   338.2 2800.48   359.9 2801.79   371.5 2800.94
   388.8 2803.09   414.2 2800.72   471.3 2799.67     476 2800.42   493.1 2808.38
   501.7 2810.85   575.8 2819.85   591.5 2824.92   603.1 2825.89   608.8  2828.8
#Mann= 5 ,-1,0
       0      .1       0   223.3    .045       0   244.1      .1       0
     390     .06       0     510      .1       0
#XS Ineff= 2 , 0
                          389.24         2808.87
Permanent Ineff=
       F       F
Bank Sta=223.3,244.1
XS Rating Curve= 0 ,0
Exp/Cntr(USF)=0,0
Exp/Cntr=0.3,0.1

Type RM Length L Ch R = 1 ,146560  ,288.4,296.3,302.8
XS GIS Cut Line= 2
2304440.14653502467436.6934087112304054.07111131468029.274291608
#Sta/Elev= 30
       0 2842.77    23.5 2837.11    87.1 2825.42   110.4 2818.39   161.2 2808.15
   175.8 2803.78   188.2 2802.91   202.7 2800.53     225 2798.97  235.82 2795.18
   239.3 2794.51   258.4 2794.04  267.61 2795.21   272.7 2797.53   277.5 2798.13
   315.4 2798.22   347.2 2795.97   377.7 2797.88   415.9 2797.86   436.8 2799.48
   449.3 2798.78   463.7 2796.74   532.2 2797.89     540 2799.42   549.6 2800.16
   554.4 2802.47   569.8  2812.1   587.8 2819.06   662.3 2835.25   707.3 2842.56
#Mann= 5 ,-1,0
       0      .1       0  235.82    .045       0  267.61      .1       0
     470     .06       0     480      .1       0
#XS Ineff= 2 , 0
                          434.93         2806.96
Permanent Ineff=
       F       F
Bank Sta=235.82,267.61
XS Rating Curve= 0 ,0
Exp/Cntr(USF)=0,0
Exp/Cntr=0.3,0.1