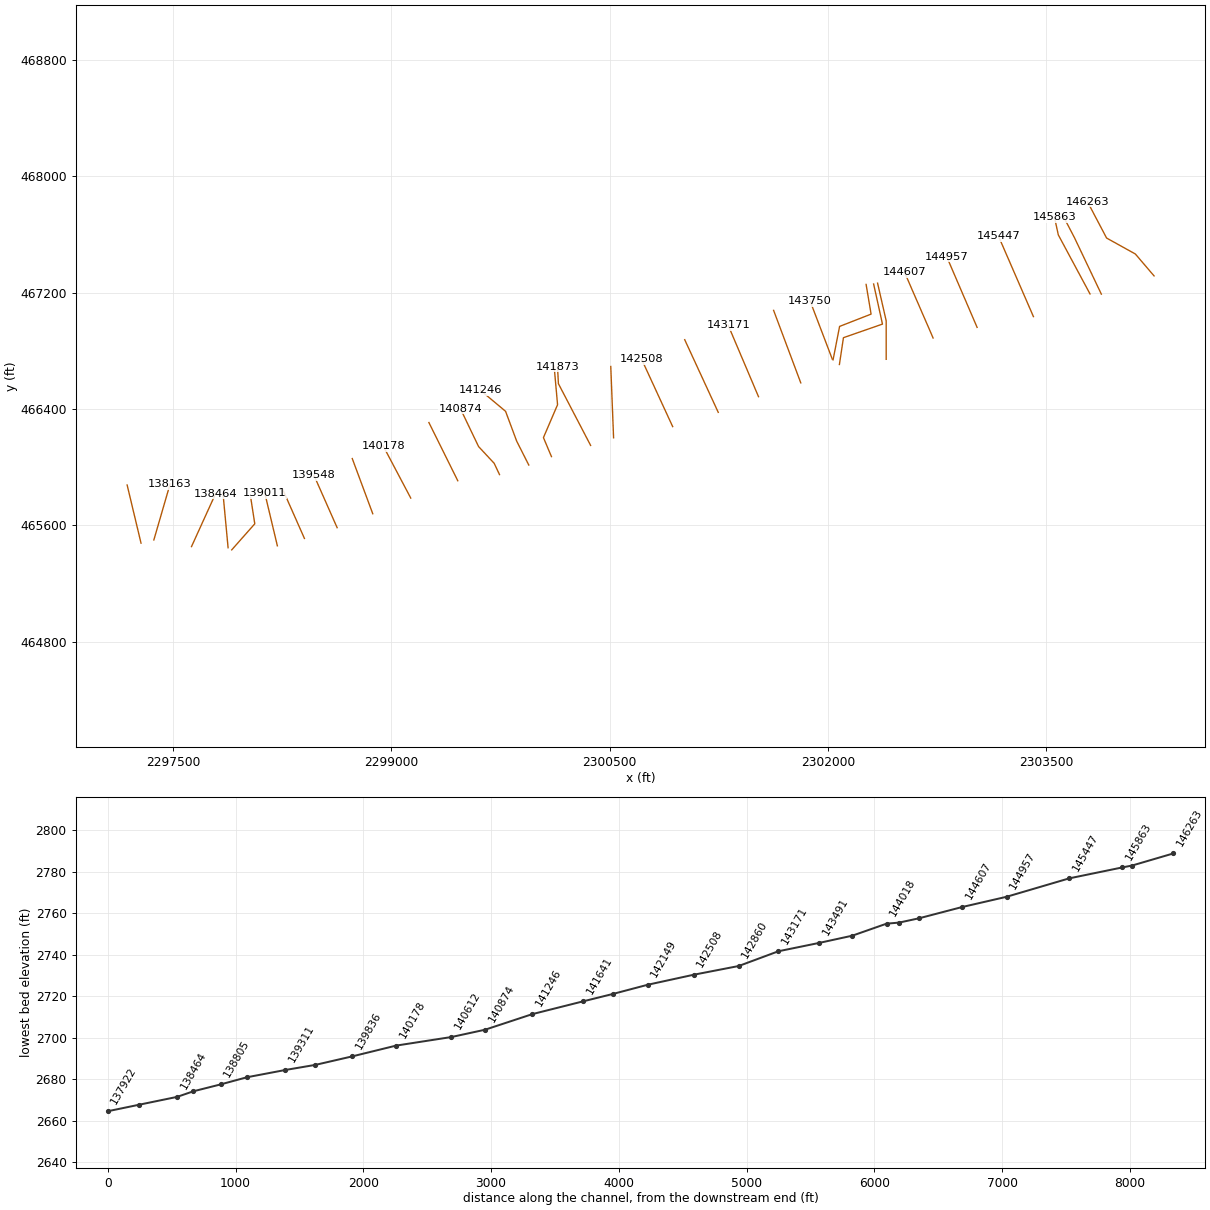
HEC-RAS study KNAPPCK.prj: KNAPPCK

--- KNAPPCK.g01 (geometry) --- (continued)

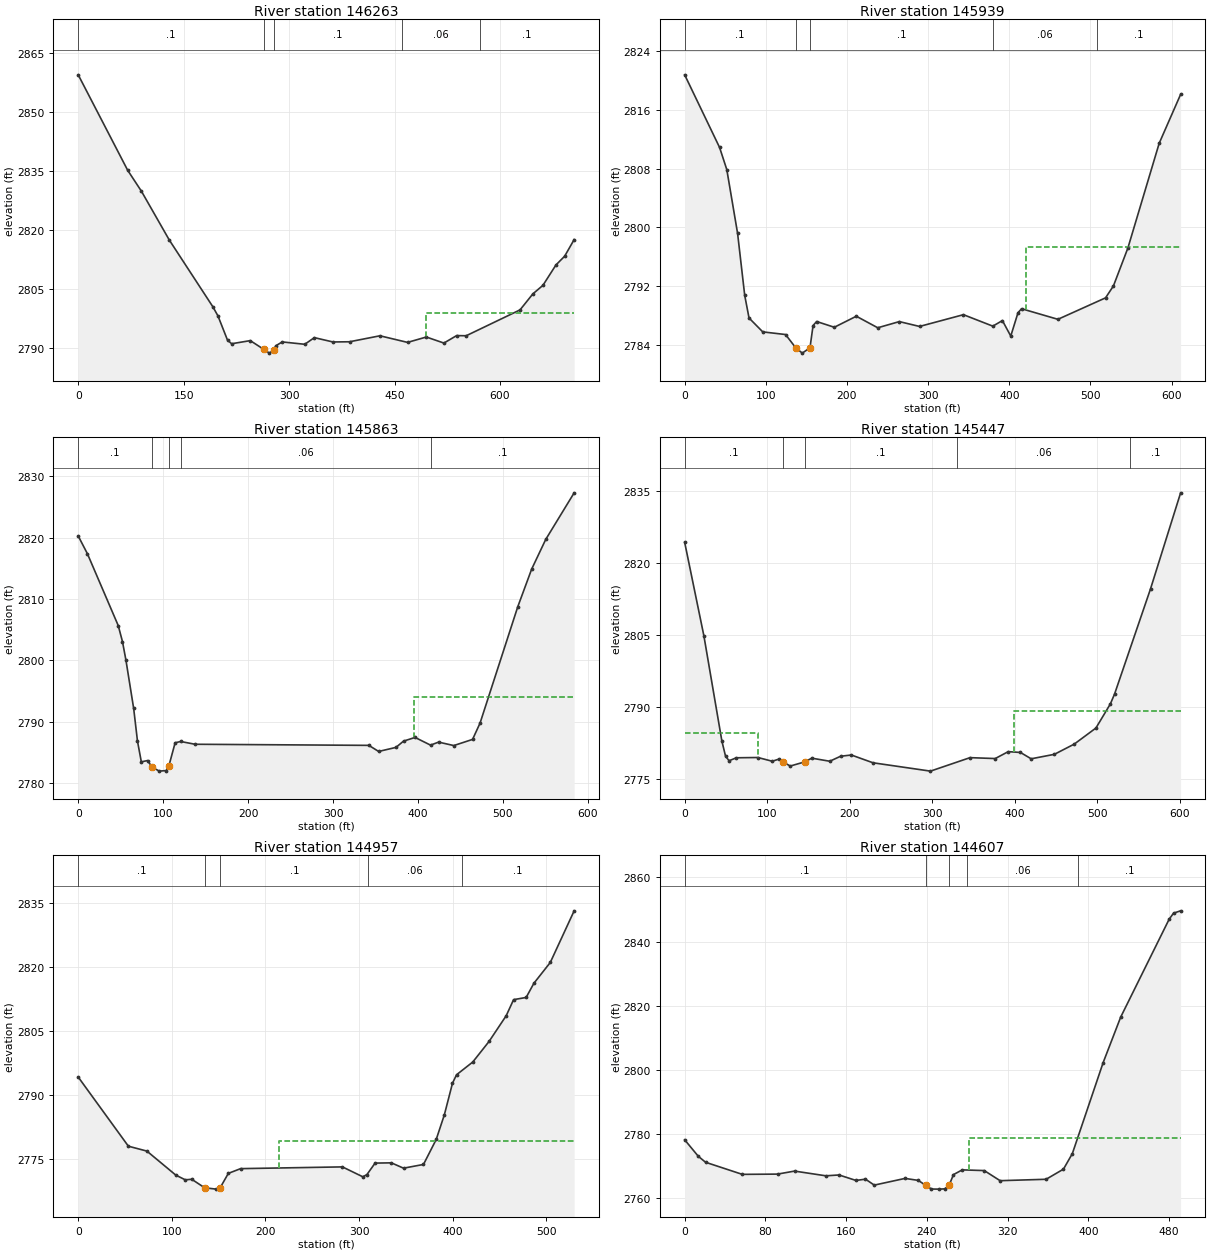
Type RM Length L Ch R = 1 ,146263  ,335,324.6,313.1
XS GIS Cut Line= 4
2304241.32187263467315.5968640782304112.62833813 467466.42388448
2303915.15839953467576.0286083832303784.12260959467825.111087851
#Sta/Elev= 30
       0 2859.55    70.4 2835.26    89.9 2829.95   129.6 2817.52   191.4 2800.59
   198.8 2798.23   212.4 2792.06   218.3 2791.14   244.8 2791.93   264.3 2789.68
     272 2788.75   278.1 2789.54   281.1 2790.62   290.3  2791.6   322.3    2791
     336 2792.69   362.4 2791.59     386 2791.64   429.3 2793.16   468.6 2791.48
   495.3 2792.85   520.3 2791.31   538.4 2793.21     552 2793.17   628.6 2799.75
   646.9 2803.83   661.2    2806   679.7 2811.18   692.1 2813.41   705.6 2817.64
#Mann= 5 ,-1,0
       0      .1       0   264.3    .045       0   278.1      .1       0
  461.26     .06       0  571.26      .1       0
#XS Ineff= 2 , 0
                          494.87         2798.99
Permanent Ineff=
       F       F
Bank Sta=264.3,278.1
XS Rating Curve= 0 ,0
Exp/Cntr(USF)=0,0
Exp/Cntr=0.3,0.1

Type RM Length L Ch R = 1 ,145939  ,75.5,75.3,76.1
XS GIS Cut Line= 3
 2303879.0274753467190.3362153912303694.93118228 467577.35654758
2303610.60460307467739.234408883
#Sta/Elev= 30
       0 2820.75      43 2810.87    51.9 2807.86    65.2 2799.18      74 2790.73
    79.3 2787.67    96.2 2785.78   124.3 2785.42   136.72783.637   144.9 2782.89
   154.4 2783.62   158.2 2786.64   162.6 2787.19   184.4 2786.41   211.5 2787.91
   237.9 2786.34   264.5 2787.18   289.4 2786.52   343.5 2788.12   379.7 2786.56
   391.5 2787.32   401.8 2785.21   410.7 2788.38   415.1 2788.93   459.9 2787.49
   518.6 2790.41   528.3 2792.03   546.1 2797.18   584.7 2811.44   611.1 2818.09
#Mann= 5 ,-1,0
       0      .1       0   136.7    .045       0   154.4      .1       0
     380     .06       0  508.57      .1       0
#XS Ineff= 2 , 0
                             420         2797.26
Permanent Ineff=
       F       F
Bank Sta=136.7,154.4
XS Rating Curve= 0 ,0
Exp/Cntr(USF)=0,0
Exp/Cntr=0.3,0.1

Type RM Length L Ch R = 1 ,145863  ,418.2,416.2,415
XS GIS Cut Line= 3
2303801.20703434467191.672856623 2303583.3449765467597.767732433
2303557.20152956467718.027588359
#Sta/Elev= 30
       0 2820.25    10.8 2817.37    47.1 2805.68    52.1 2803.08    56.2 2800.04
    65.3 2792.19    69.8 2786.86    74.3 2783.51    81.6 2783.72    86.8  2782.7
    95.3    2782   103.7 2782.09  106.65  2782.8   114.1 2786.61   120.6 2786.82
   137.6 2786.37   342.2 2786.19   353.7  2785.2   374.1 2785.86     383 2786.88
   396.6 2787.48   414.8 2786.23   424.3 2786.72   442.2 2786.16   464.3 2787.16
   473.1 2789.81   517.5 2808.73   533.9 2814.87   550.4 2819.68   583.9 2827.27
#Mann= 5 ,-1,0
       0      .1       0    86.8    .045       0  106.65      .1       0
   120.6     .06       0   414.8      .1       0
#XS Ineff= 2 , 0
                          395.15         2794.01
Permanent Ineff=
       F       F
Bank Sta=86.8,106.65
XS Rating Curve= 0 ,0
Exp/Cntr(USF)=0,0
Exp/Cntr=0.3,0.1

Type RM Length L Ch R = 1 ,145447  ,489.8,490.4,486.8
XS GIS Cut Line= 2
2303412.41200821467035.7860229482303172.95045056467587.373335056
#Sta/Elev= 30
       0 2824.39    23.3 2804.91    45.1 2782.99    49.5 2779.87    53.8 2778.88
    62.6  2779.5    88.7 2779.56   106.2 2778.78   114.9 2779.26     1192778.666
     128 2777.78   145.4 2778.64   154.1 2779.42   175.9 2778.78     189 2779.82
   202.1 2780.08   228.3 2778.46     298 2776.72     346 2779.53   376.5 2779.34
   392.3 2780.78   407.1 2780.61   420.1 2779.29   448.2 2780.22   472.3 2782.35
   498.6  2785.7   516.1 2790.72   521.2 2792.78   564.8  2814.7   601.3 2834.72
#Mann= 5 ,-1,0
       0      .1       0     119    .045       0   145.4      .1       0
     330     .06       0     540      .1       0
#XS Ineff= 2 , 0
           88.34 2784.69   398.7         2789.35
Permanent Ineff=
       F       F
Bank Sta=119,145.4
XS Rating Curve= 0 ,0
Exp/Cntr(USF)=0,0
Exp/Cntr=0.3,0.1

Type RM Length L Ch R = 1 ,144957  ,351.3,349.5,354.9
XS GIS Cut Line= 2
2303025.31363892466961.7467429832302816.23530261 467448.65077752
#Sta/Elev= 30
       0  2794.1    53.6  2777.9    73.4 2776.75   104.3 2771.12   114.4 2770.02
   121.3 2770.15   135.12768.156   147.4 2767.84   151.7 2768.17   160.4 2771.53
   173.5 2772.64   282.3 2773.05   304.1 2770.73   308.5 2771.25   317.2 2773.94
   334.6    2774   347.6 2772.75   368.9 2773.62   382.5 2779.47   391.2 2785.24
   399.9 2792.65   404.2 2794.63   421.6 2797.63     439 2802.45   457.3 2808.47
   465.2 2812.24   478.6 2812.75   486.9 2816.08   504.4 2820.95   529.9 2833.05
#Mann= 5 ,-1,0
       0      .1       0   135.1    .045       0   151.7      .1       0
     310     .06       0     410      .1       0
#XS Ineff= 2 , 0
                          214.99          2779.2
Permanent Ineff=
       F       F
Bank Sta=135.1,151.7
XS Rating Curve= 0 ,0
Exp/Cntr(USF)=0,0
Exp/Cntr=0.3,0.1

Type RM Length L Ch R = 1 ,144607  ,344.8,334.2,320.8
XS GIS Cut Line= 2
2302723.06039257466888.8265587032302527.22997441467339.654482313
#Sta/Elev= 30
       0 2778.25    13.5 2773.11    20.7 2771.25    57.1 2767.48      92 2767.56
   108.9  2768.5   139.9 2767.03     153 2767.29   169.7 2765.59   179.2 2765.98
   187.9 2764.13   218.4 2766.22   231.5  2765.6   238.9 2764.06   244.6 2762.91
   251.8 2762.88   257.7 2762.96     262 2764.03   266.4 2767.41   275.1 2768.88
   296.9 2768.66   312.6 2765.51   358.2 2765.95   375.4 2769.11   384.2 2773.95
   414.7 2802.28   432.1 2816.47   480.1 2846.96   484.5 2848.87   491.5 2849.59
#Mann= 5 ,-1,0
       0      .1       0   238.9    .045       0     262      .1       0
     280     .06       0     390      .1       0
#XS Ineff= 2 , 0
                          281.97         2778.72
Permanent Ineff=
       F       F
Bank Sta=238.9,262
XS Rating Curve= 0 ,0
Exp/Cntr(USF)=0,0
Exp/Cntr=0.3,0.1

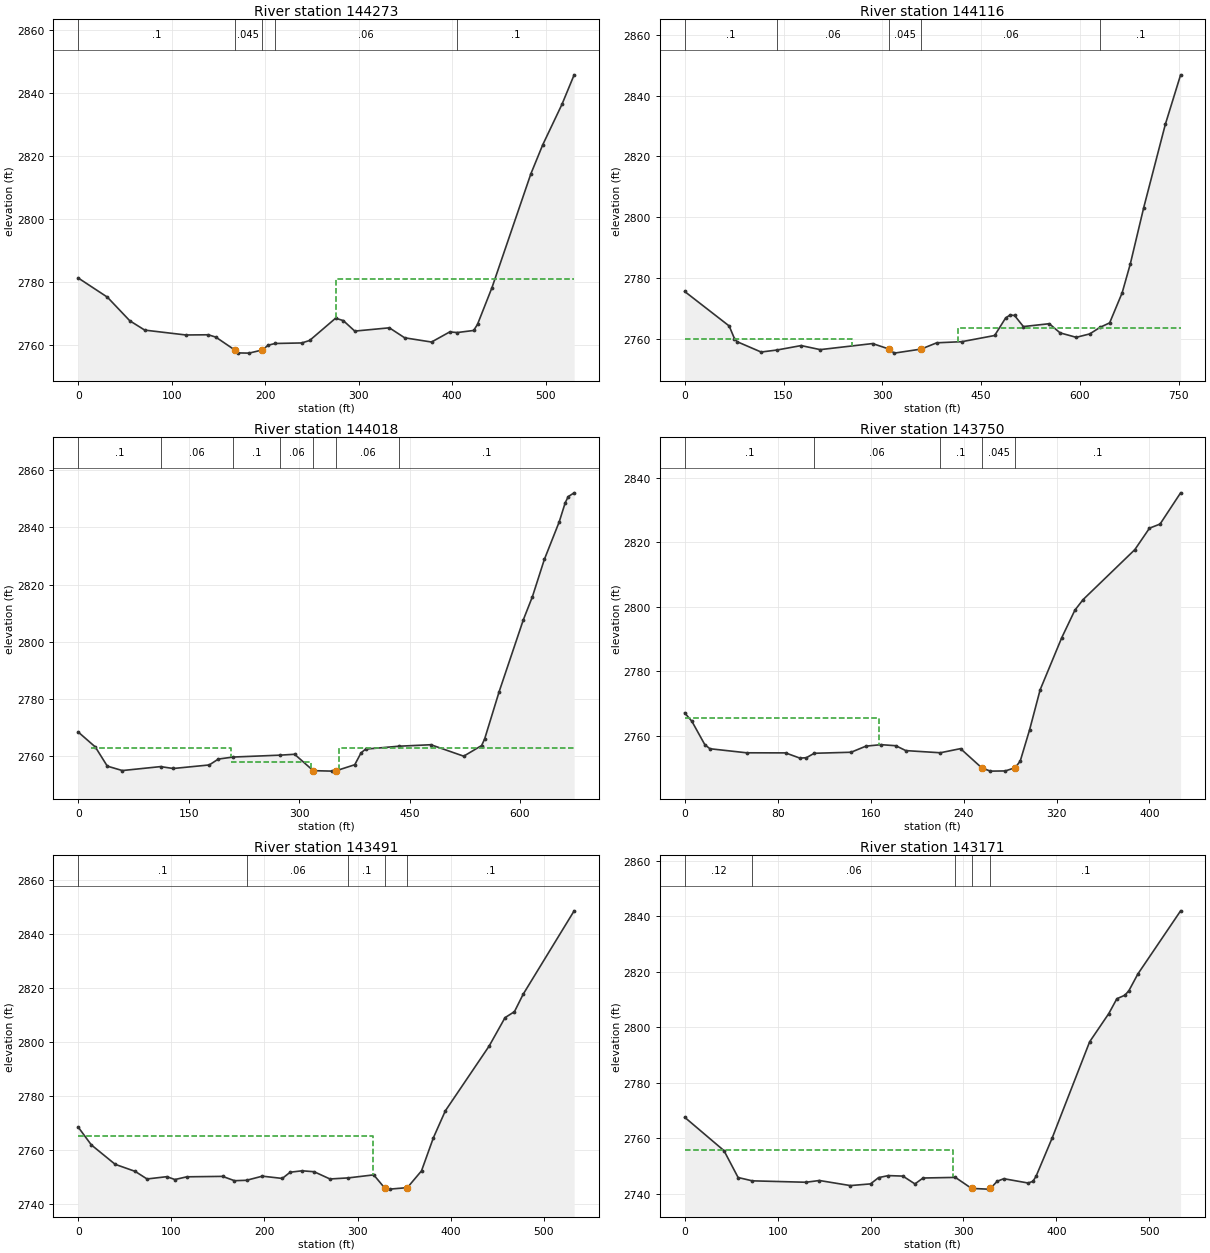
Type RM Length L Ch R = 1 ,144273  ,193,157.1,113.8
BEGIN DESCRIPTION:
structure xs 4
END DESCRIPTION:
XS GIS Cut Line= 3
2302400.65354212466742.0178122952302400.65354212 467007.06679054
2302341.52723159467265.999253902
#Sta/Elev= 30
       0 2781.34    31.2 2775.26    55.2 2767.76    71.2  2764.8   115.2 2763.26
   139.2 2763.32   147.2 2762.58   167.32758.542   171.2 2757.57   182.7  2757.5
   196.92758.499   203.2 2760.01   210.7 2760.56   239.2 2760.73   247.6 2761.52
   275.4 2768.58   283.6 2767.82   295.9 2764.49   332.9 2765.53   349.3 2762.36
     378 2761.02   397.5 2764.23   405.5 2764.03   423.1 2764.69   427.2 2766.63
   442.7  2778.3   484.3 2814.39     497  2823.6   517.5 2836.39   530.6 2845.79
#Mann= 5 ,-1,0
       0      .1       0   167.3    .045       0   196.9      .1       0
   210.7     .06       0   405.5      .1       0
#XS Ineff= 2 , 0
                          275.83         2781.01
Permanent Ineff=
       F       F
Bank Sta=167.3,196.9
XS Rating Curve= 0 ,0
Exp/Cntr(USF)=0,0
Exp/Cntr=0.5,0.3

Type RM Length L Ch R = 1 ,144116  ,92.5,98.3,109.4
BEGIN DESCRIPTION:
structure xs 3
END DESCRIPTION:
XS GIS Cut Line= 4
2302079.29185019466706.4400840612302107.06082775466890.853007771
2302375.18845182 466984.272578412302314.43107066 467259.82157387
#Sta/Elev= 30
       0 2775.66    67.5 2764.33    75.6 2760.15    79.6 2759.16     116 2755.77
   140.3 2756.44   176.7 2757.89   205.7 2756.56   285.1 2758.55   310.5 2756.72
     318 2755.41   358.8 2756.74   382.5  2758.8   420.6 2759.17   470.4  2761.2
   487.1 2766.98   493.9 2767.93   500.6 2767.77     514 2764.13   553.3 2765.07
   569.7 2762.06   594.2  2760.6   614.7 2761.72   630.6 2763.91   644.9 2765.35
   663.9 2775.23   676.2 2784.66   696.6 2803.19   729.4 2830.54   752.6  2846.8
#Mann= 5 ,-1,0
       0      .1       0   140.3     .06       0   310.5    .045       0
   358.8     .06       0   630.6      .1       0
#XS Ineff= 2 , 0
           254.5 2759.94   414.8          2763.5
Permanent Ineff=
       F       F
Bank Sta=310.5,358.8
XS Rating Curve= 0 ,0
Exp/Cntr(USF)=0,0
Exp/Cntr=0.5,0.3

Type RM Length L Ch R = 1 ,144018  ,228.1,268.1,306.8
BEGIN DESCRIPTION:
structure xs 2
END DESCRIPTION:
XS GIS Cut Line= 4
2302035.73207003466738.4294568972302080.55592993 466968.32886295
2302296.96842067467052.9610405422302262.71593732467257.150695705
#Sta/Elev= 30
       0 2768.55    23.2 2763.34    39.5 2756.64    59.9 2755.09   111.9 2756.47
   129.1 2755.81     178 2757.05   190.4 2759.11   210.5 2759.81   274.4 2760.47
   293.9 2760.78   319.22755.058   344.9 2754.89   350.52755.046   375.6 2757.12
   384.1 2761.25   390.3 2762.57   435.3 2763.59     479 2764.11   523.6 2760.11
   547.9 2763.83     552 2766.11   571.7 2782.63   604.7 2807.84   616.9 2815.82
   633.1 2828.82   653.4 2842.02   661.5 2848.67   665.6 2850.79   673.6  2852.1
#Mann= 7 ,-1,0
       0      .1       0   111.9     .06       0   210.5      .1       0
   274.4     .06       0   319.2    .045       0   350.5     .06       0
   435.3      .1       0
#XS Ineff= 3 ,-1
   17.08  207.42 2763.08  207.42  315.95 2758.18     354   673.6    2763
Permanent Ineff=
       F       F       F
Bank Sta=319.2,350.5
XS Rating Curve= 0 ,0
Exp/Cntr(USF)=0,0
Exp/Cntr=0.5,0.3

Type RM Length L Ch R = 1 ,143750  ,258.6,258.5,258.4
BEGIN DESCRIPTION:
structure xs 1
END DESCRIPTION:
XS GIS Cut Line= 2
2302030.31895436466743.3634455692301878.32355953 467142.13982753
#Sta/Elev= 30
       0 2767.14     6.2 2764.54    17.3 2757.32    21.7 2756.04    53.3 2754.78
    86.8 2754.75    99.1 2753.14   104.7 2753.25   111.5 2754.63   143.2 2754.95
     156 2756.84   168.9  2757.3   181.7 2756.97   190.3 2755.46     220 2754.79
   237.4 2756.07   255.82750.071   263.1  2749.1   275.9 2749.16   284.5 2750.17
   288.8 2752.25   296.9 2761.99   305.9  2774.3   324.5 2790.45   335.8 2798.97
   342.9 2802.26   387.4 2817.73     400 2824.38   409.1 2825.65   426.8 2835.33
#Mann= 5 ,-1,0
       0      .1       0   111.5     .06       0     220      .1       0
   255.8    .045       0   284.5      .1       0
#XS Ineff= 2 , 0
          167.61 2765.63
Permanent Ineff=
       F       F
Bank Sta=255.8,284.5
XS Rating Curve= 0 ,0
Exp/Cntr(USF)=0,0
Exp/Cntr=0.3,0.1

Type RM Length L Ch R = 1 ,143491  ,319.2,320.1,320.9
XS GIS Cut Line= 2
2301813.79967851  466579.98333392301627.18480944467078.723957423
#Sta/Elev= 30
       0 2768.58    14.1    2762    39.7 2754.81    61.1 2752.21    73.9 2749.39
    95.2 2750.24   103.8 2749.18   116.6 2750.19     155 2750.35   167.8 2748.75
   180.7  2748.9   197.7 2750.43   219.1 2749.59   227.6 2751.89   240.4 2752.42
   253.3 2752.07   270.3 2749.39     290 2749.79   317.3 2750.91   328.9 2746.11
   334.4 2745.63   353.4 2746.18   368.6 2752.39   381.4 2764.68   394.2 2774.62
   441.2 2798.59   458.3 2809.12   468.4 2811.33   477.7 2817.75   532.5 2848.66
#Mann= 5 ,-1,0
       0      .1       0   180.7     .06       0     290      .1       0
   328.9    .045       0   353.4      .1       0
#XS Ineff= 2 , 0
           316.1 2765.18
Permanent Ineff=
       F       F
Bank Sta=328.9,353.4
XS Rating Curve= 0 ,0
Exp/Cntr(USF)=0,0
Exp/Cntr=0.3,0.1

Type RM Length L Ch R = 1 ,143171  ,309.9,310.9,311.2
XS GIS Cut Line= 2
2301523.44598892466485.0209465192301315.05905498 466976.33349829
#Sta/Elev= 30
       0 2767.51    42.3 2755.47    57.5 2745.78    72.8 2744.58   130.5 2744.07
     145  2744.7   178.3 2742.87     200 2743.48   208.7 2745.75   219.2 2746.47
   234.8 2746.29   247.8 2743.47   256.5  2745.6   291.3 2745.82   308.7 2741.85
   325.9 2741.59   329.1 2741.84   336.2  2744.4   343.4 2745.35   369.5  2743.8
   374.8  2744.4   378.2 2746.27   395.6 2760.14   435.8 2794.73   456.4 2804.91
   465.1 2810.26   473.8 2811.54   478.1  2813.2   487.7 2819.19   533.7 2841.96
#Mann= 5 ,-1,0
       0     .12       0    72.8     .06       0   291.3      .1       0
   308.7    .045       0   329.1      .1       0
#XS Ineff= 2 , 0
          289.06 2755.53
Permanent Ineff=
       F       F
Bank Sta=308.7,329.1
XS Rating Curve= 0 ,0
Exp/Cntr(USF)=0,0
Exp/Cntr=0.3,0.1

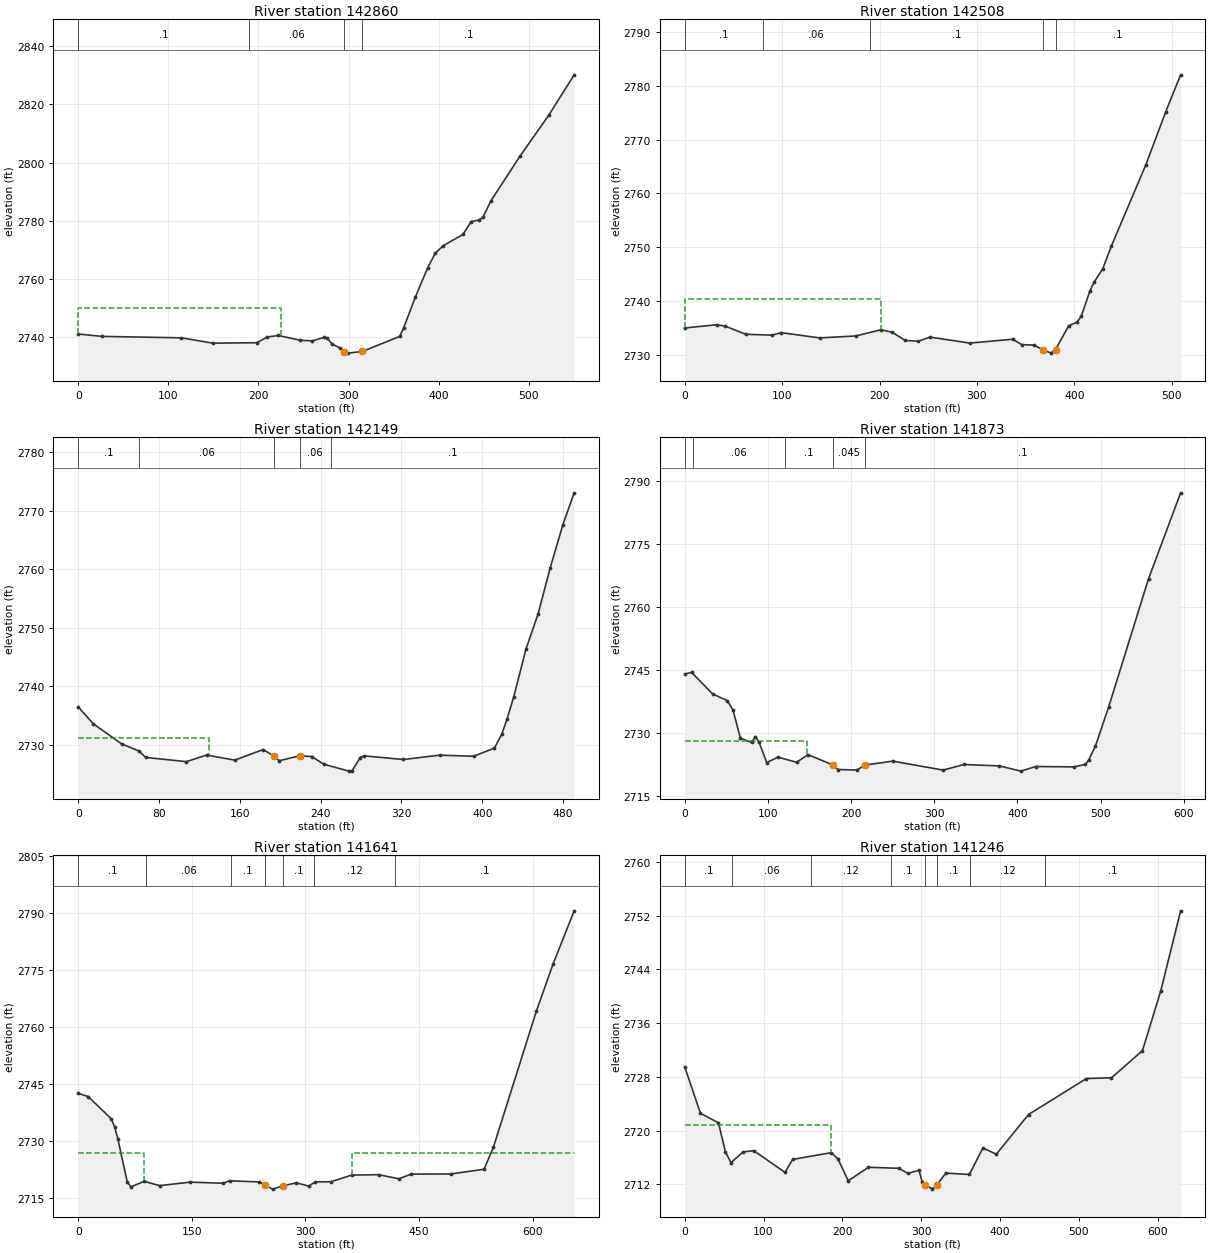
Type RM Length L Ch R = 1 ,142860  ,351.7,352,348.9
XS GIS Cut Line= 2
 2301246.7939994466377.2306180762301016.34587828466877.033685974
#Sta/Elev= 30
       0 2741.06    26.4 2740.24   114.5 2739.74   149.6 2737.91   198.2 2738.06
   209.9 2740.02     222 2740.55   246.6 2738.91   259.8  2738.7   273.3 2739.93
   276.3 2739.67   281.8 2737.61   290.7 2736.22   294.52735.003   299.5 2734.48
   315.5 2735.06   356.7 2740.22   361.1 2743.09   374.3 2753.86   387.8 2763.78
   396.4 2768.93   405.2 2771.43     427 2775.29   436.1 2779.74   444.8 2780.24
   449.2 2781.21     458 2786.85   490.3 2802.22   522.1 2816.23   550.4 2830.18
#Mann= 4 ,-1,0
       0      .1       0     190     .06       0   294.5    .045       0
   315.5      .1       0
#XS Ineff= 2 , 0
          225.13 2749.85
Permanent Ineff=
       F       F
Bank Sta=294.5,315.5
XS Rating Curve= 0 ,0
Exp/Cntr(USF)=0,0
Exp/Cntr=0.3,0.1

Type RM Length L Ch R = 1 ,142508  ,366.3,359.4,344.5
XS GIS Cut Line= 2
2300933.57202176466279.417792572 2300720.5338084466741.826317693
#Sta/Elev= 30
       0 2734.95    32.8 2735.56    41.6 2735.31    62.7 2733.78    89.8 2733.63
    98.9 2734.09   138.5 2733.11   175.4 2733.47   201.4 2734.62   213.1 2734.15
   226.5 2732.63   239.8  2732.5   251.9 2733.26   292.6 2732.15   336.7 2732.86
   346.1 2731.86   358.2 2731.78   368.2 2730.87   376.2 2730.28   380.7 2730.95
   394.3 2735.39   402.7 2736.03   407.1 2737.13   415.9 2741.81   420.3 2743.48
   429.1 2745.95   437.9 2750.14   473.2 2765.21   493.8 2775.15   509.1 2782.03
#Mann= 5 ,-1,0
       0      .1       0      80     .06       0     190      .1       0
   368.2    .045       0   380.7      .1       0
#XS Ineff= 2 , 0
           201.8  2740.4
Permanent Ineff=
       F       F
Bank Sta=368.2,380.7
XS Rating Curve= 0 ,0
Exp/Cntr(USF)=0,0
Exp/Cntr=0.3,0.1

Type RM Length L Ch R = 1 ,142149  ,264.5,275.6,285
XS GIS Cut Line= 2
2300527.64339506466202.2946564182300508.32132455 466692.77798485
#Sta/Elev= 30
       0 2736.45    14.9 2733.56    42.9 2730.13      60 2728.91    66.9  2727.8
     107 2727.08     127 2728.21     155 2727.34     183 2729.15   193.82728.022
     199 2727.24   219.22728.083   231.1 2727.96   243.1 2726.64     268 2725.46
   271.1 2725.52   279.1 2727.79   283.1 2728.07   321.9 2727.45   357.8 2728.19
   391.3    2728     412  2729.4   419.2 2731.76   424.5 2734.38   431.2 2738.22
   443.2 2746.33   455.2 2752.33   467.2 2760.23   479.8 2767.63   490.9 2773.05
#Mann= 5 ,-1,0
       0      .1       0      60     .06       0   193.8    .045       0
   219.2     .06       0     250      .1       0
#XS Ineff= 2 , 0
          129.12 2731.14
Permanent Ineff=
       F       F
Bank Sta=193.8,219.2
XS Rating Curve= 0 ,0
Exp/Cntr(USF)=0,0
Exp/Cntr=0.3,0.1

Type RM Length L Ch R = 1 ,141873  ,249.6,232.4,202.3
XS GIS Cut Line= 3
2300369.89400603466149.7753296912300148.42438313466574.757579042
2300142.43871764466691.478055976
#Sta/Elev= 30
       0 2744.09     8.3 2744.48    33.5 2739.38    51.2 2737.76      58 2735.58
      67 2728.82    80.5  2727.8      85 2729.22    89.5 2727.83    98.6 2723.01
   112.1  2724.3   134.6 2723.09   148.2  2724.9   178.7 2722.41   184.3 2721.36
   206.8 2721.25   217.3 2722.44   249.9 2723.36   310.6 2721.23   335.9 2722.56
   378.2 2722.22   404.1 2720.98   421.9 2722.08   468.4 2721.99   481.7  2722.6
   485.6 2723.64   493.7 2726.95   509.7  2736.3   557.5 2766.76   596.1 2787.23
#Mann= 5 ,-1,0
       0      .1       0      10     .06       0     120      .1       0
   178.7    .045       0   217.3      .1       0
#XS Ineff= 2 , 0
          147.55 2728.09
Permanent Ineff=
       F       F
Bank Sta=178.7,217.3
XS Rating Curve= 0 ,0
Exp/Cntr(USF)=0,0
Exp/Cntr=0.3,0.1

Type RM Length L Ch R = 1 ,141641  ,372.5,395.1,408.5
XS GIS Cut Line= 4
2300100.64719395466072.9652087772300045.71422817466203.780969534
 2300142.6882979466429.7005632362300118.90728804466695.750611082
#Sta/Elev= 30
       0 2742.63    13.2 2741.79    43.6 2735.95      48 2733.86    52.3 2730.68
    64.7  2719.4    69.6 2718.02      87 2719.48   107.5 2718.36   147.8 2719.27
   191.3 2718.98     200 2719.63   239.2 2719.32   246.52718.491   256.6 2717.43
   270.42718.324     288 2719.07   304.5 2718.24   313.2 2719.36   333.6 2719.36
     361 2721.12   396.9 2721.23   423.4 2720.15   439.4 2721.38   491.6 2721.42
   535.8 2722.66   548.1 2728.41   604.9 2764.27   626.9 2776.65   654.8 2790.68
#Mann= 7 ,-1,0
       0      .1       0      90     .06       0  201.88      .1       0
   246.5    .045       0   270.4      .1       0  311.88     .12       0
  417.73      .1       0
#XS Ineff= 2 , 0
           86.76 2727.07  361.24         2726.96
Permanent Ineff=
       F       F
Bank Sta=246.5,270.4
XS Rating Curve= 0 ,0
Exp/Cntr(USF)=0,0
Exp/Cntr=0.3,0.1

Type RM Length L Ch R = 1 ,141246  ,358.9,371.5,371.7
XS GIS Cut Line= 4
2299944.92405096466015.0250517172299861.81691728466179.351635894
2299785.45511264466384.4818879052299612.23446597466529.443492686
#Sta/Elev= 30
       0 2729.53      20 2722.59    42.8 2721.18    51.7 2716.86    58.7 2715.25
    74.1 2716.85    87.6 2717.03   127.2 2713.81   136.9 2715.73   186.1 2716.74
   194.6 2715.75   207.4 2712.55     233 2714.56   271.5 2714.41   283.3 2713.65
   297.1 2714.12   301.3 2712.34     305 2711.98   314.1 2711.31   319.72711.936
   331.2  2713.7     361 2713.49   378.2 2717.44   395.2  2716.5     436 2722.41
   509.5 2727.77   541.2 2727.87   580.5 2731.92   603.6 2740.76   628.9 2752.72
#Mann= 8 ,-1,0
       0      .1       0      60     .06       0     160     .12       0
  261.96      .1       0     305    .045       0   319.7      .1       0
  361.96     .12       0  456.78      .1       0
#XS Ineff= 2 , 0
          185.75  2720.8
Permanent Ineff=
       F       F
Bank Sta=305,319.7
XS Rating Curve= 0 ,0
Exp/Cntr(USF)=0,0
Exp/Cntr=0.3,0.1

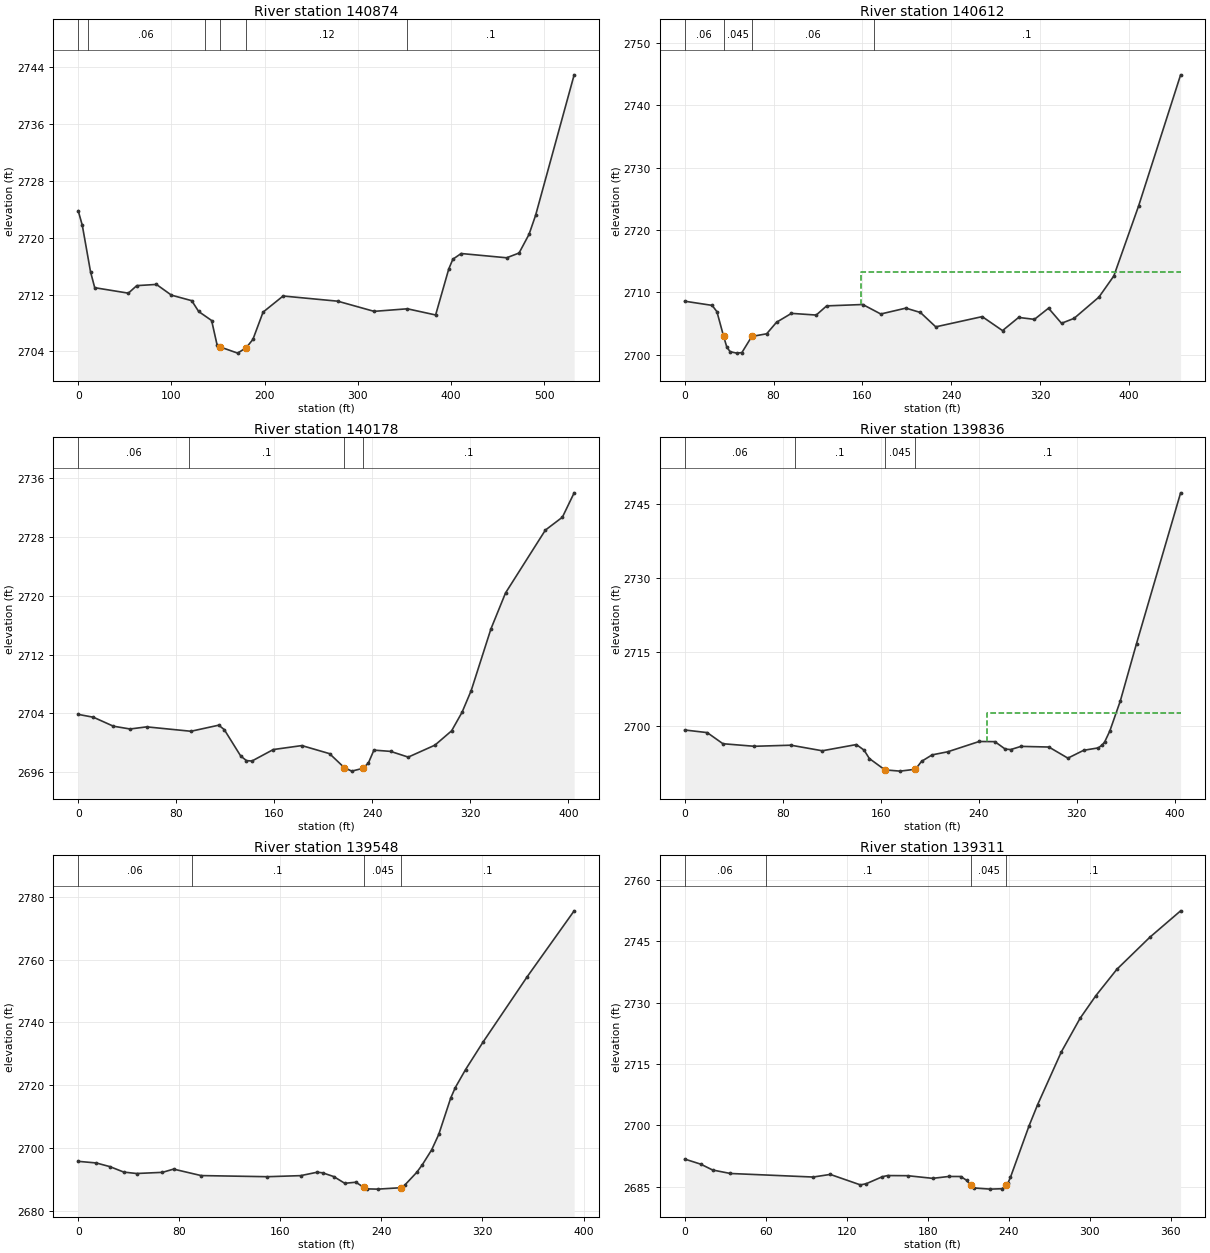
Type RM Length L Ch R = 1 ,140874  ,268.2,261.8,254.9
XS GIS Cut Line= 4
2299743.79892403 465949.202583792299707.29868439466026.693541475
2299600.03817053466141.9407638672299475.26126692466402.504297863
#Sta/Elev= 30
       0 2723.81     4.4 2721.75    13.2 2715.23    17.7 2712.98    53.8 2712.21
    62.8 2713.27    83.9 2713.44     100 2711.93   121.8 2711.15   129.2 2709.63
   143.1 2708.36   149.1 2704.85   152.62704.623     171 2703.77   180.2 2704.53
   187.4  2705.7   198.3 2709.54   219.8 2711.81   278.4 2711.08   317.4 2709.65
   353.1 2710.01   383.4 2709.14   397.5 2715.62   401.9 2716.99   410.8 2717.79
   459.6 2717.19   472.9 2717.86   483.6 2720.49   490.6 2723.15     532 2742.94
#Mann= 6 ,-1,0
       0      .1       0      10     .06       0  135.66     .12       0
   152.6    .045       0   180.2     .12       0   353.1      .1       0
Bank Sta=152.6,180.2
XS Rating Curve= 0 ,0
Exp/Cntr(USF)=0,0
Exp/Cntr=0.3,0.1

Type RM Length L Ch R = 1 ,140612  ,433.4,434.1,427.8
XS GIS Cut Line= 2
2299456.91172227465907.0665923772299258.73664008466307.086665696
#Sta/Elev= 30
       0 2708.59    24.7 2707.92      29 2706.92      35    2703    37.9 2701.25
    40.9  2700.5    46.9 2700.27    51.5 2700.36    60.4 2702.94    73.8 2703.37
    82.7 2705.22    96.1 2706.64   118.4 2706.37   127.8 2707.84   160.3 2708.06
   176.5 2706.54   199.1 2707.48   212.2 2706.78     226 2704.48   267.8 2706.12
   286.1 2703.88   300.6 2705.99   314.8 2705.68   327.5 2707.47   339.2 2705.05
   350.5 2705.84   372.9 2709.25   386.3 2712.64   408.6 2723.86   446.4 2744.86
#Mann= 4 ,-1,0
       0     .06       0      35    .045       0    60.4     .06       0
     170      .1       0
#XS Ineff= 2 , 0
                          158.59         2713.32
Permanent Ineff=
       F       F
Bank Sta=35,60.4
XS Rating Curve= 0 ,0
Exp/Cntr(USF)=0,0
Exp/Cntr=0.3,0.1

Type RM Length L Ch R = 1 ,140178  ,342.9,342.5,338.4
XS GIS Cut Line= 2
2299133.95973648465787.7945521672298944.95942661466145.610672796
#Sta/Elev= 30
       0 2703.85    12.4 2703.46    28.7 2702.24    42.3 2701.86    55.9 2702.15
      92 2701.55   114.7 2702.38   119.2 2701.77   132.6 2698.18   137.3 2697.55
   141.8  2697.5   159.2 2699.06   182.5  2699.6   205.1  2698.5   217.1  2696.6
   223.2 2696.12   232.3  2696.5   236.8 2697.23   241.3 2698.98   254.9 2698.81
   269.3 2698.03   291.1 2699.66   304.7 2701.61   313.2 2704.13   320.7  2707.1
   336.8  2715.5   348.7 2720.39   381.2 2728.95   395.1 2730.71   404.7 2734.03
#Mann= 4 ,-1,0
       0     .06       0      90      .1       0   217.1    .045       0
   232.3      .1       0
Bank Sta=217.1,232.3
XS Rating Curve= 0 ,0
Exp/Cntr(USF)=0,0
Exp/Cntr=0.3,0.1

Type RM Length L Ch R = 1 ,139836  ,286.7,287.9,291
XS GIS Cut Line= 2
2298872.91540039465679.9247869432298732.10470869466059.367812952
#Sta/Elev= 30
       0 2699.27    18.4 2698.74    31.2 2696.49    56.8 2695.97    86.7 2696.19
   112.3 2695.06   140.1 2696.32   146.4 2695.19   150.7 2693.49   163.4 2691.19
   175.8 2690.94   188.3 2691.32   193.3 2692.92   201.9 2694.23   214.7 2694.86
   240.3 2696.94   253.1 2696.91   261.6  2695.4   266.1 2695.31   274.4 2695.95
   297.2 2695.82   312.7 2693.57   325.6 2695.16   337.6 2695.65   340.7 2696.25
   342.7 2696.84   346.9 2699.05   355.5 2705.16   368.7 2716.76   404.7 2747.29
#Mann= 4 ,-1,0
       0     .06       0      90      .1       0   163.4    .045       0
   188.3      .1       0
#XS Ineff= 2 , 0
                          246.76         2702.74
Permanent Ineff=
       F       F
Bank Sta=163.4,188.3
XS Rating Curve= 0 ,0
Exp/Cntr(USF)=0,0
Exp/Cntr=0.3,0.1

Type RM Length L Ch R = 1 ,139548  ,236.7,237,236.6
XS GIS Cut Line= 2
2298628.06535024465584.1299414722298469.44521492  465943.2698705
#Sta/Elev= 30
       0 2695.71    14.3 2695.19      25 2694.03    36.1 2692.28    46.2 2691.83
    66.7  2692.2    75.5 2693.23    97.3 2691.17   149.8 2690.81   176.1 2691.15
   189.2 2692.24   193.5 2692.05   202.3 2690.85     211 2688.71   219.8 2689.05
   226.22687.375   228.5 2686.93   237.2 2686.85   255.5  2687.3   258.5 2688.13
   267.9 2692.16   272.3 2694.56   279.8 2699.37   285.4 2704.28   294.9  2715.9
   298.5 2719.21   306.6 2724.94   320.4 2733.68   355.3 2754.48   392.6 2775.56
#Mann= 4 ,-1,0
       0     .06       0      90      .1       0   226.2    .045       0
   255.5      .1       0
Bank Sta=226.2,255.5
XS Rating Curve= 0 ,0
Exp/Cntr(USF)=0,0
Exp/Cntr=0.3,0.1

Type RM Length L Ch R = 1 ,139311  ,303.6,299.8,289.2
XS GIS Cut Line= 2
2298403.40286413 465510.255392212298254.77155249465846.052059262
#Sta/Elev= 30
       0 2691.73    11.9 2690.48    20.7 2689.05    33.8  2688.2    95.1 2687.33
   107.8 2687.97   130.1 2685.41   134.4 2685.69   146.3  2687.4   150.2 2687.69
     165 2687.66   183.6 2687.01   195.6 2687.47   204.4 2687.46   208.8 2686.52
   211.82685.288   213.9 2684.66   226.3 2684.37     235 2684.47   238.1 2685.29
   239.4  2685.9   241.2 2687.25     255 2699.88   261.3 2705.03   278.8 2717.91
   292.7 2726.15   304.5 2731.75     320 2738.18   344.4 2746.02   367.2 2752.49
#Mann= 4 ,-1,0
       0     .06       0      60      .1       0   211.8    .045       0
   238.1      .1       0
Bank Sta=211.8,238.1
XS Rating Curve= 0 ,0
Exp/Cntr(USF)=0,0
Exp/Cntr=0.3,0.1

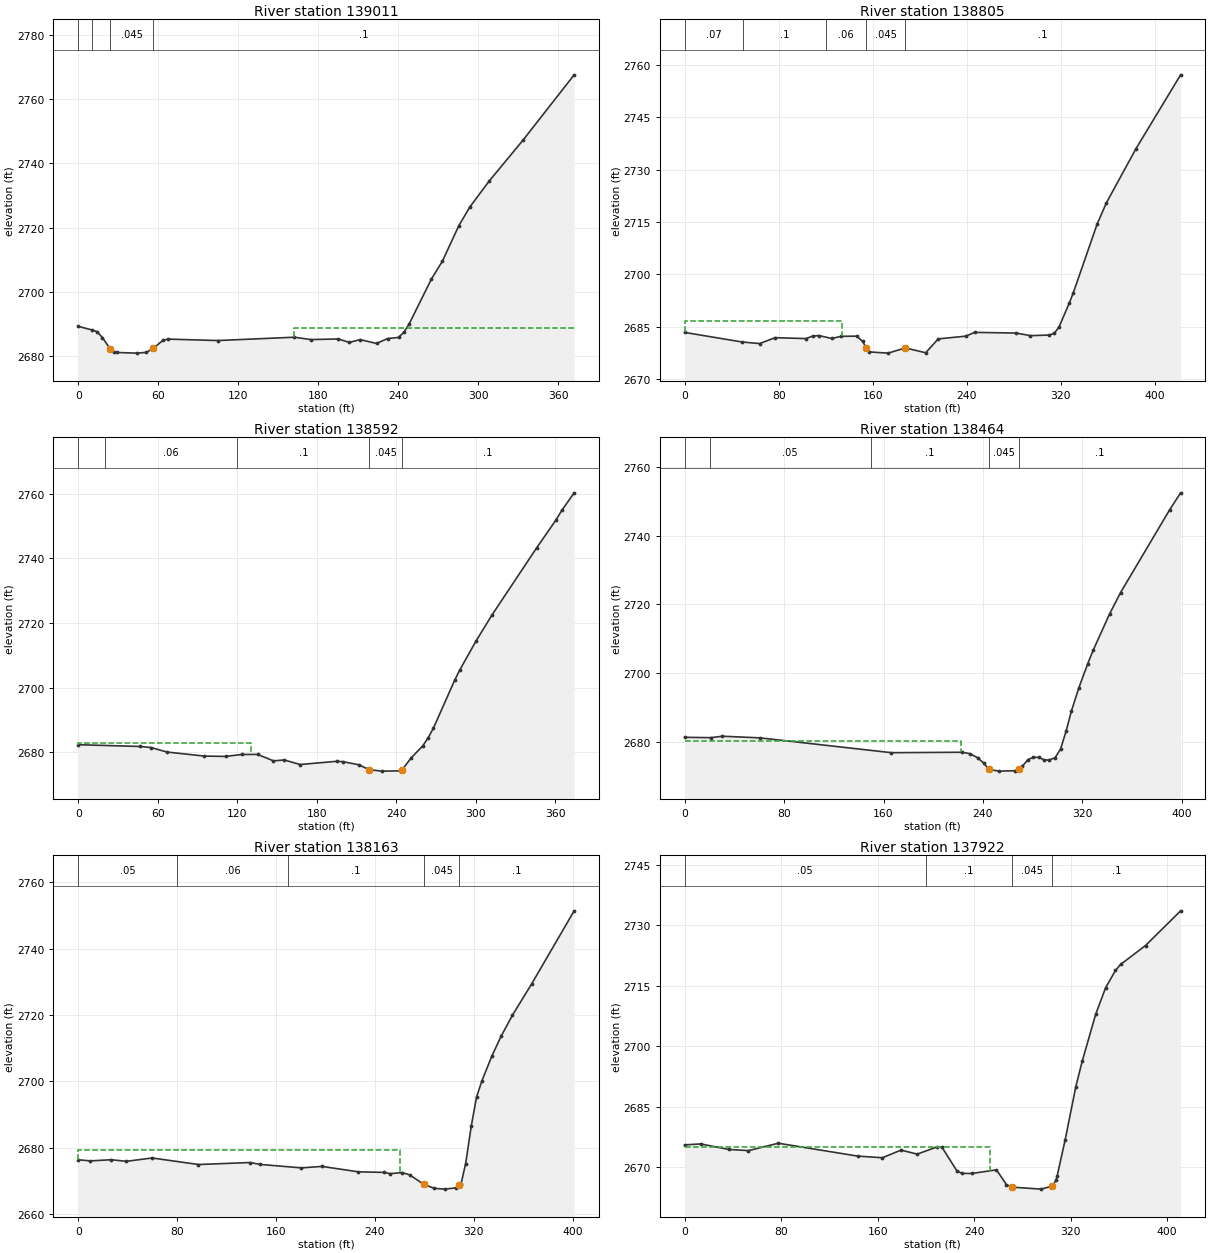
Type RM Length L Ch R = 1 ,139011  ,232.2,206.3,181.8
XS GIS Cut Line= 2
2298217.42434196465459.4259568672298131.30926864465821.304534623
#Sta/Elev= 30
       0 2689.22      10 2688.13    14.1 2687.56    18.2  2685.7      24 2682.16
    26.5 2681.25    29.1 2681.07    43.8 2680.87    51.1  2681.1    56.32682.341
    63.5 2684.85    67.6 2685.24   104.6 2684.79   162.2 2685.83   174.5 2685.09
   195.1 2685.28   203.3 2684.21   211.5 2685.08   223.8 2683.88   232.1 2685.42
   240.3 2685.76   244.4 2687.43   248.3 2690.02   264.9 2703.92   273.2 2709.55
   285.5 2720.58   293.7 2726.36   308.2 2734.45   333.7 2747.25     372 2767.57
#Mann= 4 ,-1,0
       0     .06       0      10      .1       0      24    .045       0
    56.3      .1       0
#XS Ineff= 2 , 0
                          162.17         2688.73
Permanent Ineff=
       F       F
Bank Sta=24,56.3
XS Rating Curve= 0 ,0
Exp/Cntr(USF)=0,0
Exp/Cntr=0.3,0.1

Type RM Length L Ch R = 1 ,138805  ,194.7,212.9,231.6
XS GIS Cut Line= 3
 2297903.7998267465431.4954716342298062.28062321465610.760177832
2298034.36829006465791.404111668
#Sta/Elev= 30
       0 2683.36    48.9 2680.61    63.8 2680.16      77 2681.85   103.2 2681.59
   109.1 2682.33   114.4 2682.45     125 2681.63   133.4 2682.24   146.4 2682.29
   151.5 2680.77   154.5 2678.91   157.3 2677.76   173.1 2677.42   187.8 2678.91
   205.1 2677.53   215.8  2681.5   239.3 2682.29   246.7 2683.37   282.2 2683.18
   294.3 2682.43   310.5 2682.61   314.6 2683.13   318.6  2684.9   327.4 2691.83
   330.8 2694.76     351 2714.38   358.9 2720.51     384 2735.99   422.1 2757.23
#Mann= 5 ,-1,0
       0     .07       0      50      .1       0     120     .06       0
   154.5    .045       0   187.8      .1       0
#XS Ineff= 2 , 0
          133.55 2686.51
Permanent Ineff=
       F       F
Bank Sta=154.5,187.8
XS Rating Curve= 0 ,0
Exp/Cntr(USF)=0,0
Exp/Cntr=0.3,0.1

Type RM Length L Ch R = 1 ,138592  ,140.1,127.7,117.5
XS GIS Cut Line= 2
2297878.85088258465446.4930217212297843.98674775465818.988778068
#Sta/Elev= 30
       0 2682.29    46.9 2681.74    54.9 2681.42      67 2680.02    95.1 2678.77
   111.2 2678.66   123.2 2679.26   135.3 2679.29   147.3 2677.29   155.4 2677.57
   167.4 2676.16     195 2677.15   199.6 2677.04   211.6 2676.08   219.72674.533
     229 2674.11   243.7 2674.19   244.52674.605   251.1 2678.19   259.8 2681.89
   263.8 2684.31   267.9 2687.38   283.9 2702.19   287.9 2705.49     300 2714.34
     312 2722.38   345.7 2743.18   360.3 2751.82   364.9 2754.92   374.1 2760.28
#Mann= 5 ,-1,0
       0     .07       0      20     .06       0     120      .1       0
   219.7    .045       0   244.5      .1       0
#XS Ineff= 2 , 0
           130.1 2682.89
Permanent Ineff=
       F       F
Bank Sta=219.7,244.5
XS Rating Curve= 0 ,0
Exp/Cntr(USF)=0,0
Exp/Cntr=0.3,0.1

Type RM Length L Ch R = 1 ,138464  ,296.6,300.7,303
XS GIS Cut Line= 2
2297627.46212091 465453.832839582297792.60802273465817.153823604
#Sta/Elev= 30
       0 2681.26    21.2 2681.16    30.3 2681.58    60.5  2681.1   166.4 2676.78
   223.4 2676.91   229.6 2676.49   235.7 2675.32   240.9 2673.67   244.7  2671.9
     253 2671.41   265.9 2671.53   268.9 2671.97   271.7 2672.79   276.1 2674.73
   280.5 2675.44   284.9 2675.42   289.3  2674.7   293.1 2674.64   298.1 2675.33
   302.5 2677.86   306.9 2683.02   311.2 2688.89   317.2 2695.69   324.4 2702.73
   328.8  2706.7     342 2717.24   350.8 2723.45   390.3 2747.57   399.1 2752.49
#Mann= 5 ,-1,0
       0     .06       0      20     .05       0     150      .1       0
   244.7    .045       0   268.9      .1       0
#XS Ineff= 2 , 0
          222.45 2680.07
Permanent Ineff=
       F       F
Bank Sta=244.7,268.9
XS Rating Curve= 0 ,0
Exp/Cntr(USF)=0,0
Exp/Cntr=0.3,0.1

Type RM Length L Ch R = 1 ,138163  ,227.6,241.6,253.2
XS GIS Cut Line= 2
2297368.73354137465499.7067011992297480.66576372  465885.0471388
#Sta/Elev= 30
       0 2676.43     9.9 2676.09    26.5 2676.44      39 2675.96    59.8 2676.97
    97.3    2675     139  2675.6   147.3 2675.03   180.6 2673.99   197.3 2674.43
   226.7  2672.8   247.3 2672.63   252.5 2672.25   262.2 2672.57   268.1 2671.89
   279.82669.014     288 2667.83   296.5 2667.59   305.6 2667.96   308.3 2668.78
   309.8 2669.23   313.5 2675.29   318.1 2686.67   322.3 2695.28   326.7 2700.24
   334.8 2707.73   342.1 2713.55   351.4 2719.98     367 2729.44   401.3 2751.38
#Mann= 5 ,-1,0
       0     .05       0      80     .06       0     170      .1       0
   279.8    .045       0   308.3      .1       0
#XS Ineff= 2 , 0
             260 2679.22
Permanent Ineff=
       F       F
Bank Sta=279.8,308.3
XS Rating Curve= 0 ,0
Exp/Cntr(USF)=0,0
Exp/Cntr=0.3,0.1

Type RM Length L Ch R = 1 ,137922  ,424.6,435.6,444.8
XS GIS Cut Line= 2
2297280.65572706465477.687247622 2297185.2380949465877.707320941
#Sta/Elev= 30
       0 2675.48    13.3 2675.72    36.5 2674.35    52.9 2674.06    77.6 2675.89
   143.4  2672.7     164 2672.29   179.3 2674.19   192.8 2673.19   208.9 2674.95
   213.3 2674.92   225.6 2669.08   229.8 2668.41     238 2668.38   258.5 2669.29
   266.8 2665.62   271.52664.997   295.5  2664.5   304.82665.262   307.9  2666.7
   308.8 2667.73   315.4 2676.63   324.3 2689.93   329.6 2696.24   340.8 2707.93
     349 2714.47   357.2 2718.79   361.4 2720.26   382.1 2724.97   411.2 2733.58
#Mann= 4 ,-1,0
       0     .05       0     200      .1       0   271.5    .045       0
   304.8      .1       0
#XS Ineff= 2 , 0
          253.52 2674.97
Permanent Ineff=
       F       F
Bank Sta=271.5,304.8
XS Rating Curve= 0 ,0
Exp/Cntr(USF)=0,0
Exp/Cntr=0.3,0.1