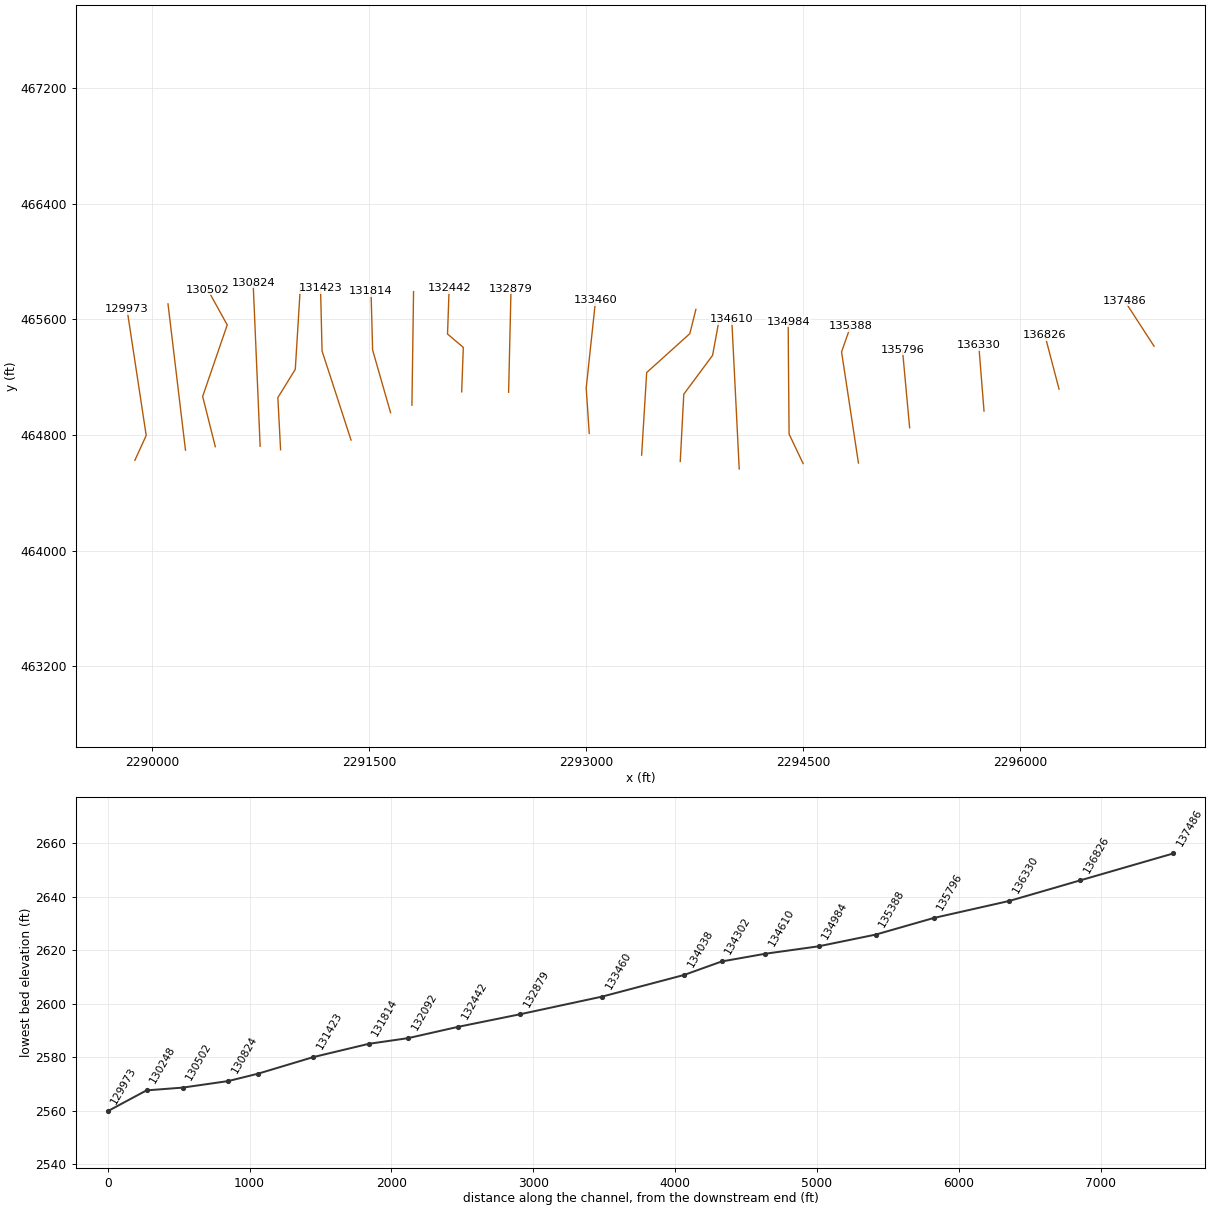
HEC-RAS study KNAPPCK.prj: KNAPPCK

--- KNAPPCK.g01 (geometry) --- (continued)

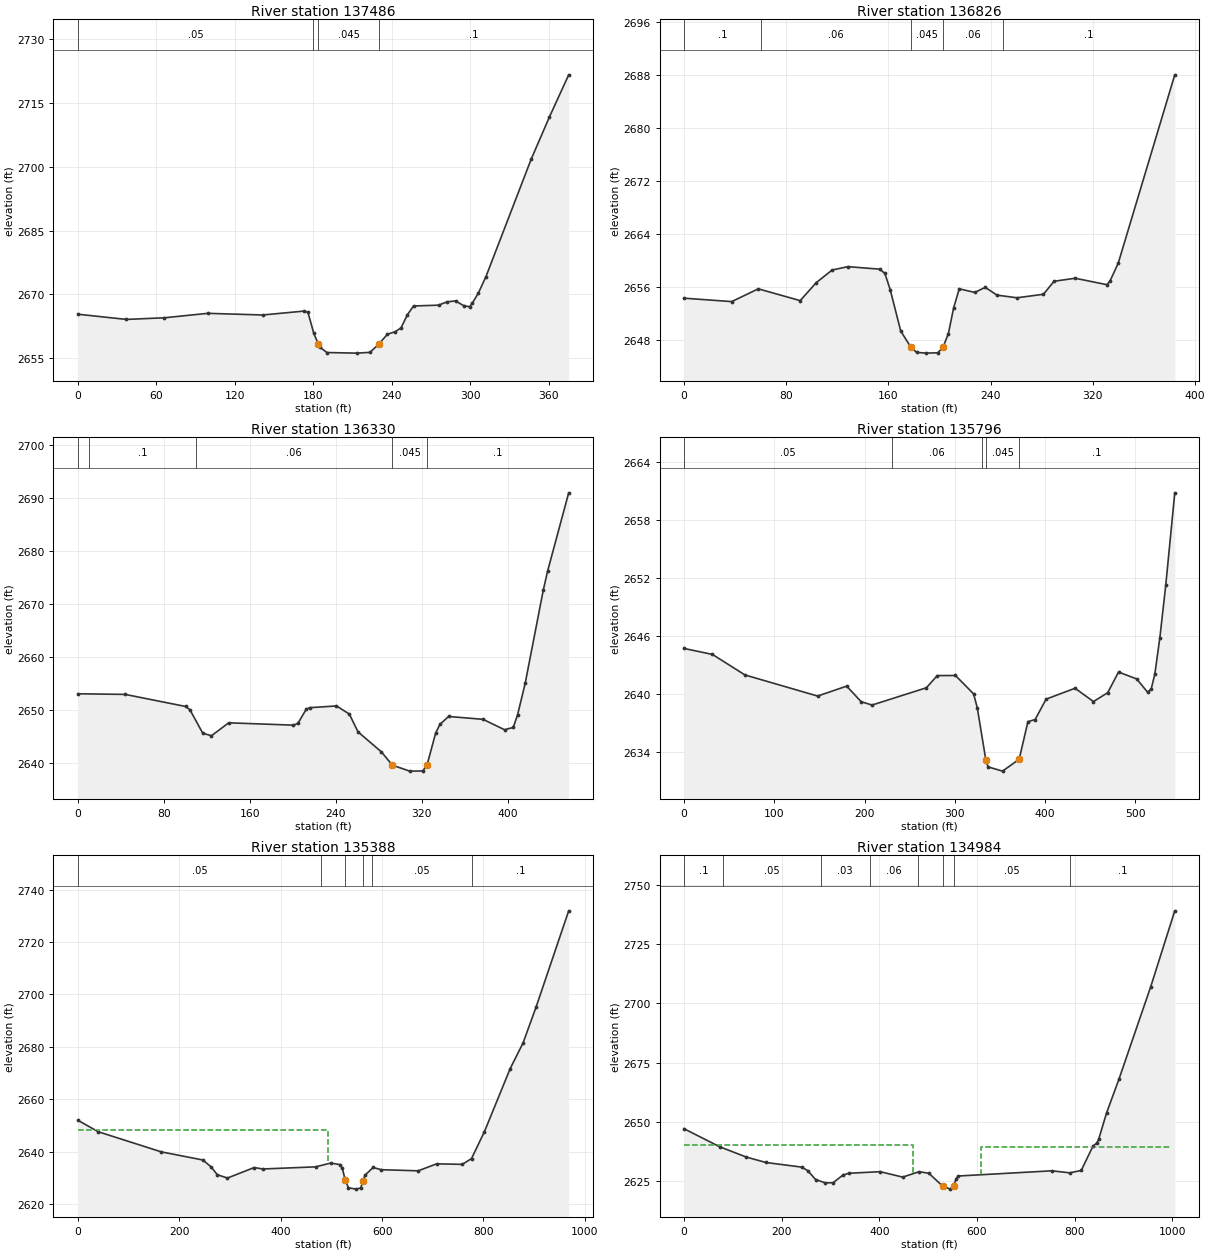
Type RM Length L Ch R = 1 ,137486  ,669,659.8,652.3
XS GIS Cut Line= 2
2296928.00497401465413.8473593512296724.12114459465728.734607008
#Sta/Elev= 30
       0 2665.31      37 2664.09    65.9 2664.47    99.3 2665.52   141.1 2665.13
   172.9 2666.05   175.8 2665.75   180.3 2660.78   183.7 2658.31     185 2657.54
   190.3  2656.3   213.1 2656.16   223.2 2656.34   229.92658.255   236.6 2660.63
   242.4 2661.17     247 2662.13   251.8 2665.18   256.5 2667.25   275.6 2667.44
   282.2 2668.23   288.6 2668.44   294.7 2667.35   299.4 2667.06   301.4  2667.9
     306 2670.25   311.8 2674.11   346.5 2701.83   360.3 2711.66   375.1 2721.62
#Mann= 4 ,-1,0
       0     .05       0     180      .1       0   183.7    .045       0
   229.9      .1       0
Bank Sta=183.7,229.9
XS Rating Curve= 0 ,0
Exp/Cntr(USF)=0,0
Exp/Cntr=0.3,0.1

Type RM Length L Ch R = 1 ,136826  ,500.5,496.1,492.7
XS GIS Cut Line= 2
2296271.04596811465117.0831187542296173.63480516465488.604763471
#Sta/Elev= 30
       0 2654.34    37.3 2653.82    58.1 2655.75    90.9 2653.97   103.5 2656.69
   115.9 2658.59   128.3  2659.1   153.1 2658.72   157.2 2658.08   161.4  2655.6
   169.6 2649.38   177.52646.946     182 2646.16   189.2 2646.04   198.6 2646.09
   202.7 2646.92   206.9    2649     211 2652.86   215.4 2655.75   227.5 2655.21
   235.8 2655.97   244.9  2654.8   260.6  2654.4   281.3 2654.93   289.6 2656.89
   306.1 2657.35   330.9 2656.38   333.3 2656.88   339.9 2659.66   384.1 2688.07
#Mann= 5 ,-1,0
       0      .1       0      60     .06       0   177.5    .045       0
   202.7     .06       0     250      .1       0
Bank Sta=177.5,202.7
XS Rating Curve= 0 ,0
Exp/Cntr(USF)=0,0
Exp/Cntr=0.3,0.1

Type RM Length L Ch R = 1 ,136330  ,533,534,533.3
XS GIS Cut Line= 2
2295752.27489103464965.3029346312295716.02887692465420.643486999
#Sta/Elev= 30
       0 2653.03      44 2652.91   100.2 2650.63   104.2 2650.02   116.2 2645.57
   124.3  2645.1   140.3 2647.54   200.5  2647.1   204.7 2647.42   212.5  2650.1
   215.6  2650.4   240.6 2650.73   252.6  2649.2   260.7 2645.83   282.5 2642.04
   292.62639.547   308.8 2638.41   320.9 2638.44   324.9 2639.52   332.9 2645.56
   336.9 2647.24     345 2648.74   377.1  2648.2   397.1 2646.23   405.2 2646.67
   409.2 2649.03   416.3    2655   433.2 2672.67   437.3 2676.31   456.8 2691.01
#Mann= 5 ,-1,0
       0     .12       0      10      .1       0     110     .06       0
   292.6    .045       0   324.9      .1       0
Bank Sta=292.6,324.9
XS Rating Curve= 0 ,0
Exp/Cntr(USF)=0,0
Exp/Cntr=0.3,0.1

Type RM Length L Ch R = 1 ,135796  ,406.5,408.5,409.9
XS GIS Cut Line= 2
2295238.03456572464849.7687646272295188.19629631465391.193600527
#Sta/Elev= 30
       0 2644.72    31.5  2644.1    67.4 2641.98     148 2639.79   180.2 2640.82
   196.2 2639.21   208.3 2638.86   268.5 2640.65   280.6 2641.91   300.7 2641.92
   320.8 2640.02   324.9 2638.57   334.32633.217   336.8 2632.46   352.9 2632.02
   371.3 2633.25     381 2637.14     389 2637.36   401.1 2639.47   433.2  2640.6
   453.6 2639.22   469.4 2640.14   481.4 2642.28   501.5 2641.56   513.6 2640.19
   517.6 2640.53   521.6 2642.07   527.2 2645.85   533.7 2651.27   543.7 2660.83
#Mann= 5 ,-1,0
       0     .05       0     230     .06       0     330      .1       0
   334.3    .045       0   371.3      .1       0
Bank Sta=334.3,371.3
XS Rating Curve= 0 ,0
Exp/Cntr(USF)=0,0
Exp/Cntr=0.3,0.1

Type RM Length L Ch R = 1 ,135388  ,406.7,403.6,399
XS GIS Cut Line= 3
2294884.03159011464605.4736348682294767.31111318465374.631649538
2294830.16060076465554.201614052
#Sta/Elev= 30
       0 2652.05    40.2 2647.68   164.7 2640.01   246.5 2636.92   262.7  2634.3
   274.8 2631.33     295 2630.05   347.6 2634.04   364.9  2633.5     469 2634.31
   498.4 2635.76   517.6 2635.15   521.6 2633.76   527.52629.158   533.7 2626.35
   548.3 2625.82     558 2626.25   562.1  2628.9   566.1 2631.08   582.3 2634.07
   598.5 2633.22   671.3  2632.8   707.7 2635.46   758.2 2635.26   776.5 2637.47
   801.9 2647.69   852.8 2671.77   878.1 2681.49   903.6 2695.06   968.2 2731.89
#Mann= 6 ,-1,0
       0     .05       0     480     .06       0   527.5    .045       0
   562.1     .06       0     580     .05       0  777.96      .1       0
#XS Ineff= 2 , 0
          492.39 2648.19
Permanent Ineff=
       F       F
Bank Sta=527.5,562.1
XS Rating Curve= 0 ,0
Exp/Cntr(USF)=0,0
Exp/Cntr=0.3,0.1

Type RM Length L Ch R = 1 ,134984  ,373.4,374.6,374.6
XS GIS Cut Line= 4
2294501.59150311464601.6093538962294404.49609088  464806.3903218
 2294399.8444471465337.8720228312294398.17169392465584.737373791
#Sta/Elev= 30
       0 2646.98    72.8 2639.37   127.9 2634.97   167.7  2632.7   241.4 2630.73
   253.5 2629.21   269.4  2625.5   289.4 2624.06   305.4 2624.15   325.4  2627.4
   337.4 2628.13   401.4 2628.82   447.8 2626.52   481.4  2628.8   501.4 2628.14
   529.4 2622.73   545.4 2621.43     552 2622.75   557.4 2625.87   561.4 2626.98
   753.4 2629.18     790 2628.32   813.4 2629.32   837.4  2639.6   845.4 2640.97
   849.4  2642.7   865.4 2653.72   890.7 2667.96   955.8 2707.11    1005 2739.17
#Mann= 8 ,-1,0
       0      .1       0      80     .05       0     280     .03       0
     380     .06       0     480     .05       0   529.4    .045       0
     552     .05       0     790      .1       0
#XS Ineff= 2 ,-1
       0  468.17 2640.05  607.32     996  2639.3
Permanent Ineff=
       F       F
Bank Sta=529.4,552
XS Rating Curve= 0 ,0
Exp/Cntr(USF)=0,0
Exp/Cntr=0.3,0.1

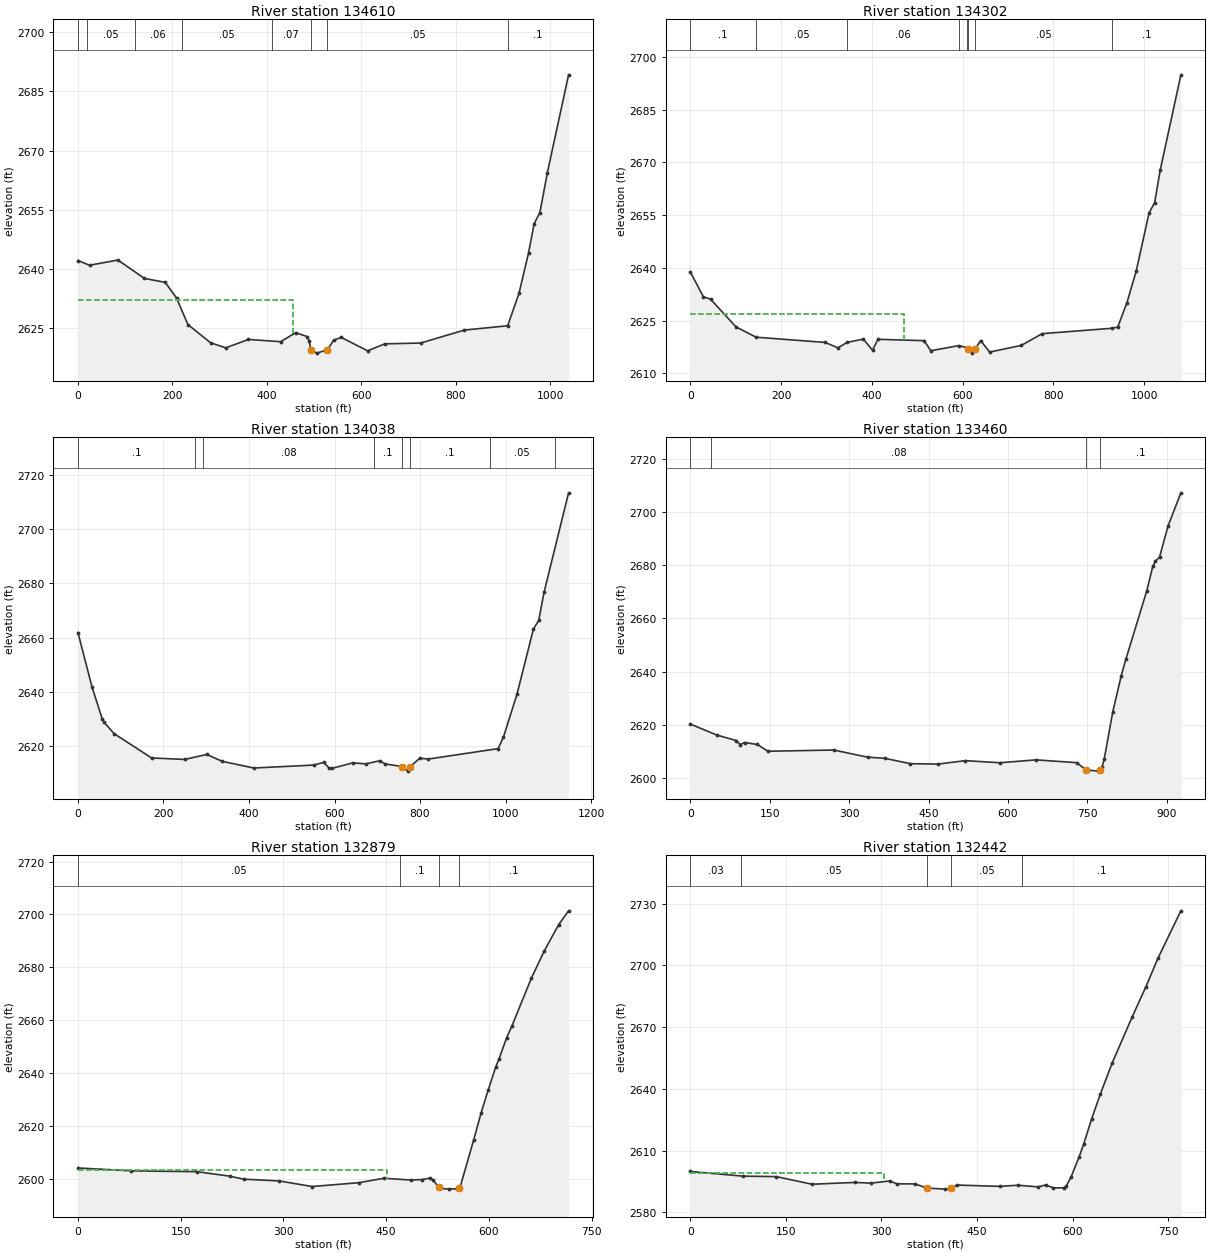
Type RM Length L Ch R = 1 ,134610  ,327.7,307.9,292.5
XS GIS Cut Line= 2
2294059.70708564464564.6830155342294007.93546157465601.873557592
#Sta/Elev= 30
       0 2642.13    24.5 2640.94    84.6 2642.26   140.7  2637.6   184.7  2636.6
   208.8  2632.6   232.7 2625.91   280.8 2621.28   312.9    2620   360.9 2622.13
     429 2621.56   461.1 2623.85   485.1 2622.85   489.1 2621.85   493.1 2619.56
   505.1 2618.66   527.9 2619.48   541.2 2621.94   557.2 2622.65   613.3 2619.24
   649.3 2621.01   725.4 2621.22   817.5 2624.49   909.6  2625.6   933.7 2633.87
   953.7 2644.04   965.7 2651.51   977.7 2654.25   993.7 2664.44  1038.5 2689.21
#Mann= 8 ,-1,0
       0      .1       0      20     .05       0     120     .06       0
     220     .05       0     410     .07       0   493.1    .045       0
   527.9     .05       0     910      .1       0
#XS Ineff= 2 , 0
          454.31 2632.21
Permanent Ineff=
       F       F
Bank Sta=493.1,527.9
XS Rating Curve= 0 ,0
Exp/Cntr(USF)=0,0
Exp/Cntr=0.3,0.1

Type RM Length L Ch R = 1 ,134302  ,267,264.3,259.7
XS GIS Cut Line= 4
2293651.95744156464616.3813833862293676.45582382465082.064407904
2293875.44695609465350.688987603 2293926.3251127465626.029599858
#Sta/Elev= 30
       0 2638.88    28.8 2631.81    44.9 2631.08   100.9  2623.2     145  2620.3
   297.2 2618.81   325.2 2617.26   345.3 2618.82   381.3 2619.75   401.4 2616.59
   413.4  2619.7     515 2619.31   529.9 2616.45   591.3 2617.91   608.5 2617.35
  612.23 2616.81   619.9 2615.77   627.1 2616.84   639.5 2619.35   659.4 2616.07
   729.1 2617.96     775  2621.3   929.3 2622.84   941.5 2623.16   961.8 2630.11
   982.5 2639.23  1010.6 2655.65  1022.8 2658.53    1035 2667.73  1080.6 2694.86
#Mann= 8 ,-1,0
       0      .1       0     145     .05       0   345.3     .06       0
   591.3      .1       0   608.5     .05       0  612.23    .045       0
   627.1     .05       0   929.3      .1       0
#XS Ineff= 2 , 0
           470.2 2626.88
Permanent Ineff=
       F       F
Bank Sta=612.23,627.1
XS Rating Curve= 0 ,0
Exp/Cntr(USF)=0,0
Exp/Cntr=0.3,0.1

Type RM Length L Ch R = 1 ,134038  ,562.6,577.5,592.5
XS GIS Cut Line= 4
 2293384.9109569464660.4332108852293419.82370644465231.755370497
2293718.16408095465501.0683782632293760.11548618465668.873999183
#Sta/Elev= 30
       0 2661.87    32.8 2641.86    56.7 2630.04    60.9 2628.83    84.9 2624.53
   172.3  2615.6   249.3 2615.06   301.3 2616.89   337.4 2614.35   411.3 2611.89
   551.4 2612.98   574.5 2613.97   586.5    2612   594.4 2611.77   642.9  2613.8
   672.8 2613.42   705.8 2614.56   718.1  2613.4   757.7 2612.44   771.5 2610.74
776.0416 2612.24   799.2 2615.51   819.3  2615.2   982.6 2619.05     995 2623.31
  1026.7 2639.11  1065.1 2663.21  1077.5 2666.36  1089.9 2676.73  1147.3 2713.47
#Mann= 8 ,-1,0
       0      .1       0  272.87     .06       0  292.87     .08       0
  692.87      .1       0   757.7    .045       0776.0416      .1       0
  962.87     .05       0 1115.37      .1       0
Bank Sta=757.7,776.0416
XS Rating Curve= 0 ,0
Exp/Cntr(USF)=0,0
Exp/Cntr=0.3,0.1

Type RM Length L Ch R = 1 ,133460  ,578.9,581.2,583
XS GIS Cut Line= 3
2293022.58940812464810.7388470922293001.73758593 465124.83498558
2293066.51891971465733.199487202
#Sta/Elev= 30
       0 2620.34    50.6 2616.18    86.6 2614.15    94.6 2612.63   102.7  2613.4
   126.7 2612.66   146.8 2610.12     271 2610.58   334.9 2607.89   367.4 2607.47
   415.5 2605.45     468  2605.3   519.5 2606.59   584.6  2605.8     653 2606.88
   729.5 2605.84747.57512603.115   769.7 2602.65  774.63 2603.18   777.7  2604.2
   781.8 2607.15   797.8 2624.75   813.9 2638.46   822.6 2644.62   862.2 2670.42
   873.5 2679.54   878.3 2681.49   886.3 2683.06   902.4 2694.78   926.6 2707.21
#Mann= 4 ,-1,0
       0     .06       0      40     .08       0747.5751    .045       0
  774.63      .1       0
Bank Sta=747.5751,774.63
XS Rating Curve= 0 ,0
Exp/Cntr(USF)=0,0
Exp/Cntr=0.3,0.1

Type RM Length L Ch R = 1 ,132879  ,412.6,436.5,460.3
XS GIS Cut Line= 2
2292465.21544474465095.5381277052292481.99600683465811.508776965
#Sta/Elev= 30
       0 2604.03    77.7 2602.94   173.7 2602.62   221.7 2600.93   241.7  2599.8
   293.6 2599.13   341.7 2597.01   409.8 2598.45   446.3 2600.13   485.8 2599.47
   501.8 2599.63   513.8 2600.17   517.8 2599.66   526.72596.718   529.8 2596.28
   541.8 2596.02   553.8 2596.19   556.72596.569   557.8 2596.71   577.8 2614.75
   588.6 2624.96   598.7 2633.38   609.8 2642.19   614.4 2645.13   625.8 2653.32
   633.7  2657.9   661.8 2675.84   680.8 2686.25   701.8 2696.17   716.2 2701.38
#Mann= 4 ,-1,0
       0     .05       0     470      .1       0   526.7    .045       0
   556.7      .1       0
#XS Ineff= 2 , 0
          451.84  2603.2
Permanent Ineff=
       F       F
Bank Sta=526.7,556.7
XS Rating Curve= 0 ,0
Exp/Cntr(USF)=0,0
Exp/Cntr=0.3,0.1

Type RM Length L Ch R = 1 ,132442  ,371.5,350.4,316
XS GIS Cut Line= 4
 2292140.7912443465098.3348880542292151.97828569465405.978526408
2292042.90463209465498.2716179142292054.09167349465817.102297663
#Sta/Elev= 30
       0 2599.89    82.9 2597.62   134.9  2597.4     191  2593.7     259 2594.58
     283 2594.22   312.8 2595.28   324.2  2593.9   352.6 2593.85   371.42591.833
   399.5 2591.32   409.3 2591.69   418.1  2593.3   485.7 2592.66   513.7 2593.21
   545.7 2592.42   557.7 2593.32   569.7 2591.93   585.7 2591.96   589.7 2592.62
   597.6  2597.3   610.1 2606.92   617.2 2613.06   629.7 2625.38   643.2 2637.29
   661.8 2652.44     693  2674.7   715.1  2689.7   733.8 2703.41   769.8 2726.45
#Mann= 5 ,-1,0
       0     .03       0      80     .05       0   371.4    .045       0
   409.3     .05       0  520.73      .1       0
#XS Ineff= 2 , 0
          304.27 2599.16
Permanent Ineff=
       F       F
Bank Sta=371.4,409.3
XS Rating Curve= 0 ,0
Exp/Cntr(USF)=0,0
Exp/Cntr=0.3,0.1

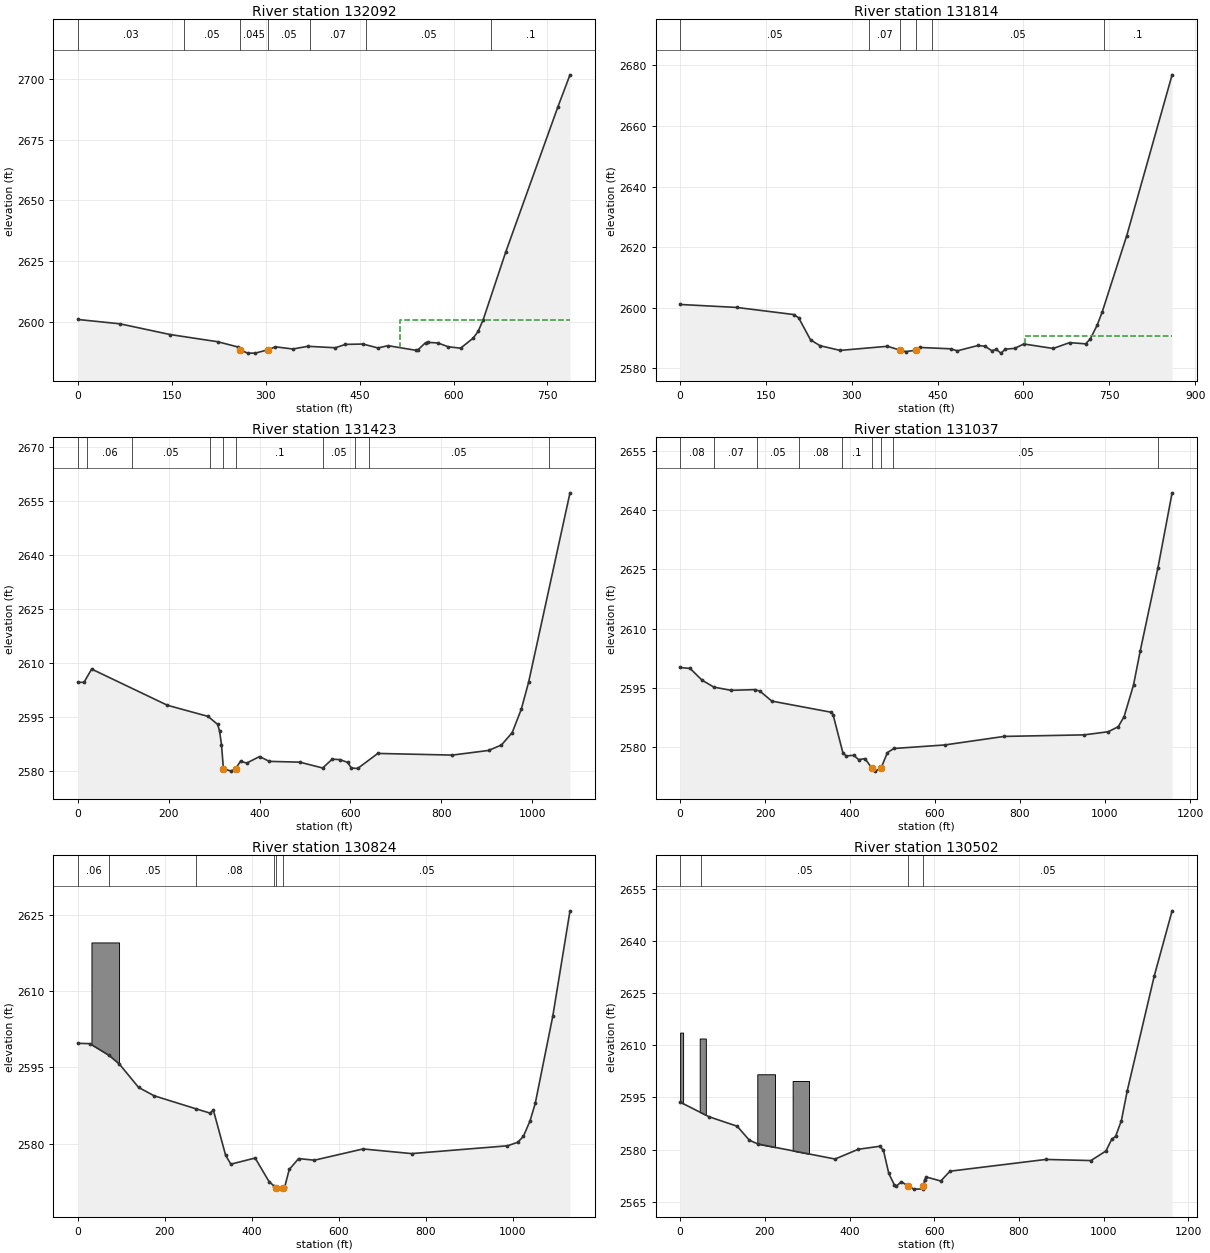
Type RM Length L Ch R = 1 ,132092  ,270.5,278.4,280.5
XS GIS Cut Line= 2
2291796.78972141465006.041796547 2291807.9767628465791.931454525
#Sta/Elev= 30
       0 2600.97    67.1 2599.18   147.2 2594.77   223.4  2591.8   255.2 2589.67
   258.9 2588.43   271.2 2587.12   283.2 2587.12   304.1 2588.56   315.2 2589.72
   343.2 2588.82   367.2 2589.93   411.2 2589.33   427.2 2590.72   455.2 2590.86
   479.2 2589.25   495.2 2590.19   539.2 2588.31   543.2 2588.51   555.2 2591.42
   559.2 2591.55   575.2  2591.3   591.2 2589.75   611.2 2589.15   631.2 2593.27
   639.2 2596.06   647.2 2600.79   683.2 2628.65   766.7 2688.54     786  2701.7
#Mann= 7 ,-1,0
       0     .03       0     170     .05       0   258.9    .045       0
   304.1     .05       0     370     .07       0     460     .05       0
     660      .1       0
#XS Ineff= 2 , 0
                          514.29         2600.83
Permanent Ineff=
       F       F
Bank Sta=258.9,304.1
XS Rating Curve= 0 ,0
Exp/Cntr(USF)=0,0
Exp/Cntr=0.3,0.1

Type RM Length L Ch R = 1 ,131814  ,390.3,390.5,393.5
XS GIS Cut Line= 3
2291649.02691461464954.0733064872291524.92696283465387.938390043
2291513.93086513465796.218044716
#Sta/Elev= 30
       0 2601.05    98.9 2600.07   198.8 2597.72   207.1 2596.65   227.9 2589.36
   244.5 2587.44   279.5 2585.88   362.3 2587.24   384.2 2585.98   394.3 2585.47
     413 2585.99   419.3 2586.85   472.5 2586.41   484.5 2585.75   520.5  2587.5
   532.5 2587.27   544.5  2585.8   552.5  2586.2   560.5 2584.98   568.5  2586.3
   584.6 2586.55   600.6    2588   651.9 2586.52   680.6 2588.45   708.6 2588.05
   716.6 2589.65   728.6 2594.14   737.7 2598.65   780.5 2623.82   859.7 2676.89
#Mann= 6 ,-1,0
       0     .05       0     330     .07       0   384.2    .045       0
     413     .07       0     440     .05       0     740      .1       0
#XS Ineff= 2 , 0
                          602.78         2590.56
Permanent Ineff=
       F       F
Bank Sta=384.2,413
XS Rating Curve= 0 ,0
Exp/Cntr(USF)=0,0
Exp/Cntr=0.3,0.1

Type RM Length L Ch R = 1 ,131423  ,402,386.6,370.7
XS GIS Cut Line= 3
 2291375.7275059464764.6745863882291175.29972528465381.313671111
2291164.93837093465816.379821496
#Sta/Elev= 30
       0  2604.7    13.1 2604.65      30 2608.35   196.8 2598.31   286.5 2595.21
   307.6 2592.98   311.8 2591.15     316 2587.39   320.2 2580.75     337 2580.03
   347.2 2580.75     358  2582.8   371.4 2582.26     400 2584.08   421.1 2582.74
   488.4 2582.52   538.9  2580.9   559.9 2583.35   576.8 2583.22   593.6 2582.47
     602 2580.91   615.9 2580.76   660.3 2584.94   824.3 2584.48   904.3 2585.77
   932.7 2587.29   956.3 2590.71   976.4 2597.24   992.4 2604.68  1083.6 2657.25
#Mann= 10 ,-1,0
       0     .07       0      20     .06       0     120     .05       0
     290     .08       0   320.2    .045       0   347.2      .1       0
     540     .05       0     610      .1       0     640     .05       0
 1038.39      .1       0
Bank Sta=320.2,347.2
XS Rating Curve= 0 ,0
Exp/Cntr(USF)=0,0
Exp/Cntr=0.3,0.1

Type RM Length L Ch R = 1 ,131037  ,176,212.5,217.1
XS GIS Cut Line= 4
2290888.59987967464697.652883319 2290869.7450334465058.588511993
 2290990.3165923465253.886172582 2291024.9885069465819.787149342
#Sta/Elev= 30
       0 2600.14    23.6 2599.89    51.6 2596.92    79.6 2595.16   119.7 2594.35
   175.8 2594.53   187.8 2594.15   215.8 2591.62     356 2588.79     360 2588.17
   383.3 2578.43   391.2 2577.72   408.7 2577.89   420.3 2576.77     435 2577.05
     4512574.683   458.5 2573.87   472.82574.633   487.9 2578.57   503.1 2579.61
   622.4  2580.5   762.6 2582.67   950.9 2583.06  1007.4 2583.85  1031.1 2585.12
    1045 2587.71  1067.1 2595.71  1082.9 2604.36  1124.5 2625.36  1157.9 2644.41
#Mann= 9 ,-1,0
       0     .08       0      80     .07       0     180     .05       0
     280     .08       0  381.43      .1       0     451    .045       0
   472.8      .1       0  501.43     .05       0 1124.65      .1       0
Bank Sta=451,472.8
XS Rating Curve= 0 ,0
Exp/Cntr(USF)=0,0
Exp/Cntr=0.3,0.1

Type RM Length L Ch R = 1 ,130824  ,335.5,321.9,309.9
BEGIN DESCRIPTION:
start of detailed reach
END DESCRIPTION:
XS GIS Cut Line= 2
 2290747.2930013464721.8340421372290698.80911088465853.124818577
#Sta/Elev= 30
       0 2599.71    27.4 2599.64    71.5 2597.34    95.4 2595.61   139.5 2591.04
   175.1 2589.41   271.6 2586.84   303.6 2586.01   311.6 2586.56   339.7 2577.73
   351.7 2575.97   407.7 2577.18   439.7 2572.54   451.5 2571.67   455.8 2571.36
   467.8 2571.07   471.8 2571.33   475.8 2571.52   486.1 2574.93   507.8 2577.07
     544 2576.75   655.9 2578.96     768 2578.05   988.3 2579.58  1012.1 2580.27
  1025.1 2581.45  1040.3 2584.47  1052.3  2587.9  1092.7 2605.04  1132.3 2625.73
#Mann= 6 ,-1,0
       0     .06       0    71.5     .05       0   271.6     .08       0
   451.5     .05       0   455.8    .045       0   471.8     .05       0
#Block Obstruct= 1 ,-1
   30.93   94.46 2619.52
Bank Sta=455.8,471.8
XS Rating Curve= 0 ,0
Exp/Cntr(USF)=0,0
Exp/Cntr=0.3,0.1

Type RM Length L Ch R = 1 ,130502  ,230.1,254.5,267.5
XS GIS Cut Line= 4
2290437.26462587464718.5846793572290349.88998613465066.669160396
2290519.69228431465561.4617862432290384.61203397465805.915256268
#Sta/Elev= 30
       0 2593.65    68.7 2589.42   134.6 2586.72   163.5 2582.68   184.1 2581.59
   365.7 2577.28   420.7 2580.09   471.5 2580.95   479.9 2579.79   492.6 2573.12
   505.3 2569.93   509.6  2569.4   522.2 2570.74     5392569.462   551.8 2568.62
     573 2568.65   574.42569.512   577.2 2571.37   581.4 2572.09   615.3 2570.96
     637 2573.78   863.3 2577.16   969.7 2576.84  1005.1 2579.59  1018.8 2582.97
  1027.9 2583.78  1041.6 2588.33  1055.3 2596.85  1119.3    2630  1161.3 2648.68
#Mann= 4 ,-1,0
       0     .04       0      50     .05       0     539    .045       0
   574.4     .05       0
#Block Obstruct= 4 ,-1
       0    7.06 2613.65   46.23   60.67 2611.95  182.16  224.04 2601.66
  265.62  304.17 2599.74
Bank Sta=539,574.4
XS Rating Curve= 0 ,0
Exp/Cntr(USF)=0,0
Exp/Cntr=0.3,0.1

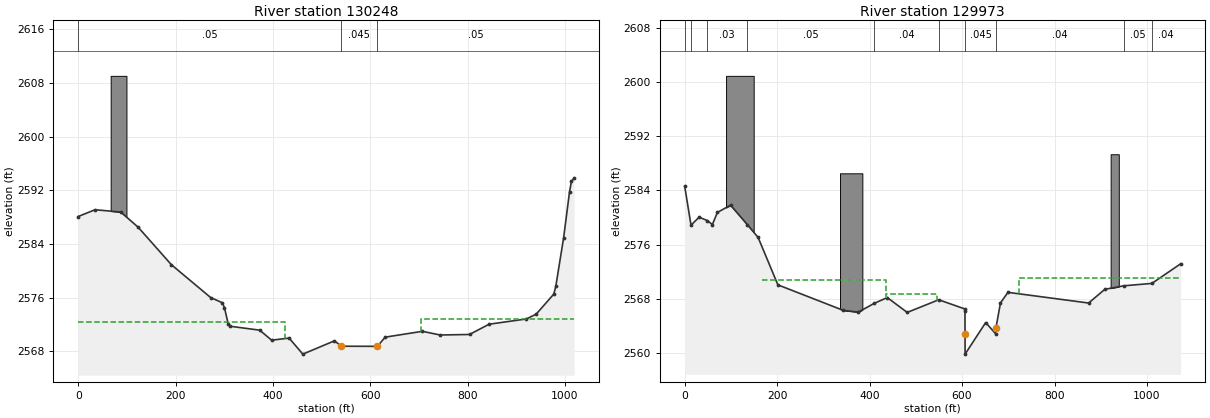
Type RM Length L Ch R = 1 ,130248  ,272.2,274.3,273.7
BEGIN DESCRIPTION:
xs 4
END DESCRIPTION:
XS GIS Cut Line= 2
2290231.05059579464694.9306259752290110.20292641465706.598258273
#Sta/Elev= 30
       0  2588.1    34.5 2589.11    87.4 2588.77   123.1 2586.51   191.4 2580.92
   272.2 2576.02   296.1 2575.25   300.4 2574.52   308.4 2572.03   312.5 2571.74
   372.9 2571.16   397.3 2569.67   433.3 2569.98   461.5 2567.59   526.4 2569.57
   540.8 2568.77   614.6 2568.75   630.7 2570.12   707.2 2570.99   743.5 2570.44
   803.9 2570.52   844.2 2572.05   920.7 2572.83   940.9 2573.55   977.1 2576.54
   981.2 2577.69   997.3 2584.94  1009.4 2591.77  1013.4 2593.34  1018.9  2593.8
#Mann= 3 ,-1,0
       0     .05       0   540.8    .045       0   614.6     .05       0
#XS Ineff= 2 , 0
          423.89 2572.39  704.45         2572.76
Permanent Ineff=
       F       F
#Block Obstruct= 1 ,-1
   66.66   99.13 2609.07
Bank Sta=540.8,614.6
XS Rating Curve= 0 ,0
Exp/Cntr(USF)=0,0
Exp/Cntr=0.5,0.3

Type RM Length L Ch R = 1 ,129973  ,172.4,169.8,168.5
BEGIN DESCRIPTION:
Structure XS3 - channel burned within banks
LOB IFA added to uncross profiles at this XS
END DESCRIPTION:
XS GIS Cut Line= 3
2289881.19646125464624.731045109 2289959.5243019464796.284230702
2289826.84439025 465670.49988083
#Sta/Elev= 30
       0 2584.63    13.7 2578.87    31.3 2580.05    48.9 2579.55    59.9 2578.96
    70.8 2580.75    99.2 2581.83   135.4 2578.95   158.8 2577.06   201.6 2570.04
   343.2 2566.26   375.6 2566.01   409.8 2567.29   438.2 2568.16   481.4 2565.96
   549.6 2567.83   606.2 2566.47  606.33 2566.12  606.47 2562.78   606.6 2559.79
  651.14 2564.46  672.41 2562.82  673.11 2563.59   683.1 2567.36   699.3 2568.93
   873.8 2567.35   908.9 2569.38   950.1  2569.9  1010.6 2570.25  1072.8 2573.15
#Mann= 10 ,-1,0
       0     .03       0    13.7    .016       0    48.9     .03       0
   135.4     .05       0   409.8     .04       0   549.6     .03       0
  606.47    .045       0  673.11     .04       0   950.1     .05       0
  1010.6     .04       0
#XS Ineff= 3 ,-1
  166.99  436.06 2570.79  436.06     545  2568.7     723  1072.8    2571
Permanent Ineff=
       F       F       F
#Block Obstruct= 3 ,-1
   89.54  149.28 2600.96  335.91  384.38 2586.54   921.4  939.06 2589.36
Bank Sta=606.47,673.11
XS Rating Curve= 0 ,0
Exp/Cntr(USF)=0,0
Exp/Cntr=0.5,0.3