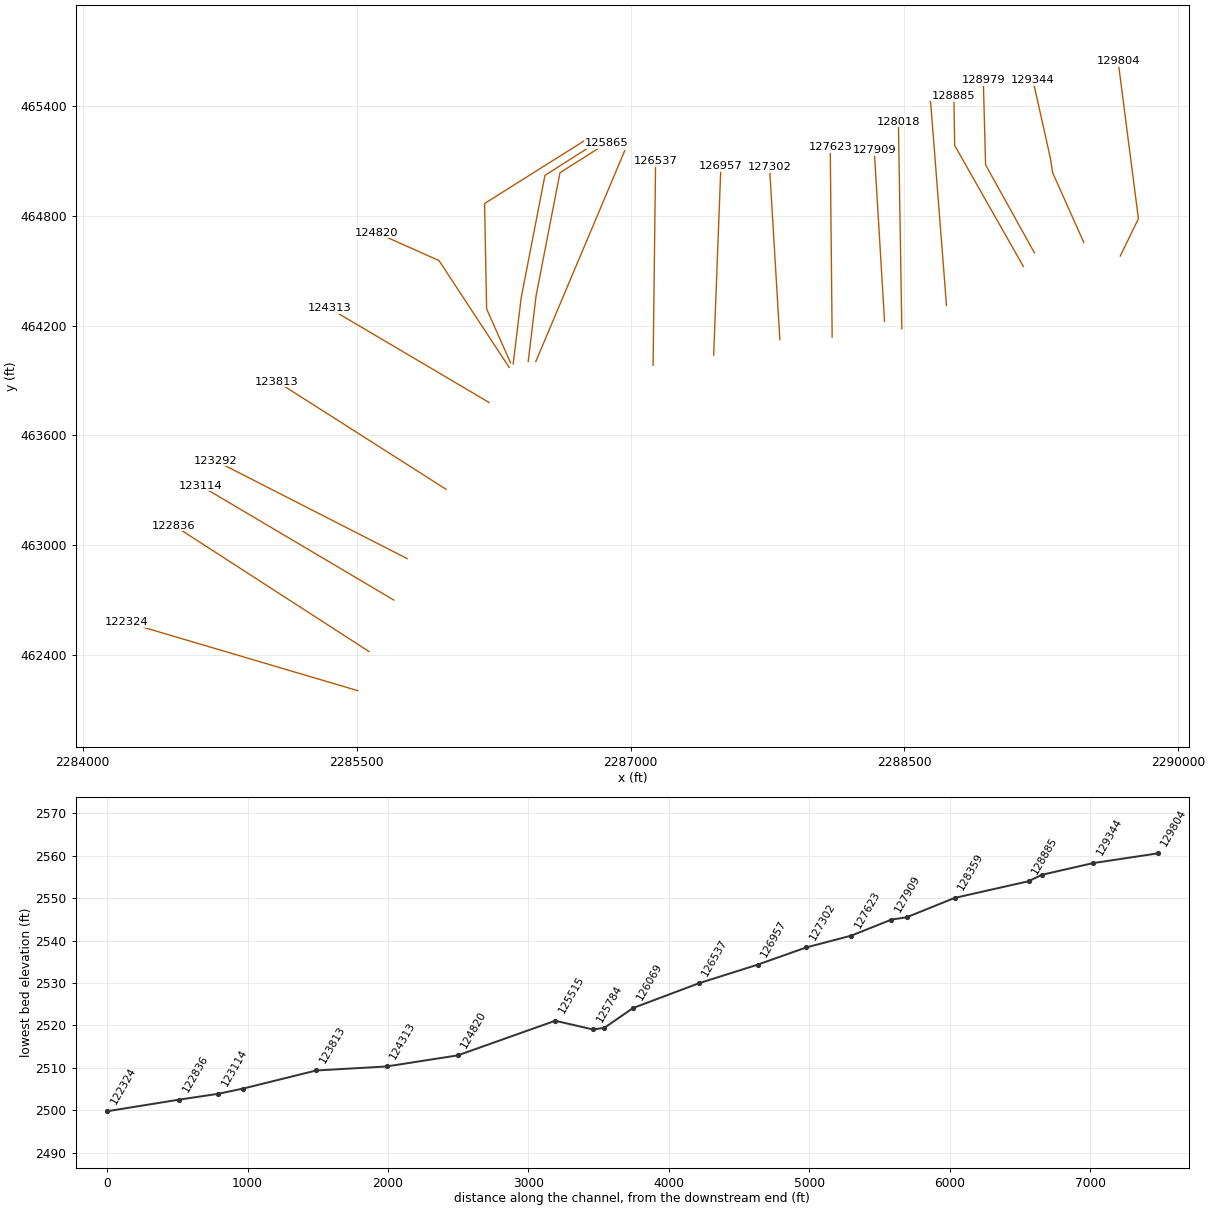
HEC-RAS study KNAPPCK.prj: KNAPPCK

--- KNAPPCK.g01 (geometry) --- (continued)

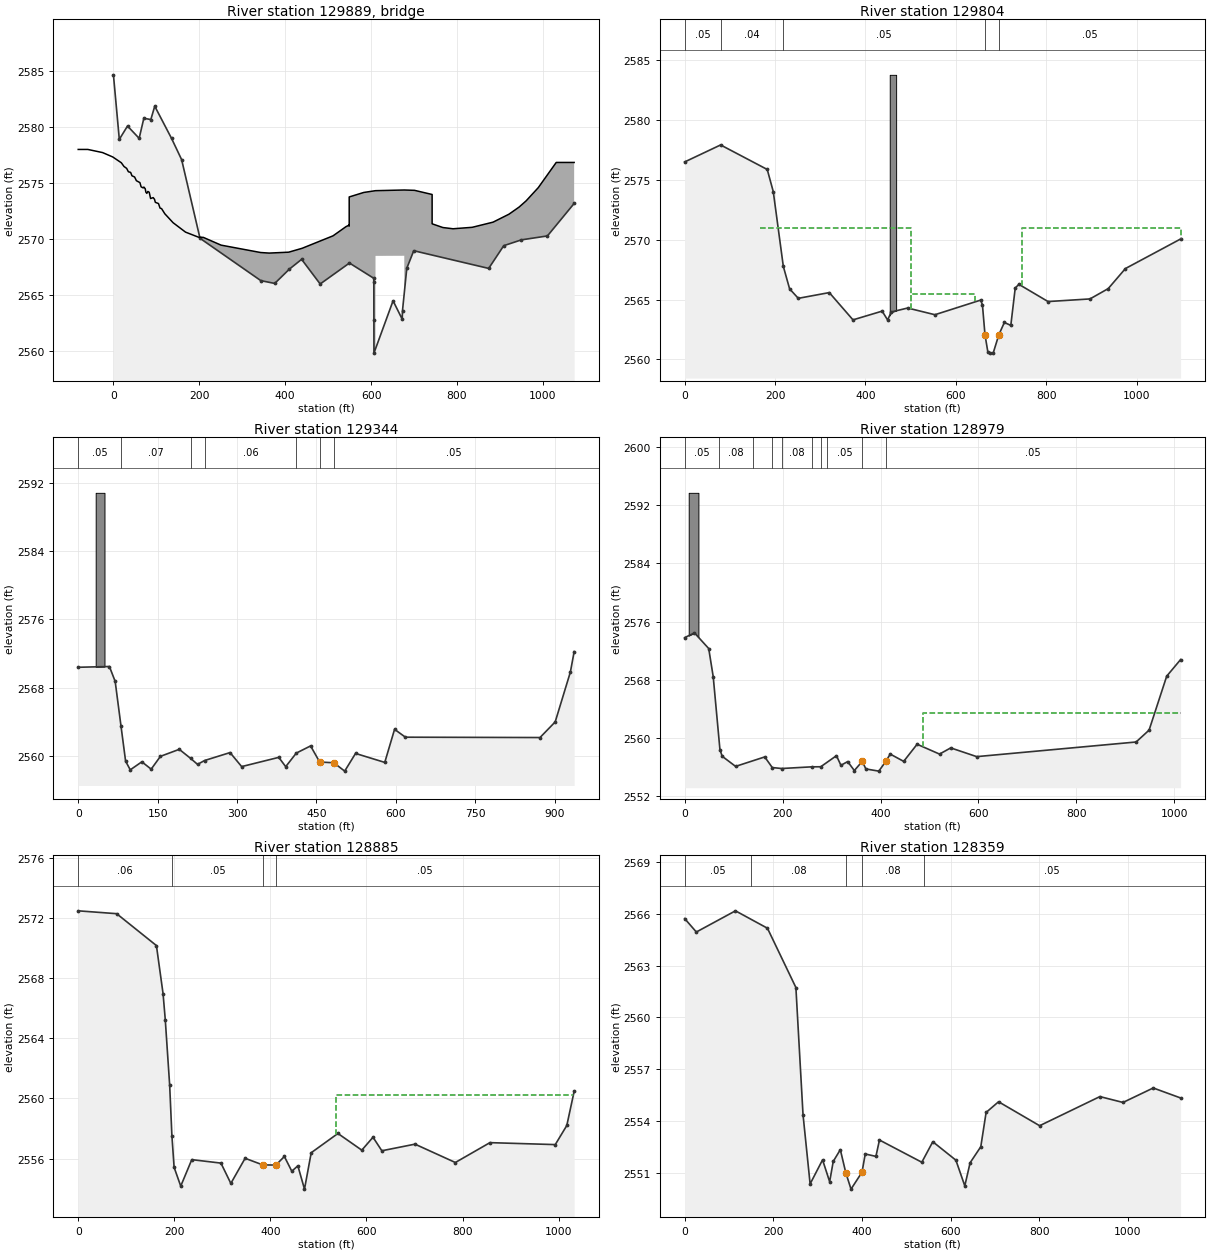
Type RM Length L Ch R = 3 ,129889  ,,,
BEGIN DESCRIPTION:
Frost Road
Bridge data: 54075KNA120
Width: 30' (measured on orthoimagery)
Railing height: 2.6'
Structure bounding section 3 incorporates channel data from survey. Structure section 2 from terrain
Deck from Lidar with survey data incorporated
END DESCRIPTION:
Bridge Culvert--1,0,-1,-1, 0
Deck Dist Width WeirC Skew NumUp NumDn MinLoCord MaxHiCord MaxSubmerge Is_Ogee
65,30,2.6,0, 60, 60, , , 0.98, 0, 0,0,,
     -82  -59.62  -25.28   -1.66   18.41   24.59   30.77   34.82   40.04   43.13
   49.31   53.47   61.67   64.49   69.16   70.94   74.03   75.52   77.74   80.21
    83.3   86.54   92.57   95.65   97.57  104.92  108.59  112.08  119.62  138.91
  167.88  197.93  209.39  250.61  342.73  362.73  408.05  439.54  511.35  541.58
  548.97     549     549  582.73  610.25  677.32  701.13  742.08  742.08   742.2
  767.16   790.8  835.35  883.95  920.96   944.7   960.9  989.25 1031.07  1072.8
 2577.97 2577.97 2577.69  2577.3 2576.78 2576.45 2576.28 2575.98 2575.92 2575.62
 2575.51 2575.18 2575.01 2574.63 2574.54 2574.61 2574.46 2574.16 2574.05 2574.22
 2574.15 2573.59 2573.67 2573.52 2573.25 2573.14 2572.73 2572.69 2572.23 2571.43
 2570.59 2570.14 2570.12 2569.43 2568.77 2568.72  2568.8 2569.15 2570.26 2571.08
 2571.22 2571.13 2573.73 2574.13 2574.29 2574.35 2574.32 2573.95 2571.35 2571.33
    2571 2570.89 2571.02 2571.48 2572.19 2572.83 2573.38 2574.56 2576.81 2576.81
                                                                                
                                                                                
                                                                                
                                                                                
                                 2568.47 2568.48
                                                                                
   42.61   70.41   76.59   82.77   86.82   92.04   95.13  101.31  105.47  113.67
  116.49  121.16  122.94  126.03  127.52  129.74  132.21   135.3  138.54  144.57
  147.65  149.57  156.92  160.59  164.08  169.28  171.62  190.91  219.88  249.93
  261.39  302.61  394.73  414.73  460.05  491.54  563.35  593.58  600.97     601
     601  634.73  662.25  729.32  753.13  794.08  794.08   794.2  819.16   842.8
  863.05  903.05  935.95   956.2   996.7  1012.9 1041.25  1069.6 1083.07 1097.25
 2577.42 2576.78 2576.45 2576.28 2575.98 2575.92 2575.62 2575.51 2575.18 2575.01
 2574.63 2574.54 2574.61 2574.46 2574.16 2574.05 2574.22 2574.15 2573.59 2573.67
 2573.52 2573.25 2573.14 2572.73 2572.69 2572.44 2572.23 2571.43 2570.59 2570.14
 2570.12 2569.43 2568.77 2568.72  2568.8 2569.15 2570.26 2571.08 2571.22 2571.13
 2573.73 2574.13 2574.29 2574.35 2574.32 2573.95 2571.35 2571.33    2571 2570.89
  2570.9 2571.13 2571.48 2571.83 2572.83 2573.38 2574.56 2576.02 2576.81 2576.81
                                                                                
                                                                                
                                                                                
                                                                                
                 2568.47 2568.48
                                                                                
BR Coef=-1 ,-1 , 0 ,, 0 ,,,0.8,0,1.2,0,
WSPro=,,,, 1 ,,,, 0 ,,,, 0 ,,,,-1 ,-1 ,-1 , 0 , 0 , 0 , 0 , 0
BR U #Sta/Elev= 30
       0 2584.63    13.7 2578.87    32.8 2580.06    59.9 2578.96    70.8 2580.75
    87.1 2580.64    96.2 2581.83   135.4 2578.95   158.8 2577.06   201.6 2570.04
   343.2 2566.26   375.6 2566.01   409.8 2567.29   438.2 2568.16   481.4 2565.96
   549.6 2567.83   606.2 2566.47  606.33 2566.12  606.47 2562.78   606.6 2559.79
  651.14 2564.46  672.41 2562.82  673.11 2563.59   683.1 2567.36   699.3 2568.93
   873.8 2567.35   908.9 2569.38   950.1  2569.9  1010.6 2570.25  1072.8 2573.15
BR U #Mann= 8
       0     .03   135.4     .05   409.8     .04   549.6     .03  606.47     .04
  673.11     .04   950.1     .05  1010.6     .04
BR D #Sta/Elev= 30
       0 2576.51   79.51 2577.93  182.65 2575.88     196 2574.03  218.24 2567.78
  232.17  2565.9  251.38 2565.11  319.94 2565.59  372.37 2563.31   436.9 2564.04
     449  2563.3  457.07 2563.97  493.37  2564.3  553.66 2563.74   654.7 2564.96
  658.73 2564.58  664.42 2562.07  670.83 2560.61  674.86 2560.53  682.93 2560.58
  695.03 2562.06  707.26 2563.09  721.55 2562.85  731.33 2565.97  739.41 2566.28
  803.92 2564.84  896.69 2565.06  937.02 2565.92  975.17  2567.6 1097.25 2570.07
BR D #Mann= 5
       0     .05   79.51     .04  218.24     .05  664.42     .04  695.03     .05
BC Design=,, 0 ,, 0 ,,,,,,
BC Use User HTab Curves=0
BC User HTab FreeFlow(D)= 0

Type RM Length L Ch R = 1 ,129804  ,451.3,459.6,445.2
BEGIN DESCRIPTION:
Stucture XS2 - terrain is lower than survey, channel not burned
LOB IFA added to uncross profiles at this XS
END DESCRIPTION:
XS GIS Cut Line= 3
2289682.05689772464580.9885376962289781.72194804464785.517410982
2289670.37924609  465648.0945831
#Sta/Elev= 30
       0 2576.51   79.51 2577.93  182.65 2575.88     196 2574.03  218.24 2567.78
  232.17  2565.9  251.38 2565.11  319.94 2565.59  372.37 2563.31   436.9 2564.04
     449  2563.3  457.07 2563.97  493.37  2564.3  553.66 2563.74   654.7 2564.96
  658.73 2564.58  664.42 2562.07  670.83 2560.61  674.86 2560.53  682.93 2560.58
  695.03 2562.06  707.26 2563.09  721.55 2562.85  731.33 2565.97  739.41 2566.28
  803.92 2564.84  896.69 2565.06  937.02 2565.92  975.17  2567.6 1097.25 2570.07
#Mann= 5 ,-1,0
       0     .05       0   79.51     .04       0  218.24     .05       0
  664.42    .045       0  695.03     .05       0
#XS Ineff= 3 ,-1
  165.63     500    2571     500  643.37  2565.5     747 1097.25    2571
Permanent Ineff=
       F       F       F
#Block Obstruct= 1 ,-1
  453.68  467.85 2583.79
Bank Sta=664.42,695.03
XS Rating Curve= 0 ,0
Exp/Cntr(USF)=0,0
Exp/Cntr=0.5,0.3

Type RM Length L Ch R = 1 ,129344  ,293.8,365.3,357.2
XS GIS Cut Line= 4
2289482.64466721464655.4482211752289311.80508444465037.031515793
2289298.89474027465119.8728908732289203.84592394465544.184248302
#Sta/Elev= 30
       0 2570.39    58.9 2570.48    69.8 2568.74    80.8 2563.52    89.5 2559.41
    98.3 2558.39   120.2 2559.33   137.8 2558.47   155.3 2559.97   190.9 2560.79
   212.3 2559.73   225.4 2559.03   238.6 2559.48   286.8 2560.41   308.7 2558.77
   378.8 2559.85   391.9 2558.76   411.9 2560.35   438.9 2561.19     4562559.308
   482.92559.214   503.3 2558.24   523.8 2560.31     579 2559.26   597.5 2563.13
     618 2562.21   872.2 2562.17   900.9    2564   929.6 2569.84   936.7 2572.22
#Mann= 7 ,-1,0
       0     .05       0    80.8     .07       0   212.3    .045       0
   238.6     .06       0   411.9     .05       0     456    .045       0
   482.9     .05       0
#Block Obstruct= 1 ,-1
   32.99   49.64  2590.8
Bank Sta=456,482.9
XS Rating Curve= 0 ,0
Exp/Cntr(USF)=0,0
Exp/Cntr=0.3,0.1

Type RM Length L Ch R = 1 ,128979  ,92.1,93.4,94.4
Node Name=AW
XS GIS Cut Line= 3
2289212.47738239464598.2524904652288944.64529573465080.034402328
 2288932.2229402465541.518524588
#Sta/Elev= 30
       0 2573.81      20 2574.46    49.1 2572.31    58.3 2568.44      72 2558.44
    76.6 2557.52     104 2556.13   163.5 2557.43   178.9 2555.97   198.2 2555.84
   259.6 2556.07   277.9 2556.08     310  2557.6   319.1 2556.28   332.9 2556.79
   346.5 2555.56   362.8 2556.83     370 2555.78   396.5 2555.48   410.7 2556.81
   419.8 2557.82   447.3 2556.82   474.7 2559.17   520.5 2557.82   543.4 2558.67
   596.4 2557.47     922 2559.48   948.5 2561.11   984.5 2568.52  1012.9  2570.8
#Mann= 10 ,-1,0
       0     .05       0      70     .08       0     140     .07       0
   178.9    .045       0   198.2     .08       0   259.6    .045       0
   277.9     .08       0     290     .05       0   362.8    .045       0
   410.7     .05       0
#XS Ineff= 2 , 0
                          486.76         2563.44
Permanent Ineff=
       F       F
#Block Obstruct= 1 ,-1
    8.21   28.06 2593.69
Bank Sta=362.8,410.7
XS Rating Curve= 0 ,0
Exp/Cntr(USF)=0,0
Exp/Cntr=0.3,0.1

Type RM Length L Ch R = 1 ,128885  ,434.2,526.8,260.8
XS GIS Cut Line= 3
2289151.79155809464523.6694227672288775.23985318465186.400423402
2288770.93640513 465456.44178892
#Sta/Elev= 30
       0 2572.47      80 2572.28   162.8 2570.16   176.6 2566.97   181.2 2565.24
   190.4 2560.86     195 2557.53   199.6 2555.42   213.4 2554.17   236.4 2555.93
   297.1  2555.7   317.7 2554.35   347.4 2556.02  384.17 2555.58   411.5 2555.57
   429.1 2556.14   444.6 2555.16   457.2 2555.52     471 2553.97     485 2556.39
   540.6 2557.67   590.3 2556.56   613.6 2557.42     632 2556.52     701 2556.96
     785 2555.74     857 2557.06     993 2556.93    1017  2558.2  1032.3 2560.47
#Mann= 4 ,-1,0
       0     .06       0     195     .05       0  384.17    .045       0
   411.5     .05       0
#XS Ineff= 2 , 0
                          536.11         2560.21
Permanent Ineff=
       F       F
Bank Sta=384.17,411.5
XS Rating Curve= 0 ,0
Exp/Cntr(USF)=0,0
Exp/Cntr=0.3,0.1

Type RM Length L Ch R = 1 ,128359  ,276.4,340.8,228.5
XS GIS Cut Line= 2
2288730.57352754464310.925877682 2288643.3949794465426.811293794
#Sta/Elev= 30
       0 2565.74    26.3 2564.96   114.6 2566.19   186.8 2565.18     251 2561.74
   267.1 2554.36   283.1 2550.34   311.2 2551.74   327.2 2550.47   335.3 2551.65
   351.3 2552.33   363.52551.003   375.4 2550.04   400.2 2551.02   407.5 2552.08
   431.6 2551.94   439.6 2552.89   535.2  2551.6     560 2552.79   612.1 2551.72
   632.2 2550.23   644.2 2551.57   668.3  2552.5   680.3 2554.49   708.4 2555.11
   801.1 2553.72   937.1 2555.41   989.3 2555.07  1057.5 2555.91  1119.3 2555.33
#Mann= 5 ,-1,0
       0     .05       0     150     .08       0   363.5    .045       0
   400.2     .08       0     540     .05       0
Bank Sta=363.5,400.2
XS Rating Curve= 0 ,0
Exp/Cntr(USF)=0,0
Exp/Cntr=0.3,0.1

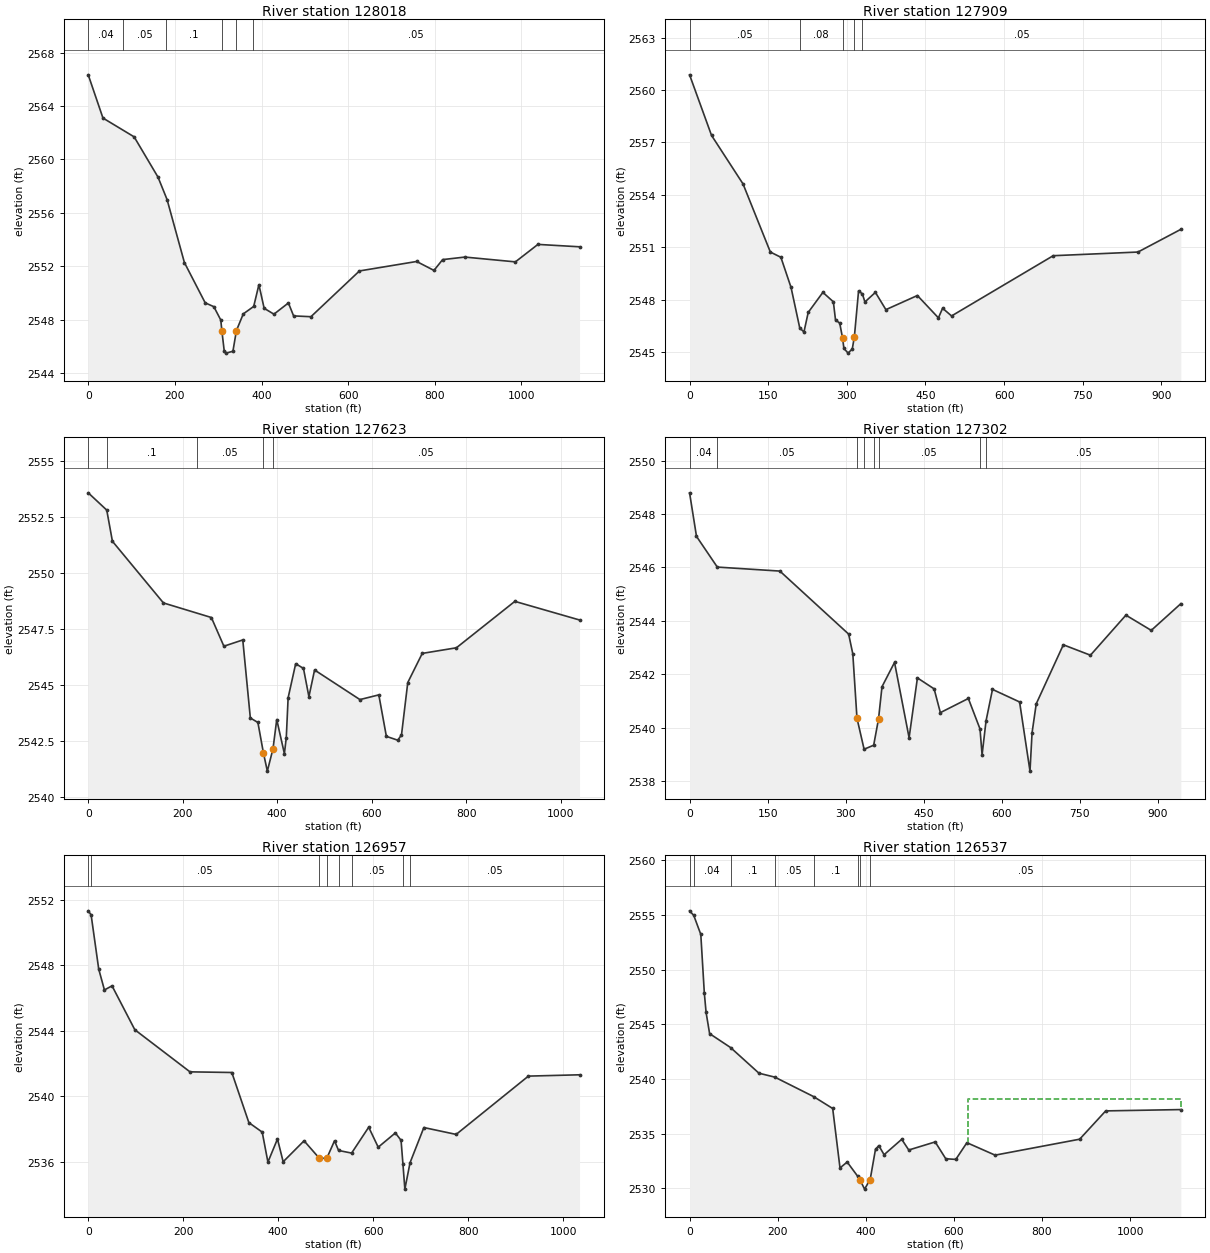
Type RM Length L Ch R = 1 ,128018  ,105.1,108.9,116.6
XS GIS Cut Line= 2
2288485.95375447464183.184934986 2288467.0989082465317.169260894
#Sta/Elev= 30
       0 2566.34      34  2563.1     106 2561.69   161.1 2558.67     182 2556.99
     222 2552.27     270 2549.25     290 2548.96     306 2547.96   308.52547.147
     314 2545.63     318 2545.48     334 2545.62   342.1 2547.17   357.9 2548.42
     382 2548.98     394 2550.61   406.1 2548.84   428.7  2548.4   462.1 2549.24
   474.1 2548.27   514.1 2548.21   626.1 2551.64   758.1 2552.35   798.1 2551.68
   818.1 2552.49   869.4 2552.68   986.1 2552.32  1038.1 2553.63  1134.1 2553.45
#Mann= 6 ,-1,0
       0     .04       0      80     .05       0     180      .1       0
   308.5    .045       0   342.1      .1       0     380     .05       0
Bank Sta=308.5,342.1
XS Rating Curve= 0 ,0
Exp/Cntr(USF)=0,0
Exp/Cntr=0.3,0.1

Type RM Length L Ch R = 1 ,127909  ,275.4,285.5,263.1
XS GIS Cut Line= 2
2288391.26807691464223.3267699652288334.90390588465158.841263069
#Sta/Elev= 30
       0 2560.87    41.9  2557.4     102 2554.62   154.1 2550.72   174.2 2550.42
   193.6 2548.69   210.2 2546.37   218.2 2546.14   226.3 2547.26   254.3 2548.41
   274.3 2547.87   278.4 2546.83   286.4 2546.65   291.9 2545.79   294.4  2545.2
   302.4 2544.93   310.4 2545.17   314.4 2545.87   322.4  2548.5   329.7 2548.32
   334.5 2547.86   354.5 2548.41   374.5 2547.42   434.6 2548.23   474.7 2546.95
   482.7  2547.5   499.8 2547.06   693.7 2550.51   855.4 2550.72   937.2 2552.02
#Mann= 5 ,-1,0
       0     .05       0   210.2     .08       0   291.9    .045       0
   314.4     .08       0   329.7     .05       0
Bank Sta=291.9,314.4
XS Rating Curve= 0 ,0
Exp/Cntr(USF)=0,0
Exp/Cntr=0.3,0.1

Type RM Length L Ch R = 1 ,127623  ,309.5,321.3,315.3
XS GIS Cut Line= 2
2288104.31156502 464137.982460382288093.78143649465178.036496261
#Sta/Elev= 30
       0 2553.57    39.2  2552.8    51.2 2551.41   159.2 2548.66   260.7 2548.01
   287.2 2546.73   327.2 2547.01   343.2 2543.53   359.2 2543.33   370.82541.984
   379.2 2541.16   391.2 2542.16   399.1 2543.46   415.3 2541.94   419.3 2542.65
   423.2 2544.43   439.2 2545.95   455.7 2545.74   467.2 2544.48   479.2 2545.67
   575.2 2544.35   615.2 2544.56   631.2 2542.71   655.2 2542.54   663.2 2542.77
   676.5 2545.11   707.2 2546.41   779.5 2546.66   903.2 2548.73  1040.1  2547.9
#Mann= 5 ,-1,0
       0     .05       0      40      .1       0     230     .05       0
   370.8    .045       0   391.2     .05       0
Bank Sta=370.8,391.2
XS Rating Curve= 0 ,0
Exp/Cntr(USF)=0,0
Exp/Cntr=0.3,0.1

Type RM Length L Ch R = 1 ,127302  ,336.3,345.4,311.9
XS GIS Cut Line= 2
2287817.95348648464123.9268466962287761.38894766465066.669160396
#Sta/Elev= 30
       0 2548.79    13.3 2547.16    53.3 2546.01   173.6 2545.86   305.8  2543.5
   313.8 2542.76   321.8 2540.35   335.5 2539.19   353.9 2539.34   363.22540.319
   369.9 2541.53     394 2542.44     422 2539.62     438 2541.86   470.1 2541.45
   482.1 2540.56   535.9 2541.09   558.3 2539.95   562.3 2538.98   569.9 2540.25
   582.3 2541.43   634.4 2540.96   654.4 2538.37   658.4 2539.81   666.4 2540.89
   718.5  2543.1   770.6 2542.71   838.8 2544.21   887.5 2543.64   944.4 2544.64
#Mann= 8 ,-1,0
       0     .04       0    53.3     .05       0   321.8    .045       0
   335.5     .05       0   353.9    .045       0   363.2     .05       0
   558.3    .045       0   569.9     .05       0
Bank Sta=321.8,363.2
XS Rating Curve= 0 ,0
Exp/Cntr(USF)=0,0
Exp/Cntr=0.3,0.1

Type RM Length L Ch R = 1 ,126957  ,362.3,419.9,356.4
XS GIS Cut Line= 2
2287455.41174166464039.1050006932287494.85995057465072.621926143
#Sta/Elev= 30
       0 2551.31     6.1 2551.06    22.1 2547.75    34.1 2546.48    50.1 2546.73
    98.1 2544.05   214.2 2541.48   302.3 2541.44   338.2 2538.38   366.3  2537.8
   378.3 2535.97   398.4 2537.38   410.4 2535.99   454.4 2537.27   486.4 2536.21
  502.18  2536.2   518.5 2537.27   527.1 2536.68   554.5 2536.52   590.5  2538.1
   610.5 2536.88   646.6 2537.75   658.6  2537.3   662.6 2535.84   666.6 2534.32
   677.5 2535.93   706.6 2538.08   774.6 2537.66   926.7 2541.22  1034.3  2541.3
#Mann= 8 ,-1,0
       0    .016       0     6.1     .05       0   486.4    .045       0
  502.18     .05       0   527.1    .045       0   554.5     .05       0
   662.6    .045       0   677.5     .05       0
Bank Sta=486.4,502.18
XS Rating Curve= 0 ,0
Exp/Cntr(USF)=0,0
Exp/Cntr=0.3,0.1

Type RM Length L Ch R = 1 ,126537  ,473.3,467.6,409.9
Node Name=AV
XS GIS Cut Line= 2
2287123.53909727463983.6557718682287137.35025949465098.907120783
#Sta/Elev= 30
       0 2555.39     9.5 2554.97    25.5 2553.23    33.5 2547.86    37.5 2546.09
    45.5 2544.15      93 2542.88   157.5 2540.53   193.5 2540.17   281.5 2538.39
   324.9  2537.3   341.5 2531.86   357.8  2532.4   381.6  2531.1   387.42530.728
   397.3 2529.92     410  2530.8   422.1 2533.57   429.6  2533.9   441.6 2533.07
   481.6 2534.48   497.6  2533.5   557.6 2534.24   581.6  2532.7   604.4 2532.64
   629.6 2534.17   693.6 2533.03   885.6 2534.49   944.7 2537.08  1115.3  2537.2
#Mann= 8 ,-1,0
       0    .016       0     9.5     .04       0      93      .1       0
   193.5     .05       0   281.5      .1       0   381.6     .05       0
   387.4    .045       0     410     .05       0
#XS Ineff= 2 , 0
                           631.3         2538.13
Permanent Ineff=
       F       F
Bank Sta=387.4,410
XS Rating Curve= 0 ,0
Exp/Cntr(USF)=0,0
Exp/Cntr=0.3,0.1

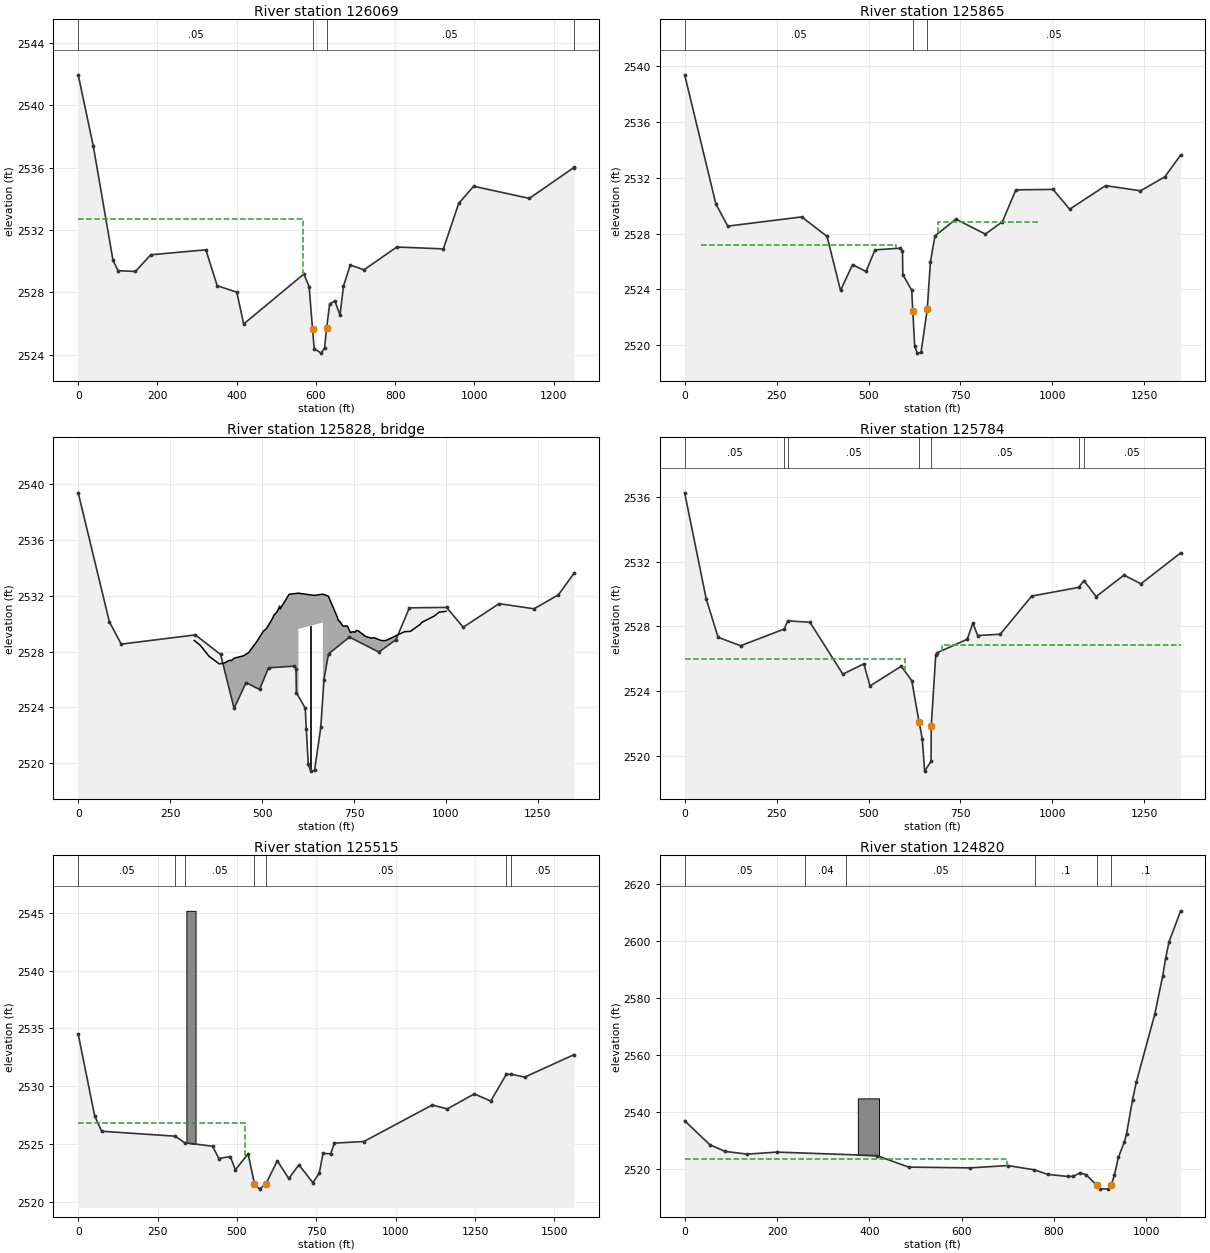
Type RM Length L Ch R = 1 ,126069  ,188.7,203.8,203.4
BEGIN DESCRIPTION:
structure xs 4
END DESCRIPTION:
XS GIS Cut Line= 2
2286481.32005424464004.3725151922286968.16352234  465157.6045602
#Sta/Elev= 30
       0 2541.96    38.2 2537.37    87.7 2530.07   100.5 2529.39   144.2 2529.34
   183.2 2530.41   322.2 2530.73   350.8 2528.43   400.3 2528.01   417.7 2525.97
   569.7 2529.18   582.9 2528.36   591.52525.624   595.7 2524.39   613.1  2524.1
   621.8 2524.43   627.12525.734   634.7 2527.25   647.8 2527.45   660.8 2526.54
   669.5  2528.4   686.7 2529.75   721.6 2529.45   804.1 2530.91   921.7 2530.79
   960.4 2533.71   998.1 2534.81  1138.7 2534.03    1251 2536.01  1251.8 2536.03
#Mann= 4 ,-1,0
       0     .05       0   591.5    .045       0   627.1     .05       0
    1251     .04       0
#XS Ineff= 2 , 0
           567.1 2532.69
Permanent Ineff=
       F       F
Bank Sta=591.5,627.1
XS Rating Curve= 0 ,0
Exp/Cntr(USF)=0,0
Exp/Cntr=0.5,0.3

Type RM Length L Ch R = 1 ,125865  ,81.4,81,78.5
BEGIN DESCRIPTION:
Structure XS 3 - channel burned within banks
END DESCRIPTION:
XS GIS Cut Line= 4
2286439.54128854464005.0630733022286483.04644952464365.534407131
2286613.56193246465036.7568908122286868.37787534465198.347488736
#Sta/Elev= 30
       0 2539.38    84.7 2530.14     117 2528.54   318.4  2529.2   387.2  2527.8
   423.8 2523.93   456.4 2525.78   493.1 2525.29   517.6 2526.84   586.8 2526.96
   592.3 2526.79  593.13 2525.07  617.35 2523.95   620.3 2522.43  625.55 2519.93
  632.42 2519.44  642.69 2519.49   659.6 2522.57   668.3 2525.99   680.6 2527.84
   737.6 2529.04   817.5 2527.97   863.9 2528.85   900.6 2531.14  1001.7 2531.17
  1046.9 2529.75  1144.6 2531.44  1239.4 2531.07  1305.7 2532.07  1348.6 2533.63
#Mann= 3 ,-1,0
       0     .05       0   620.3    .045       0   659.6     .05       0
#XS Ineff= 2 ,-1
   44.17     575 2527.18     690  966.99  2528.8
Permanent Ineff=
       F       F
Bank Sta=620.3,659.6
XS Rating Curve= 0 ,0
Exp/Cntr(USF)=0,0
Exp/Cntr=0.5,0.3

Type RM Length L Ch R = 3 ,125828  ,,,
BEGIN DESCRIPTION:
Unnamed Road- Wooden Bridge
Bridge data: 54075KNA110
Width: 12' (measured on orthoimagery)
Rectangular Pier width: 2'
Structure bounding sections incorporate channel data from survey.
Deck from Lidar with survey data incorporated
END DESCRIPTION:
Bridge Culvert--1,0,-1,-1, 0
Deck Dist Width WeirC Skew NumUp NumDn MinLoCord MaxHiCord MaxSubmerge Is_Ogee
28.5,12,2.6,0, 45, 39, , , 0.98, 0, 0,0,,
   315.6  331.66  355.74  383.68  396.86  411.95  415.97  423.87  449.05  463.02
  486.33   502.9  511.97  528.28   531.9  541.33  547.86     549  573.47  598.84
  641.39  665.23  680.08  704.85  707.22  711.77   719.9  732.08  740.21   745.6
  752.39  756.46  760.52   780.7   796.7  804.71  824.72  836.73   887.5  903.17
  930.23  934.53  968.03  981.56 1000.56
  2528.8 2528.46 2527.67 2527.12 2527.18 2527.39 2527.35 2527.53  2527.7 2527.92
 2528.75 2529.45 2529.66 2530.37  2530.6 2530.88 2531.27 2531.06 2532.11 2532.19
 2532.03 2532.12 2531.98 2530.46 2530.23 2530.16 2529.83 2529.84 2529.36 2529.43
 2529.39 2529.51 2529.51  2529.1 2528.97    2529 2528.79  2528.8 2529.43 2529.45
 2529.96  2530.1 2530.55 2530.83 2530.89
                                                                                
                                                                         2529.63
 2529.92 2530.09
                                                                                
                                        
   329.7  374.03  382.74  410.68  423.86  438.95  442.97  450.87  476.05  490.02
  513.33   529.9  538.97  555.28   558.9  568.33  574.86     576  600.47  625.84
  668.39  692.23  707.08  731.85  734.22  738.77   746.9  759.08  767.21   772.6
  779.39  783.46  787.52   807.7   823.7  831.71  843.72  859.72     920
 2528.25 2527.96 2527.67 2527.12 2527.18 2527.39 2527.35 2527.53  2527.7 2527.92
 2528.75 2529.45 2529.66 2530.37  2530.6 2530.88 2531.27 2531.06 2532.11 2532.19
 2532.03 2532.12 2531.98 2530.46 2530.23 2530.16 2529.83 2529.84 2529.36 2529.43
 2529.39 2529.51 2529.51  2529.1 2528.97    2529 2528.83 2528.79 2529.47
                                                                                
                                                                         2529.63
 2529.92 2530.09
                                                                        
Pier Skew, UpSta & Num, DnSta & Num=  ,632, 2 ,659, 2 , 0 , 0 , 0 ,,
       2       2
 2519.93    2530
       2       2
 2521.03    2530
BR Coef=-1 ,-1 , 0 ,1.25, 0 ,,,0.8,0,2,0,
WSPro=,,,, 1 ,,,, 0 ,,,, 0 ,,,,-1 ,-1 ,-1 , 0 , 0 , 0 , 0 , 0
BR U #Sta/Elev= 30
       0 2539.38    84.7 2530.14     117 2528.54   318.4  2529.2   387.2  2527.8
   423.8 2523.93   456.4 2525.78   493.1 2525.29   517.6 2526.84   586.8 2526.96
   592.3 2526.79  593.13 2525.07  617.35 2523.95   620.3 2522.43  625.55 2519.93
  632.42 2519.44  642.69 2519.49   659.6 2522.57   668.3 2525.99   680.6 2527.84
   737.6 2529.04   817.5 2527.97   863.9 2528.85   900.6 2531.14  1001.7 2531.17
  1046.9 2529.75  1144.6 2531.44  1239.4 2531.07  1305.7 2532.07  1348.6 2533.63
BR U #Mann= 3
       0     .05   620.3     .04   659.6     .05
BR D #Sta/Elev= 30
       0 2536.26    58.5  2529.7    90.9 2527.32     152  2526.8   270.6 2527.83
   280.3 2528.34   340.7 2528.25   430.1 2525.04   487.2 2525.68   503.9 2524.31
     589 2525.53   617.6 2524.63  637.15 2522.11  646.17 2521.03   652.5 2519.04
  669.92 2519.64  670.54 2521.85  682.77 2526.24  686.08 2526.36   768.3  2527.2
   783.7 2528.19   796.9 2527.43     858 2527.51   943.6 2529.87  1071.5 2530.41
  1085.7 2530.83  1118.8 2529.84  1194.6 2531.17  1240.6 2530.63  1348.6 2532.54
BR D #Mann= 7
       0     .05   270.6    .016   280.3     .05  637.15     .04  670.54     .05
  1071.5    .016  1085.7     .05
BC Design=,, 0 ,, 0 ,,,,,,
BC Use User HTab Curves=0
BC User HTab FreeFlow(D)= 0

Type RM Length L Ch R = 1 ,125784  ,254,269.7,263.7
BEGIN DESCRIPTION:
Structure XS 2 - channel burned within banks
END DESCRIPTION:
XS GIS Cut Line= 4
2286357.36487336463990.9066320312286400.87003433 464351.37796586
2286531.38551727465022.6004495412286786.20146015465184.191047465
#Sta/Elev= 30
       0 2536.26    58.5  2529.7    90.9 2527.32     152  2526.8   270.6 2527.83
   280.3 2528.34   340.7 2528.25   430.1 2525.04   487.2 2525.68   503.9 2524.31
     589 2525.53   617.6 2524.63  637.15 2522.11  646.17 2521.03   652.5 2519.04
  669.92 2519.64  670.54 2521.85  682.77 2526.24  686.08 2526.36   768.3  2527.2
   783.7 2528.19   796.9 2527.43     858 2527.51   943.6 2529.87  1071.5 2530.41
  1085.7 2530.83  1118.8 2529.84  1194.6 2531.17  1240.6 2530.63  1348.6 2532.54
#Mann= 7 ,-1,0
       0     .05       0   270.6    .016       0   280.3     .05       0
  637.15    .045       0  670.54     .05       0  1071.5    .016       0
  1085.7     .05       0
#XS Ineff= 2 , 0
          598.65 2525.95  699.09         2526.85
Permanent Ineff=
       F       F
Bank Sta=637.15,670.54
XS Rating Curve= 0 ,0
Exp/Cntr(USF)=0,0
Exp/Cntr=0.5,0.3

Type RM Length L Ch R = 1 ,125515  ,392.7,694.1,629.3
BEGIN DESCRIPTION:
structure xs 1
END DESCRIPTION:
XS GIS Cut Line= 4
2286342.59372973463997.8086970562286211.85998303464292.073940618
2286200.73370671464868.4398187472286762.61066064465221.699091765
#Sta/Elev= 30
       0 2534.51    51.8 2527.44    73.7 2526.11   305.7 2525.68   335.1 2525.12
   423.1 2524.81   443.1 2523.75   479.1 2523.92   495.1 2522.77   535.1 2524.15
   555.1 2521.58   571.2  2521.1   591.32521.559   627.2 2523.55   663.2 2522.02
   695.2  2523.2   739.2 2521.66   759.2 2522.48   771.2 2524.19   795.2 2524.16
   807.2 2525.08   899.9 2525.22  1115.2 2528.38  1162.6 2528.04  1247.5 2529.34
  1299.4 2528.72  1348.3 2531.02  1362.8 2531.05  1406.3 2530.79  1562.2 2532.74
#Mann= 7 ,-1,0
       0     .05       0   305.7    .016       0   335.1     .05       0
   555.1    .045       0   591.3     .05       0  1348.3    .016       0
  1362.8     .05       0
#XS Ineff= 2 , 0
          525.52 2526.86
Permanent Ineff=
       F       F
#Block Obstruct= 1 ,-1
  340.71  369.59 2545.18
Bank Sta=555.1,591.3
XS Rating Curve= 0 ,0
Exp/Cntr(USF)=0,0
Exp/Cntr=0.3,0.1

Type RM Length L Ch R = 1 ,124820  ,529.1,507,504
XS GIS Cut Line= 3
2286335.40810812463971.6434162612285951.14141113464556.356051054
2285609.07254052464708.971393325
#Sta/Elev= 30
       0 2536.93    54.5 2528.51      88 2526.16   135.9 2525.22   199.8 2525.94
   416.5 2524.69   485.3 2520.67   618.7  2520.4   699.7 2521.21   757.1 2519.72
   786.1 2518.13   829.3 2517.39   841.9 2517.44   856.2 2518.65   869.4 2517.99
   892.7 2514.28     900 2513.06   917.5 2512.94   923.92514.436   930.7 2517.77
   939.4  2524.1   952.6  2529.6     957 2532.32   970.1 2544.34   978.2 2550.46
  1018.3 2574.36  1035.5 2587.86  1041.8    2594    1049 2599.67  1074.2  2610.6
#Mann= 6 ,-1,0
       0     .05       0     260     .04       0     350     .05       0
  759.68      .1       0   892.7    .045       0   923.9      .1       0
#XS Ineff= 2 , 0
          698.21 2523.46
Permanent Ineff=
       F       F
#Block Obstruct= 1 ,-1
     375  420.96 2544.79
Bank Sta=892.7,923.9
XS Rating Curve= 0 ,0
Exp/Cntr(USF)=0,0
Exp/Cntr=0.3,0.1

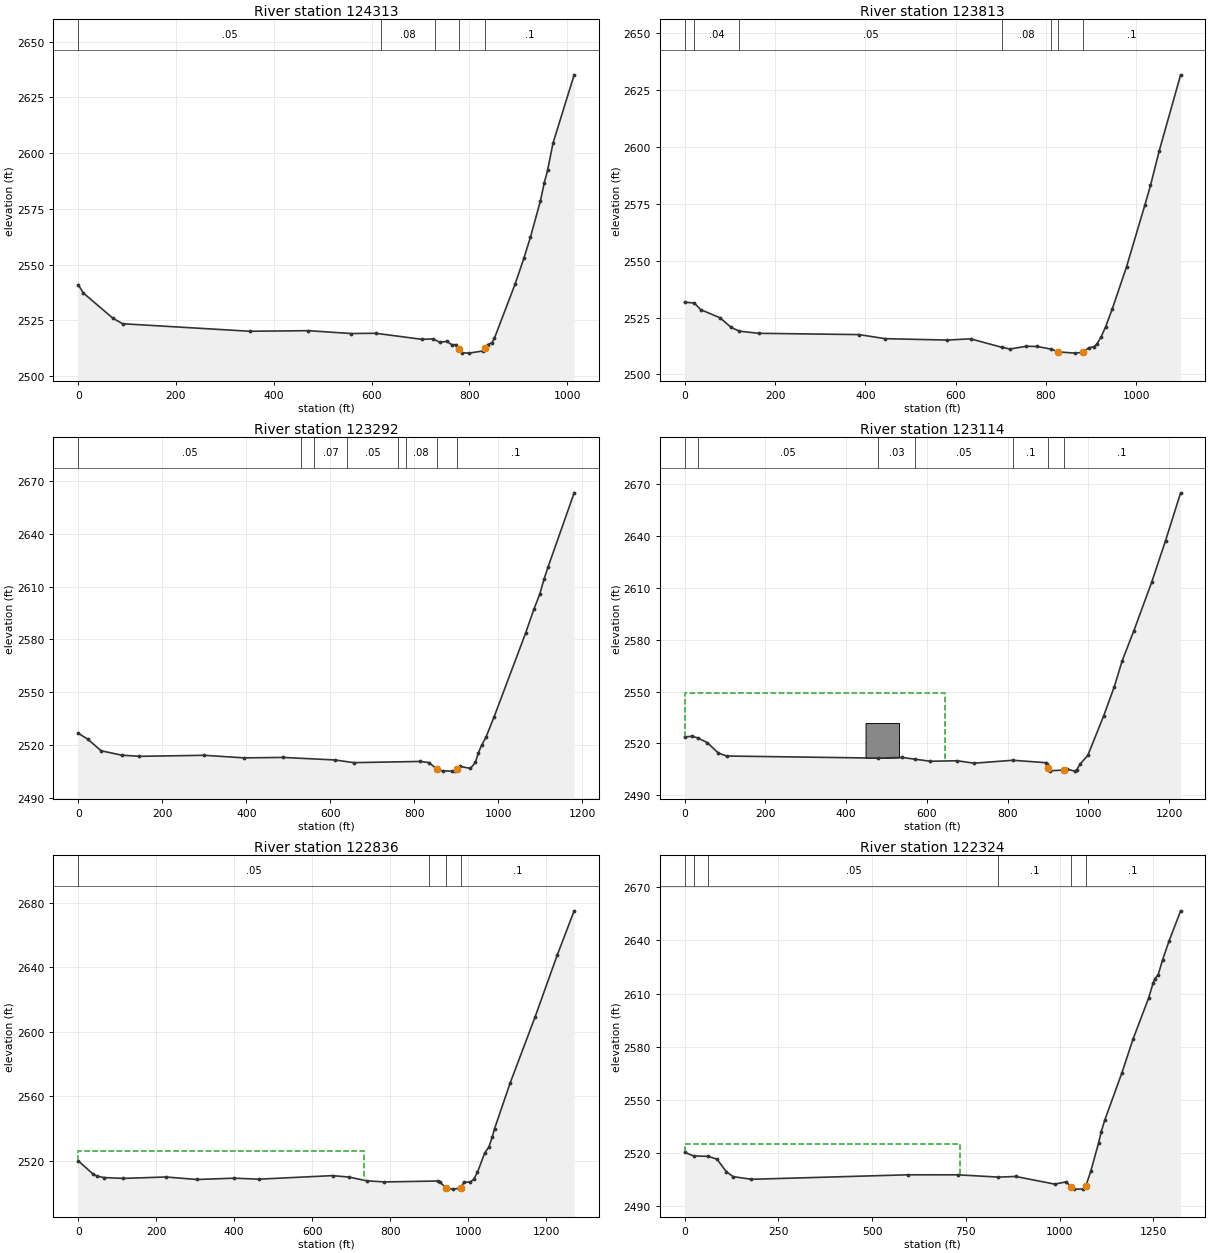
Type RM Length L Ch R = 1 ,124313  ,504.4,500.6,499.5
Node Name=AU
XS GIS Cut Line= 2
2286225.49804226 463780.015123312285351.65777086464295.127223593
#Sta/Elev= 30
       0 2541.02    10.6 2537.27    71.2 2525.94    90.9 2523.51   351.1 2520.14
   470.5  2520.4   558.7 2519.12   608.8 2519.23   702.9 2516.52   725.9 2516.73
   739.8 2515.16   753.7 2515.62   764.3 2514.11     773 2514.13   778.22512.169
   784.7  2510.5   799.3 2510.33     828 2511.31   831.4 2512.41   837.3 2514.16
   846.6 2515.06   851.3 2517.02     894 2541.53   911.6 2552.91   924.9 2562.27
   945.4  2578.6   953.4 2586.86     960 2592.25   971.1 2604.49  1014.4 2635.16
#Mann= 5 ,-1,0
       0     .05       0     620     .08       0     730      .1       0
   778.2    .045       0   831.4      .1       0
Bank Sta=778.2,831.4
XS Rating Curve= 0 ,0
Exp/Cntr(USF)=0,0
Exp/Cntr=0.3,0.1

Type RM Length L Ch R = 1 ,123813  ,509.3,520.7,524.4
XS GIS Cut Line= 2
2285990.12967206463304.8872913582285063.91242241463894.298268402
#Sta/Elev= 30
       0 2531.76    21.3  2531.4    35.5 2528.49    78.2 2524.92     103 2520.66
   120.8 2519.04   163.5 2518.09   386.4 2517.52   443.3 2515.74   580.7 2515.12
   632.9 2515.66   702.8  2511.9   720.2  2511.2   756.2 2512.39   779.9 2512.31
     810 2511.19   827.3 2509.91   864.8 2509.38   882.4 2509.76   894.6 2511.76
   905.6 2512.11   912.6 2513.37   922.1 2516.61   931.9 2520.96   946.8 2528.94
   978.1 2547.26  1018.6 2574.35  1031.2 2583.06  1050.5 2598.24  1097.9 2631.67
#Mann= 7 ,-1,0
       0    .016       0    21.3     .04       0   120.8     .05       0
   702.8     .08       0     810      .1       0   827.3    .045       0
   882.4      .1       0
Bank Sta=827.3,882.4
XS Rating Curve= 0 ,0
Exp/Cntr(USF)=0,0
Exp/Cntr=0.3,0.1

Type RM Length L Ch R = 1 ,123292  ,183.4,178.3,174.5
XS GIS Cut Line= 2
2285776.60417034462926.071176499 2284725.1596059 463462.31269884
#Sta/Elev= 30
       0 2526.69    22.9 2523.28    54.4 2516.71   103.7 2514.19   145.4 2513.55
     300 2514.12   395.1 2512.66   487.3 2512.91   611.1 2511.47     656 2509.95
   814.4 2510.63   835.2 2509.96   852.92506.364   867.1 2505.24   889.5 2505.12
   896.1 2505.33   900.7 2506.47   907.5 2507.86   933.4 2506.67   945.3 2510.09
   952.4 2515.59   960.1 2519.85   970.4 2524.37   989.9 2536.08  1064.7 2583.56
  1084.3 2597.09  1098.6 2605.87  1108.8 2614.46  1118.5 2621.39  1180.3 2663.41
#Mann= 8 ,-1,0
       0     .05       0     530      .1       0     560     .07       0
     640     .05       0     760      .1       0     780     .08       0
   852.9    .045       0   900.7      .1       0
Bank Sta=852.9,900.7
XS Rating Curve= 0 ,0
Exp/Cntr(USF)=0,0
Exp/Cntr=0.3,0.1

Type RM Length L Ch R = 1 ,123114  ,278.3,277.4,271.9
XS GIS Cut Line= 2
2285704.11337155462698.9969969342284646.26159605463324.194191874
#Sta/Elev= 30
       0 2523.73    18.5 2524.06    32.5 2523.12    55.7 2520.42    83.6 2514.35
   103.8 2512.64   478.5 2511.42   538.9 2511.81   570.3 2510.81   608.6 2509.59
   675.3 2509.89     717 2508.47     813 2510.18   895.2 2508.77   898.1 2508.12
   901.3 2505.79     906 2504.09     939 2504.51   947.9 2505.03   966.4 2503.88
     971 2504.53   980.3 2508.12   998.9 2513.04  1038.3    2536  1064.6 2552.86
  1084.2 2567.92  1112.8 2585.15  1156.9  2613.2  1191.4 2637.41  1228.8 2665.12
#Mann= 7 ,-1,0
       0    .016       0    32.5     .05       0   478.5     .03       0
   570.3     .05       0     813      .1       0   901.3    .045       0
     939      .1       0
#XS Ineff= 2 , 0
          645.78 2549.17
Permanent Ineff=
       F       F
#Block Obstruct= 1 ,-1
  448.08  531.11 2531.72
Bank Sta=901.3,939
XS Rating Curve= 0 ,0
Exp/Cntr(USF)=0,0
Exp/Cntr=0.3,0.1

Type RM Length L Ch R = 1 ,122836  ,472.7,512.1,519.5
XS GIS Cut Line= 2
2285567.96776386462417.5911844132284499.66036797463106.991523634
#Sta/Elev= 30
       0 2520.08    37.8  2511.9    48.7 2510.51    66.1 2509.69   115.3 2509.16
   225.2 2510.03   304.4 2508.48   399.6  2509.3   462.5 2508.68     652 2510.88
     694 2509.99   740.3 2507.65   785.2 2506.97   921.4 2507.54   928.1 2506.73
   943.32503.178   960.2 2502.51   980.4 2503.07   989.1 2506.96  1004.2 2506.79
  1013.8 2508.51  1023.3 2512.84  1042.3 2525.02  1052.7 2528.54  1061.4  2534.8
  1067.2  2539.9  1107.7 2568.56  1170.9 2609.02    1228 2647.59  1271.4 2675.04
#Mann= 4 ,-1,0
       0     .05       0     900      .1       0   943.3    .045       0
   980.4      .1       0
#XS Ineff= 2 , 0
          732.53 2526.34
Permanent Ineff=
       F       F
Bank Sta=943.3,980.4
XS Rating Curve= 0 ,0
Exp/Cntr(USF)=0,0
Exp/Cntr=0.3,0.1

Type RM Length L Ch R = 1 ,122324  ,155.1,156.1,156.8
XS GIS Cut Line= 2
2285506.88804318462203.4260762162284238.22624389462577.829452228
#Sta/Elev= 30
       0 2520.51    23.7 2518.51    62.7 2518.24    86.2 2516.67   111.3 2509.54
   129.2 2506.83     178 2505.32     595 2507.85   728.5 2507.84   836.9 2506.56
   882.7 2506.91   987.1  2502.6    1018  2503.9  1030.7  2500.9  1037.1 2499.78
  1062.1 2499.81  1069.5 2501.29    1083 2509.75  1103.9 2525.75  1111.3 2532.25
  1120.5 2538.71  1166.4 2565.43  1195.6 2584.16  1237.3 2607.36  1249.8 2616.16
    1254 2618.34  1262.7 2620.43  1274.8 2629.04  1291.5 2639.33  1322.8  2656.6
#Mann= 6 ,-1,0
       0      .1       0    23.7    .016       0    62.7     .05       0
   836.9      .1       0  1030.7    .045       0  1069.5      .1       0
#XS Ineff= 2 , 0
          734.31    2525
Permanent Ineff=
       F       F
Bank Sta=1030.7,1069.5
XS Rating Curve= 0 ,0
Exp/Cntr(USF)=0,0
Exp/Cntr=0.3,0.1