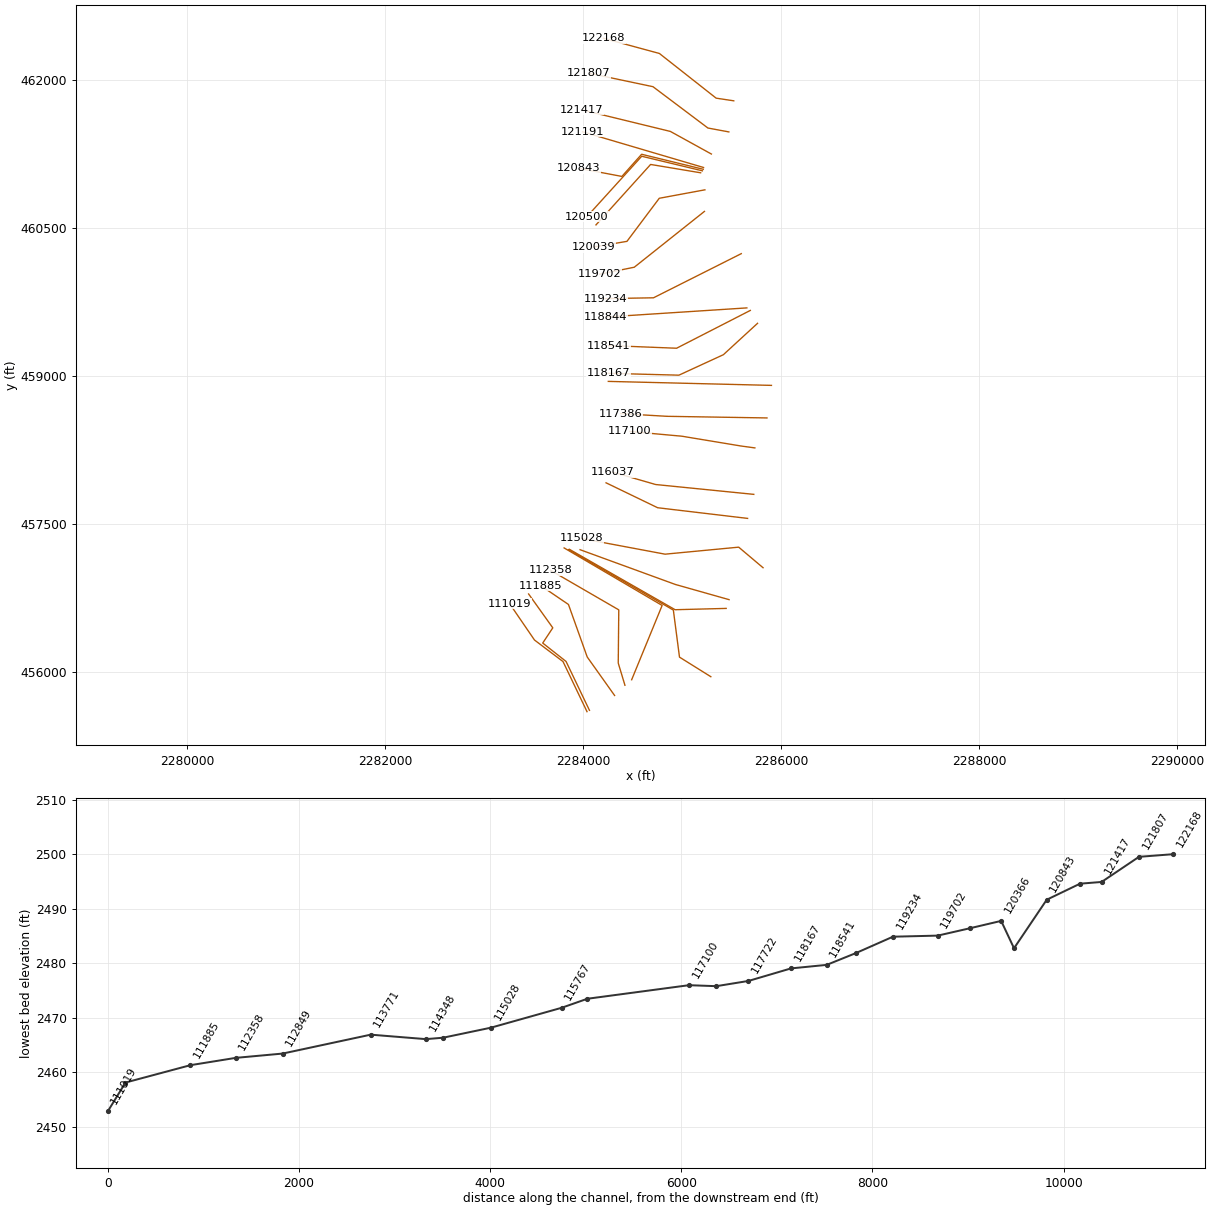
HEC-RAS study KNAPPCK.prj: KNAPPCK

--- KNAPPCK.g01 (geometry) --- (continued)

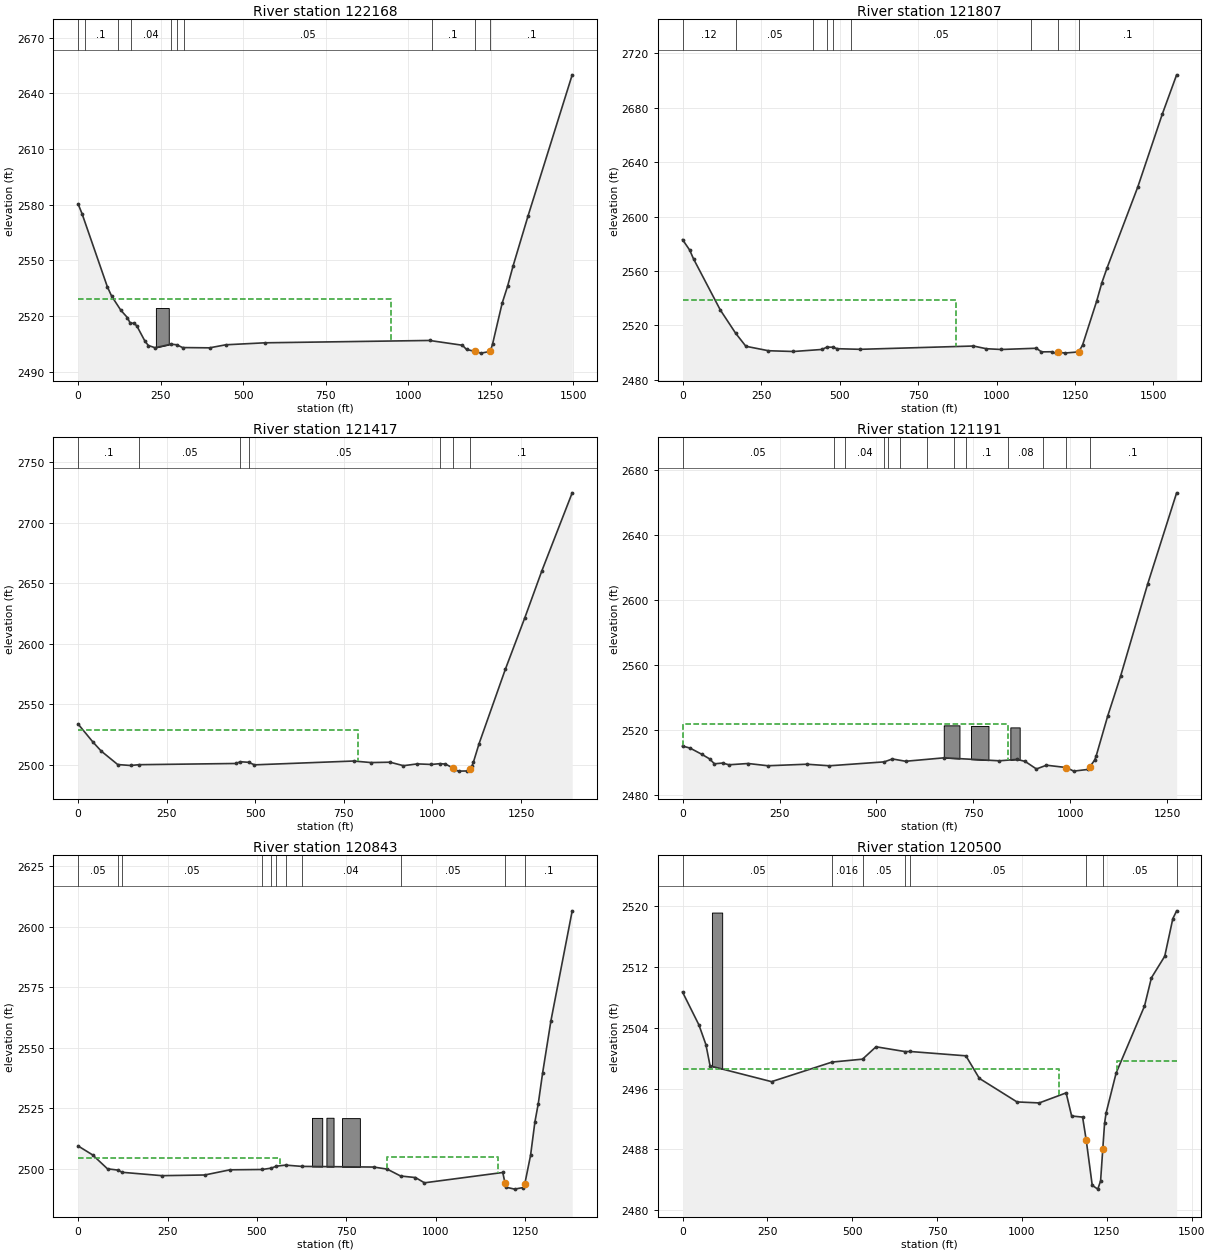
Type RM Length L Ch R = 1 ,122168  ,355.1,360.7,362.8
Node Name=AT
XS GIS Cut Line= 4
 2285519.8858194461785.5609939342285341.99812278461812.582589621
2284768.85548902462265.3777139732284203.46086833462419.413227398
#Sta/Elev= 30
       0 2580.35    11.8 2575.16    88.7 2535.68   101.3 2530.81   129.4 2523.12
   149.4 2519.14   157.5 2516.22   169.6 2516.09   177.7 2514.73   202.6 2506.41
   212.8 2504.14   233.2 2502.95   281.3 2504.87   298.4 2504.54   316.4 2503.04
   398.1 2502.89   447.3 2504.53   566.1  2505.6  1064.4 2506.86  1163.9 2504.28
  1176.4 2502.01  1200.82501.023  1220.3 2500.04  1248.52500.978  1255.2 2504.92
  1284.2 2526.91  1300.8 2536.13  1317.3 2546.97  1362.9 2574.06  1496.4  2649.9
#Mann= 10 ,-1,0
       0     .12       0      20      .1       0     120     .03       0
     160     .04       0  279.93    .016       0   298.4     .04       0
  319.93     .05       0 1070.35      .1       0  1200.8    .045       0
  1248.5      .1       0
#XS Ineff= 2 , 0
          948.28 2529.15
Permanent Ineff=
       F       F
#Block Obstruct= 1 ,-1
  235.55  274.55 2524.32
Bank Sta=1200.8,1248.5
XS Rating Curve= 0 ,0
Exp/Cntr(USF)=0,0
Exp/Cntr=0.3,0.1

Type RM Length L Ch R = 1 ,121807  ,391.4,390.6,388.5
XS GIS Cut Line= 4
2285470.44199112 461470.514591422285258.86387995461509.973945717
 2284704.2103018461928.6840305092284055.06488008462066.055053362
#Sta/Elev= 30
       0 2583.03    22.7 2575.34    34.9  2568.9   120.3 2531.28   169.1  2514.2
   201.7 2504.59   273.7 2501.31   353.3 2500.75   444.1 2502.25   459.5 2503.94
   479.2 2503.91   492.7  2502.8   565.8 2502.35   926.6 2504.78   967.5 2502.79
  1015.2 2502.23  1126.9 2503.14  1143.3 2500.46    1176 2500.57  1188.2 2499.55
  1196.4 2500.25  1217.7 2499.63  1261.8 2500.44  1274.1  2505.5  1319.1 2537.84
  1335.4 2551.19  1351.8 2562.02  1449.9 2621.69  1527.6 2675.04  1573.7 2704.21
#Mann= 9 ,-1,0
       0     .12       0     170     .05       0  415.23     .03       0
   459.5    .016       0   479.2     .03       0  535.23     .05       0
 1110.18     .08       0  1196.4    .045       0  1261.8      .1       0
#XS Ineff= 2 , 0
          871.66 2538.57
Permanent Ineff=
       F       F
Bank Sta=1196.4,1261.8
XS Rating Curve= 0 ,0
Exp/Cntr(USF)=0,0
Exp/Cntr=0.3,0.1

Type RM Length L Ch R = 1 ,121417  ,237.4,226.1,225.1
XS GIS Cut Line= 3
2285293.93636395461246.4739686392284880.06535856461475.411152578
2283985.03259392461694.345226818
#Sta/Elev= 30
       0 2533.81    41.5 2519.06    65.1 2511.52   111.7 2500.38   148.3 2499.59
   171.1 2500.25   444.8 2501.25   457.9 2502.68   481.3 2502.23   497.5 2500.13
   777.6 2503.28     827 2502.01   880.5 2502.31   918.1 2499.43   957.4 2500.91
   997.1 2500.45    1021 2501.11  1036.8 2500.76    10592497.331  1061.7 2496.11
  1074.1 2494.94  1098.8 2495.09  1107.22497.107  1111.1    2499  1115.3 2502.08
  1131.7 2517.75  1205.5 2578.87  1260.9 2621.76  1308.8 2660.35  1394.4 2724.73
#Mann= 7 ,-1,0
       0      .1       0   171.1     .05       0   457.9    .016       0
   481.3     .05       0    1021      .1       0    1059    .045       0
  1107.2      .1       0
#XS Ineff= 2 , 0
          788.73 2528.77
Permanent Ineff=
       F       F
Bank Sta=1059,1107.2
XS Rating Curve= 0 ,0
Exp/Cntr(USF)=0,0
Exp/Cntr=0.3,0.1

Type RM Length L Ch R = 1 ,121191  ,348.3,348.1,353
XS GIS Cut Line= 2
2285215.01462479461110.0179857172283993.56993717461471.483203368
#Sta/Elev= 30
       0 2510.07    19.6 2508.77    49.9 2504.94    69.7 2502.16    82.2 2499.13
   103.1 2499.58   119.8 2498.53     169 2499.31   219.9 2497.93   320.3 2498.87
   378.7 2497.91   519.9 2500.32   541.1 2502.11     575 2500.69   674.6 2502.81
   817.1 2500.97   862.3 2501.84   883.1 2500.62   912.3 2495.95   938.3 2498.26
   989.8 2496.82  1008.3 2494.62  1045.8 2495.68    1050 2497.29  1062.5 2501.42
  1066.7  2504.2    1096 2528.45  1129.3 2553.04    1199 2609.64  1273.8 2665.87
#Mann= 13 ,-1,0
       0     .05       0     390     .03       0     420     .04       0
     520     .05       0     530    .016       0     560     .05       0
     630     .04       0     700     .03       0     730      .1       0
     840     .08       0     930      .1       0   989.8    .045       0
    1050      .1       0
#XS Ineff= 2 , 0
             840 2523.47
Permanent Ineff=
       F       F
#Block Obstruct= 3 ,-1
  673.46  713.91 2522.79  743.58  788.68 2522.42   845.1  869.17 2521.53
Bank Sta=989.8,1050
XS Rating Curve= 0 ,0
Exp/Cntr(USF)=0,0
Exp/Cntr=0.3,0.1

Type RM Length L Ch R = 1 ,120843  ,328.4,342.4,383.3
BEGIN DESCRIPTION:
structure xs 4
END DESCRIPTION:
XS GIS Cut Line= 4
2285212.00688585461091.9407523432284589.46554672461244.005342638
2284390.15269195 461019.549723382283957.77119526 461101.69290824
#Sta/Elev= 30
       0 2509.51    40.6 2505.81    82.2 2500.06     111 2499.55   123.3 2498.63
   234.5 2497.24   353.9 2497.52   424.5 2499.66   514.5 2499.79   540.3 2500.36
   553.8 2501.16     580  2501.6   625.7 2501.07   826.5  2500.8     864 2499.94
   901.4  2497.1     943 2496.46   968.1 2494.29    1187 2498.55  1193.3 2494.19
  1195.5  2492.5  1219.9 2491.68  1244.3 2492.34  1248.6 2493.87  1264.7 2505.62
  1276.9  2519.5  1286.3 2527.04  1298.3 2539.57  1321.7 2561.29  1381.1 2606.65
#Mann= 11 ,-1,0
       0     .05       0     111     .04       0   123.3     .05       0
   514.5     .04       0   540.3     .05       0   553.8    .016       0
     580     .05       0   625.7     .04       0   901.4     .05       0
  1193.3    .045       0  1248.6      .1       0
#XS Ineff= 2 ,-1
       0  564.96  2504.7  862.74 1173.85 2504.94
Permanent Ineff=
       F       F
#Block Obstruct= 3 ,-1
  653.64  682.33  2521.1  694.06  713.95 2521.16  737.49  787.59 2521.01
Bank Sta=1193.3,1248.6
XS Rating Curve= 0 ,0
Exp/Cntr(USF)=0,0
Exp/Cntr=0.5,0.3

Type RM Length L Ch R = 1 ,120500  ,137.4,134.5,129.4
BEGIN DESCRIPTION:
Structure XS 3 - channel burned within banks
END DESCRIPTION:
XS GIS Cut Line= 3
2285203.08551497461076.2906271692284590.46456759 461223.99215038
2284036.66181431460611.718595342
#Sta/Elev= 30
       0 2508.71   48.25 2504.39   68.83  2501.8   81.17 2498.99  262.21 2496.92
  440.77  2499.5  530.28 2499.88  570.07 2501.51  655.54 2500.88   670.6 2500.89
  834.86 2500.32  874.51 2497.35   985.4 2494.25    1051 2494.12 1130.17 2495.44
  1146.4  2492.4 1178.71 2492.25 1189.41 2489.21 1207.12 2483.27 1223.45 2482.77
 1231.69 2483.84 1238.16 2488.05 1243.43 2491.43 1247.77 2492.76 1277.59 2498.07
 1361.07 2506.87 1381.43 2510.59  1420.7 2513.43 1444.55 2518.38 1455.75 2519.41
#Mann= 8 ,-1,0
       0     .05       0  440.77    .016       0  530.28     .05       0
  655.54    .016       0   670.6     .05       0 1189.41    .045       0
 1238.16     .05       0 1455.75     .04       0
#XS Ineff= 2 , 0
            1110  2498.6    1280          2499.6
Permanent Ineff=
       F       F
#Block Obstruct= 1 ,-1
   86.57  116.76 2519.18
Bank Sta=1189.41,1238.16
XS Rating Curve= 0 ,0
Exp/Cntr(USF)=0,0
Exp/Cntr=0.5,0.3

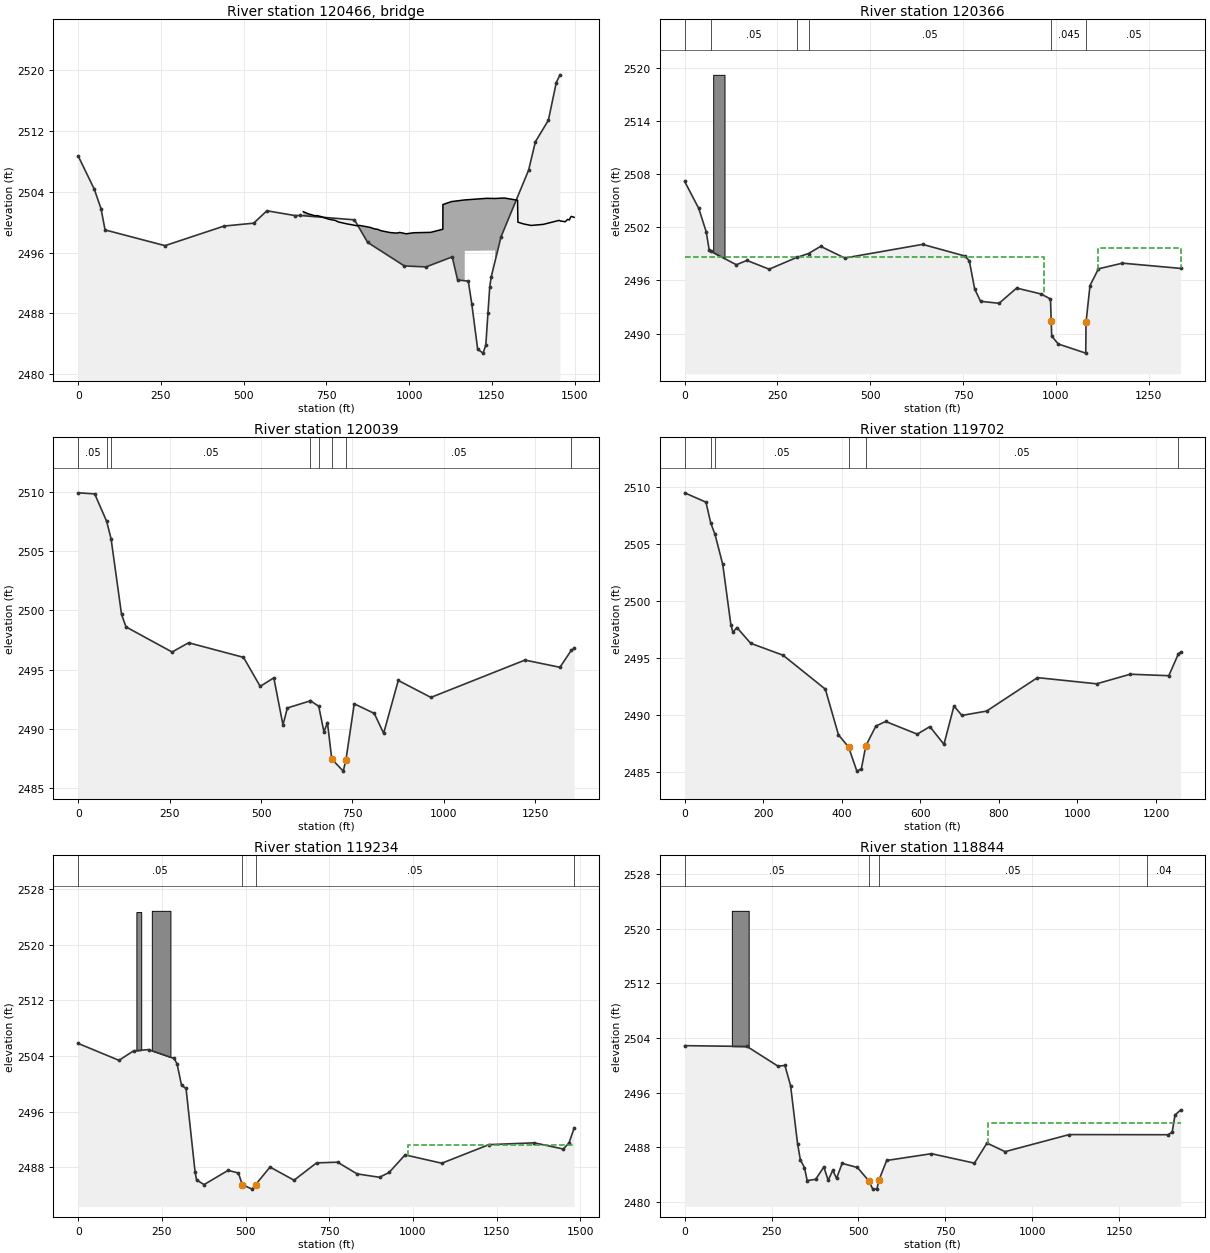
Type RM Length L Ch R = 3 ,120466  ,,,
BEGIN DESCRIPTION:
Unnamed Road
Bridge data: 54075KNA100
Width: 30' (measured on orthoimagery)
Railing height: 2.8'
Structure bounding sections incorporate channel data from survey.
Deck from Lidar with survey data incorporated
END DESCRIPTION:
Bridge Culvert--1,0,-1,-1, 0
Deck Dist Width WeirC Skew NumUp NumDn MinLoCord MaxHiCord MaxSubmerge Is_Ogee
36,30,2.6,0, 41, 35, , , 0.98, 0, 0,0,,
     680  696.34  716.19  721.24  733.44  757.85  776.15  785.97  812.76  843.79
  849.53  881.32  897.21  903.33  914.67  943.03  962.87   971.4  991.23 1014.11
 1064.95 1101.81    1102 1127.96 1168.03 1234.45 1259.38 1287.49 1327.64 1328.65
 1345.66 1368.35 1405.21 1453.41 1456.24 1471.72 1478.93 1483.92 1487.43 1490.02
 1498.61
 2501.39 2501.09 2500.85 2500.88 2500.75 2500.39 2500.25 2500.04 2499.78 2499.53
 2499.59 2499.33  2499.1 2499.09 2498.89 2498.64 2498.57 2498.66 2498.48 2498.62
 2498.67 2499.08 2502.33 2502.72 2502.94 2503.15 2503.13 2503.19  2502.9 2500.01
 2499.78 2499.58 2499.72 2500.25 2500.17 2500.07 2500.38  2500.3 2500.63 2500.77
 2500.65
                                                                                
                                                                                
                                 2496.23 2496.27 2496.29
                                                                                
        
  625.25  667.79  673.53  705.32  721.21  727.33  738.67  767.03  786.87   795.4
  815.23  838.11  888.95  925.81     926  951.96  992.03 1058.45 1083.38 1111.49
 1151.64 1152.65 1169.66 1192.35 1217.86 1243.38 1277.41 1280.24 1295.72 1302.93
 1307.92 1311.43 1314.02 1319.78  1336.2
 2499.91 2499.53 2499.59 2499.33  2499.1 2499.09 2498.89 2498.64 2498.57 2498.66
 2498.48 2498.62 2498.67 2499.08 2502.33 2502.72 2502.94 2503.15 2503.13 2503.19
  2502.9 2500.01 2499.78 2499.58 2499.65 2499.85 2500.25 2500.17 2500.07 2500.38
  2500.3 2500.63 2500.77 2500.64 2500.65
                                                                                
                                                 2496.23 2496.27 2496.29
                                                                                
                                        
BR Coef=-1 ,-1 , 0 ,, 0 ,,,0.8,0,1.2,0,
WSPro=,,,, 1 ,,,, 0 ,,,, 0 ,,,,-1 ,-1 ,-1 , 0 , 0 , 0 , 0 , 0
BR U #Sta/Elev= 30
       0 2508.71   48.25 2504.39   68.83  2501.8   81.17 2498.99  262.21 2496.92
  440.77  2499.5  530.28 2499.88  570.07 2501.51  655.54 2500.88   670.6 2500.89
  834.86 2500.32  874.51 2497.35   985.4 2494.25    1051 2494.12 1130.17 2495.44
  1146.4  2492.4 1178.71 2492.25 1189.41 2489.21 1207.12 2483.27 1223.45 2482.77
 1231.69 2483.84 1238.16 2488.05 1243.43 2491.43 1247.77 2492.76 1277.59 2498.07
 1361.07 2506.87 1381.43 2510.59  1420.7 2513.43 1444.55 2518.38 1455.75 2519.41
BR U #Mann= 8
       0     .05  440.77    .016  530.28     .05  655.54    .016   670.6     .05
 1189.41    .025 1238.16     .05 1455.75     .04
BR D #Sta/Elev= 30
       0 2507.16   37.82 2504.12    58.1 2501.47   66.21 2499.39   71.27 2499.26
  139.21 2497.76  167.59 2498.25  227.64 2497.26  301.42 2498.58  333.87 2499.03
  366.31 2499.84   431.2 2498.52  641.01 2500.06  755.63 2498.74  766.96 2498.19
  781.28 2495.03  797.13 2493.64  847.02 2493.41  894.42 2495.13  959.56 2494.47
  985.56  2493.9  987.55 2491.39  988.84 2489.72 1006.43 2488.82 1080.59 2487.79
  1081.32491.254 1092.05 2495.42 1114.77  2497.3 1179.37 2497.94 1336.17 2497.35
BR D #Mann= 6
       0     .08   71.27     .05  301.42    .016  333.87     .05  987.55    .025
  1081.3     .05
BC Design=,, 0 ,, 0 ,,,,,,
BC Use User HTab Curves=0
BC User HTab FreeFlow(D)= 0

Type RM Length L Ch R = 1 ,120366  ,323,327.3,330.2
BEGIN DESCRIPTION:
Structure XS 2- channel burned within banks
END DESCRIPTION:
XS GIS Cut Line= 3
2285185.47695004461056.4344365982284680.24954985461140.857907549
2284128.79044991 460528.68038022
#Sta/Elev= 30
       0 2507.16   37.82 2504.12    58.1 2501.47   66.21 2499.39   71.27 2499.26
  139.21 2497.76  167.59 2498.25  227.64 2497.26  301.42 2498.58  333.87 2499.03
  366.31 2499.84   431.2 2498.52  641.01 2500.06  755.63 2498.74  766.96 2498.19
  781.28 2495.03  797.13 2493.64  847.02 2493.41  894.42 2495.13  959.56 2494.47
  985.56  2493.9  987.55 2491.39  988.84 2489.72 1006.43 2488.82 1080.59 2487.79
  1081.32491.254 1092.05 2495.42 1114.77  2497.3 1179.37 2497.94 1336.17 2497.35
#Mann= 6 ,-1,0
       0     .08       0   71.27     .05       0  301.42    .016       0
  333.87     .05       0  987.55    .045       0  1081.3     .05       0
#XS Ineff= 2 , 0
             967  2498.6    1113          2499.6
Permanent Ineff=
       F       F
#Block Obstruct= 1 ,-1
   76.84   107.3 2519.19
Bank Sta=987.55,1081.3
XS Rating Curve= 0 ,0
Exp/Cntr(USF)=0,0
Exp/Cntr=0.5,0.3

Type RM Length L Ch R = 1 ,120039  ,343.6,336.2,307.8
XS GIS Cut Line= 4
2285228.54966741460883.8635040262284767.64970689460798.237031743
2284441.24556123460361.745233044 2284103.5487705460304.473701477
#Sta/Elev= 30
       0 2509.92    45.1 2509.83    77.7 2507.52    89.9 2506.04   118.4 2499.68
   130.6 2498.61   256.7 2496.49   301.9 2497.27     452 2496.04   497.7 2493.59
   534.9 2494.31     560 2490.34     572 2491.77   634.9 2492.37   634.9 2492.38
   657.8 2491.91   672.1 2489.74   681.6 2490.54  693.42 2487.46   724.8 2486.44
   732.1 2487.37   754.9 2492.12   809.7 2491.31   835.3 2489.63   875.3 2494.09
   964.6 2492.66  1221.8 2495.81  1317.4  2495.2  1348.2 2496.62  1356.3  2496.8
#Mann= 8 ,-1,0
       0     .05       0    77.7    .016       0    89.9     .05       0
   634.9     .07       0   657.8     .05       0  693.42    .045       0
   732.1     .05       0  1348.2    .016       0
Bank Sta=693.42,732.1
XS Rating Curve= 0 ,0
Exp/Cntr(USF)=0,0
Exp/Cntr=0.3,0.1

Type RM Length L Ch R = 1 ,119702  ,486.5,468.8,434.5
Node Name=AS
XS GIS Cut Line= 3
2285224.06534907460665.4093301512284515.30976554460099.738391637
2284166.69754135460028.833805947
#Sta/Elev= 30
       0 2509.47    54.2 2508.65    66.4 2506.82    77.3 2505.82    96.9  2503.2
   117.6 2497.92   122.7 2497.25   132.9 2497.67     168 2496.29   250.6 2495.24
   358.1 2492.27   391.5 2488.27   417.22487.204   438.4 2485.09   449.8 2485.29
   461.2 2487.31   486.8 2489.04   511.6 2489.44   592.1 2488.33   624.2 2488.99
   660.1 2487.44   685.6  2490.8   705.7 2489.97   768.6 2490.35   898.1 2493.28
  1048.8 2492.74  1134.5 2493.58  1232.5 2493.45    1257 2495.37  1262.6 2495.51
#Mann= 6 ,-1,0
       0     .05       0    66.4    .016       0    77.3     .05       0
   417.2    .045       0   461.2     .05       0    1257    .016       0
Bank Sta=417.2,461.2
XS Rating Curve= 0 ,0
Exp/Cntr(USF)=0,0
Exp/Cntr=0.3,0.1

Type RM Length L Ch R = 1 ,119234  ,397.8,389.4,296.4
XS GIS Cut Line= 3
2285595.77517561460237.1349647842284709.59740074459790.005753144
2284220.86781398459781.625821466
#Sta/Elev= 30
       0 2505.81   121.8 2503.39   165.3 2504.75   210.1 2504.93   286.3 2503.66
   295.3 2502.88   308.7 2499.78   322.1 2499.36     349 2487.39   353.5 2486.21
   375.9 2485.54   447.6 2487.58   478.5 2487.21   490.12485.537   519.3 2484.89
   529.92485.538     573 2488.06   644.7 2486.17   711.9 2488.66   774.6 2488.76
   832.9 2487.08   900.1 2486.59   928.8 2487.29   976.3 2489.81    1086 2488.61
  1226.9 2491.28  1362.1 2491.54  1449.1 2490.65  1466.1 2491.53  1481.4 2493.67
#Mann= 4 ,-1,0
       0     .05       0   490.1    .045       0   529.9     .05       0
 1481.39     .04       0
#XS Ineff= 2 , 0
                          984.82         2491.18
Permanent Ineff=
       F       F
#Block Obstruct= 2 ,-1
  173.77  188.25 2524.68  219.86  275.48 2524.86
Bank Sta=490.1,529.9
XS Rating Curve= 0 ,0
Exp/Cntr(USF)=0,0
Exp/Cntr=0.3,0.1

Type RM Length L Ch R = 1 ,118844  ,193.1,303.2,293.7
XS GIS Cut Line= 2
2285652.33971443 459687.650873372284228.05061256459595.172341645
#Sta/Elev= 30
       0 2502.89   179.4 2502.77   268.7 2499.88   288.5 2499.99   304.8 2497.03
   324.8 2488.55   332.9 2486.17   344.8 2485.02   352.5 2483.12     377 2483.31
   400.5 2485.11     413 2483.17   426.2 2484.63   437.1 2483.44   453.1 2485.64
   497.2 2485.04   530.92483.017   541.3 2481.87   553.3  2481.9   559.1 2483.21
   581.4 2486.07   710.1 2487.06   833.9 2485.68     870 2488.62   922.1 2487.36
  1106.5 2489.86  1391.1 2489.84  1403.1 2490.22  1411.1 2492.73  1427.3 2493.46
#Mann= 4 ,-1,0
       0     .05       0   530.9    .045       0   559.1     .05       0
    1330     .04       0
#XS Ineff= 2 , 0
                          874.37         2491.49
Permanent Ineff=
       F       F
#Block Obstruct= 1 ,-1
  135.74  184.17 2522.64
Bank Sta=530.9,559.1
XS Rating Curve= 0 ,0
Exp/Cntr(USF)=0,0
Exp/Cntr=0.3,0.1

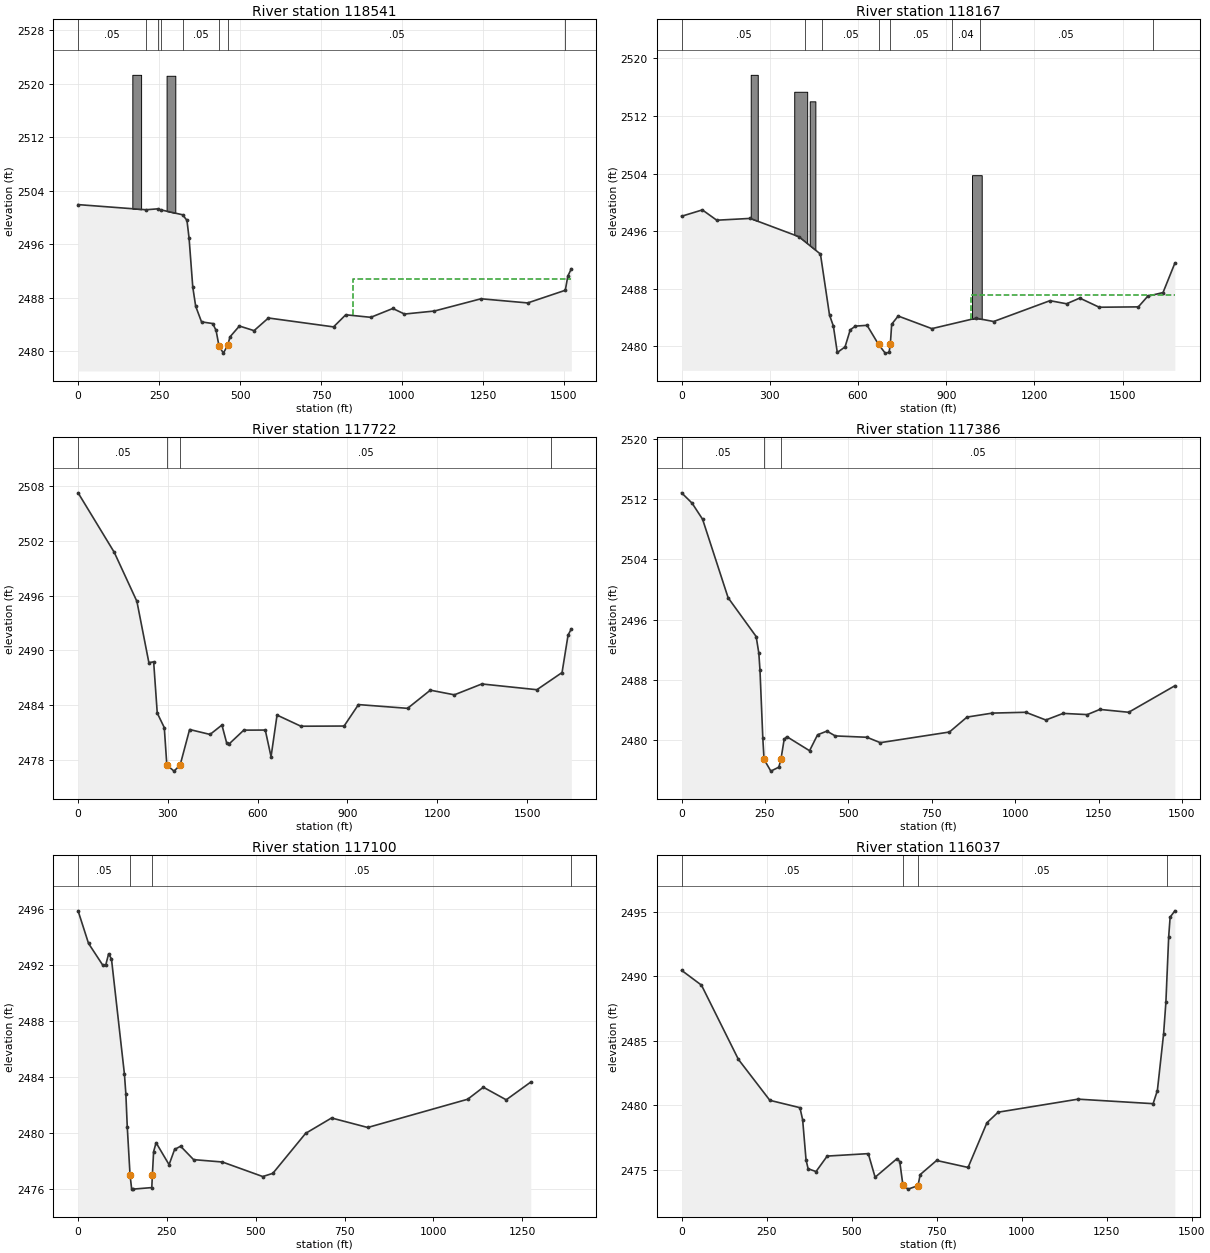
Type RM Length L Ch R = 1 ,118541  ,289.3,373.9,273.2
XS GIS Cut Line= 3
2285687.04572047459661.9304880852284942.45148754459278.951758314
2284257.48387154 459306.24143228
#Sta/Elev= 30
       0 2501.91   210.1 2501.14   246.5 2501.28   255.2 2501.13   322.6 2500.39
   336.1 2499.56   342.7 2496.89   354.1 2489.58   363.1 2486.72   381.1 2484.39
   415.6 2484.14     426 2483.12     435  2480.8   448.5 2479.72     462  2480.9
     469 2482.15     498 2483.77   543.3 2483.08   587.6 2484.97   788.7 2483.64
   826.4 2485.45   903.6 2485.07   971.7 2486.39  1007.7 2485.56    1100 2486.01
  1243.9 2487.84    1388 2487.22  1504.1 2489.11  1512.1 2491.25  1522.8 2492.32
#Mann= 8 ,-1,0
       0     .05       0   210.1     .03       0   246.5    .016       0
   255.2     .05       0   322.6     .05       0     435    .045       0
     462     .05       0  1504.1     .04       0
#XS Ineff= 2 , 0
                          847.32          2490.8
Permanent Ineff=
       F       F
#Block Obstruct= 2 ,-1
  167.49  194.62  2521.3   273.2  300.18 2521.16
Bank Sta=435,462
XS Rating Curve= 0 ,0
Exp/Cntr(USF)=0,0
Exp/Cntr=0.3,0.1

Type RM Length L Ch R = 1 ,118167  ,423.6,444.9,298.8
XS GIS Cut Line= 4
2285760.08169314459531.4250042432285415.30736128459213.586167053
2284966.22844763459006.114601776 2284251.9932745459025.014501605
#Sta/Elev= 30
       0 2498.07    70.6 2498.95   119.6 2497.52   233.5 2497.77   398.7 2495.24
   472.4 2492.82   503.2 2484.36   516.4 2482.82   529.7 2479.16     556 2479.93
   573.7  2482.3   591.3 2482.82     631 2482.93  670.15 2480.27   692.7 2479.07
   705.9 2479.18   710.3 2480.37   714.7 2483.08   736.8 2484.22   851.4 2482.47
  1001.7 2483.92  1061.7 2483.46  1253.2 2486.35  1309.8 2485.92  1354.5 2486.71
  1420.8 2485.44  1553.9 2485.49  1585.9 2486.97  1637.9 2487.48  1678.1 2491.56
#Mann= 8 ,-1,0
       0     .05       0     420     .04       0  478.93     .05       0
  670.15    .045       0   710.3     .05       0  918.93     .04       0
 1013.61     .05       0 1603.61     .03       0
#XS Ineff= 2 , 0
                          983.66         2487.15
Permanent Ineff=
       F       F
#Block Obstruct= 4 ,-1
  235.16  259.07  2517.7   383.2  427.29 2515.35  435.88  455.11 2514.02
  988.04 1021.02 2503.77
Bank Sta=670.15,710.3
XS Rating Curve= 0 ,0
Exp/Cntr(USF)=0,0
Exp/Cntr=0.3,0.1

Type RM Length L Ch R = 1 ,117722  ,336.2,336.3,365.8
Node Name=AR
XS GIS Cut Line= 2
2285900.63347264458902.6338401692284253.26507812458943.023200387
#Sta/Elev= 30
       0 2507.26   120.9 2500.74   196.5 2495.37   236.5 2488.66   252.5 2488.74
   264.5 2483.13     288 2481.54   296.5 2477.44   320.6 2476.77     341 2477.44
   372.6 2481.33   440.9 2480.79   480.6 2481.82   496.6 2479.83   504.6 2479.75
   553.6 2481.26   625.4 2481.27   644.7 2478.35   664.7 2482.91   744.4 2481.69
   888.7 2481.71   936.7 2484.06  1100.8 2483.65  1176.8 2485.64  1257.1 2485.13
  1348.9 2486.32  1532.9 2485.69  1616.9 2487.57    1637 2491.68  1647.9 2492.35
#Mann= 4 ,-1,0
       0     .05       0   296.5    .045       0     341     .05       0
    1580     .04       0
Bank Sta=296.5,341
XS Rating Curve= 0 ,0
Exp/Cntr(USF)=0,0
Exp/Cntr=0.3,0.1

Type RM Length L Ch R = 1 ,117386  ,292,286.3,275.6
XS GIS Cut Line= 3
2285855.67808878458572.7999076652284846.30018947458589.197743574
2284378.05087516 458616.52747009
#Sta/Elev= 30
       0 2512.88    31.5  2511.5    62.9 2509.36   139.5  2498.9   223.5 2493.74
   231.5 2491.53     235 2489.23   243.5 2480.16   247.2 2477.37   267.5 2475.81
   291.5 2476.34  297.81 2477.39   307.5 2480.06   315.5  2480.4   383.6 2478.53
   407.6 2480.65   435.6 2481.14   460.5  2480.5   555.6 2480.32   595.6  2479.6
   802.9 2481.02   855.6 2483.01   931.6 2483.54  1031.7 2483.65  1091.8 2482.62
  1143.7  2483.5    1216 2483.34  1253.8 2484.03  1340.2 2483.65  1478.6 2487.18
#Mann= 3 ,-1,0
       0     .05       0   247.2    .045       0  297.81     .05       0
Bank Sta=247.2,297.81
XS Rating Curve= 0 ,0
Exp/Cntr(USF)=0,0
Exp/Cntr=0.3,0.1

Type RM Length L Ch R = 1 ,117100  ,620.3,1062.9,671.6
XS GIS Cut Line= 4
2285733.33741428458269.2144794662285592.25740584458288.586939188
2284995.42693748458387.7931642182284471.33680339458435.520841286
#Sta/Elev= 30
       0  2495.9    29.4 2493.57    69.8    2492    77.9 2492.03      86 2492.83
      94 2492.45   130.4 2484.22   134.4 2482.82   138.4 2480.44   146.2    2477
   150.6 2476.03   154.7 2475.99   207.4  2476.1   209.1 2477.03   212.5 2478.67
   219.5 2479.31     256 2477.74   271.6 2478.83   288.5 2479.06     325  2478.1
   406.1 2477.93   519.6 2476.89     548 2477.12   640.2 2479.98   713.2 2481.08
     815  2480.4  1096.1 2482.42  1140.3 2483.28  1204.6 2482.38  1273.7 2483.65
#Mann= 4 ,-1,0
       0     .05       0   146.2    .045       0   209.1     .05       0
 1387.84     .04       0
Bank Sta=146.2,209.1
XS Rating Curve= 0 ,0
Exp/Cntr(USF)=0,0
Exp/Cntr=0.3,0.1

Type RM Length L Ch R = 1 ,116037  ,250.5,269.6,237.1
XS GIS Cut Line= 3
2285722.41078424457798.5313547862284731.18458012457898.192685091
2284294.82956635458024.789510074
#Sta/Elev= 30
       0 2490.45    58.5  2489.3   167.1 2483.55   259.5 2480.38     348 2479.81
     356 2478.87     366 2475.76   372.1 2475.08   395.3 2474.86   428.2 2476.06
     549 2476.25   569.1 2474.42   633.4 2475.86   641.5 2475.64     651 2473.79
   666.2  2473.5  695.14 2473.77   701.8 2474.63     750 2475.72   842.5 2475.18
   897.9 2478.64   930.9 2479.46    1166 2480.47  1386.7 2480.12  1399.2 2481.14
  1417.5 2485.53  1424.2 2487.96  1432.5 2493.07  1436.7 2494.57  1450.6 2495.06
#Mann= 4 ,-1,0
       0     .05       0     651    .045       0  695.14     .05       0
 1426.22     .04       0
Bank Sta=651,695.14
XS Rating Curve= 0 ,0
Exp/Cntr(USF)=0,0
Exp/Cntr=0.3,0.1

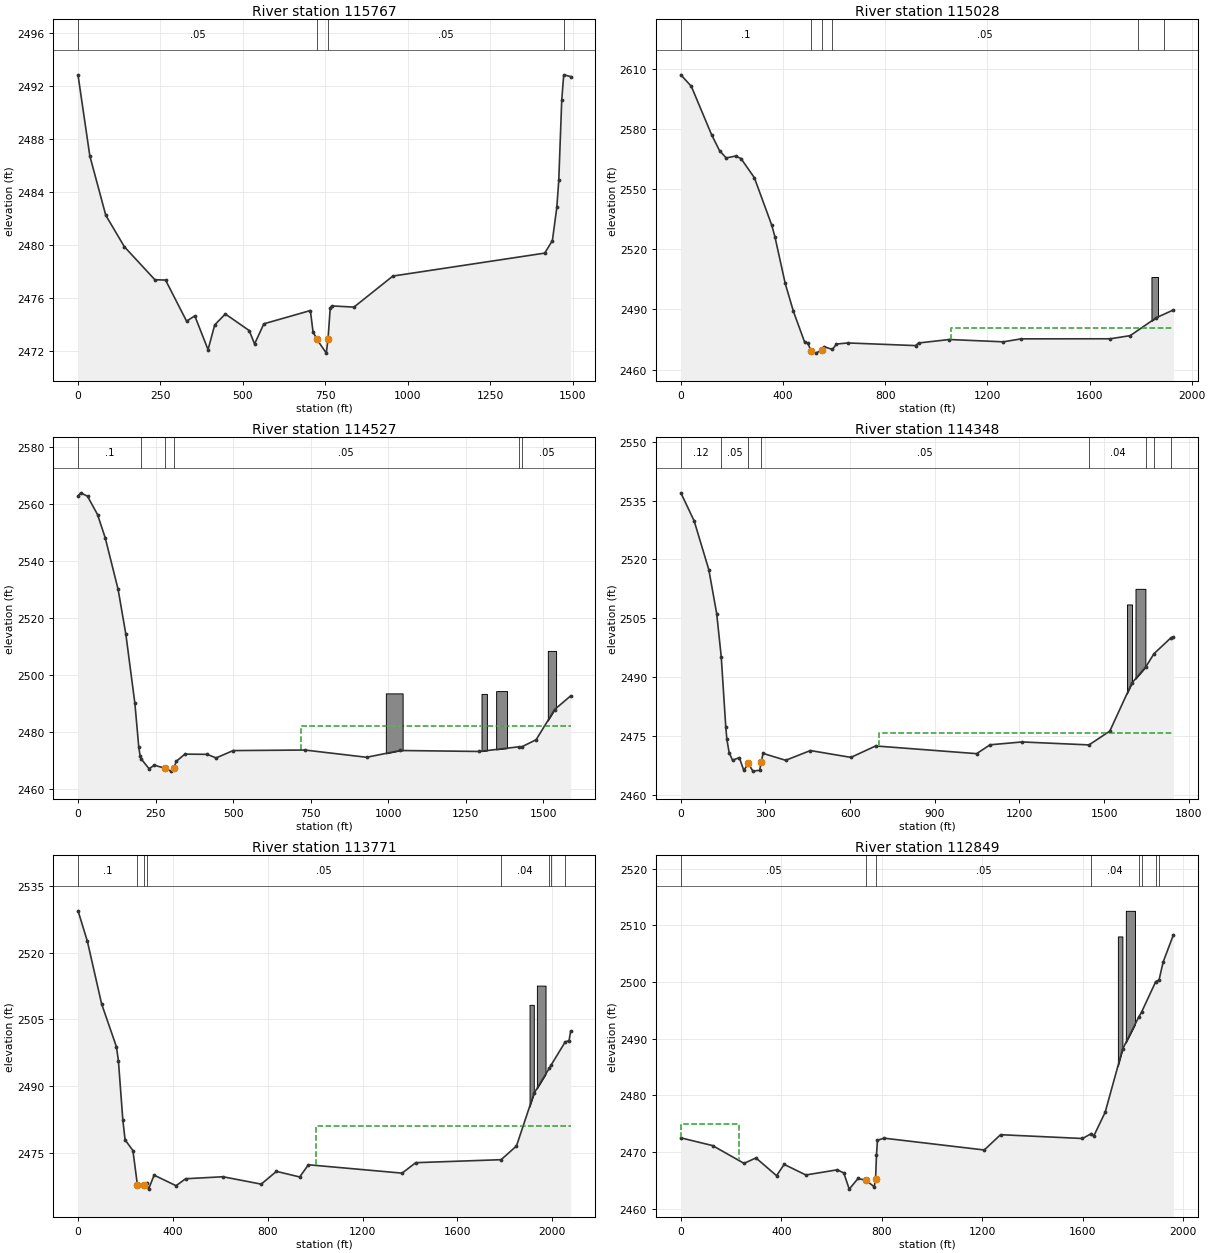
Type RM Length L Ch R = 1 ,115767  ,364.6,739.4,515.2
XS GIS Cut Line= 3
2285659.64863888457555.0274958482284751.28439031457663.095997905
2284230.32371863457915.466069656
#Sta/Elev= 30
       0 2492.79    35.7 2486.71    84.1 2482.23   140.5 2479.86   233.1 2477.37
   265.3 2477.35   329.1 2474.25     354 2474.65   394.2  2472.1   414.4 2473.97
   446.6 2474.79   519.1 2473.54   535.2 2472.53   563.4 2474.05   704.4 2475.05
   712.5 2473.45   724.5 2472.87   752.7 2471.84     7582472.927   764.6 2475.22
   768.9  2475.4   836.6 2475.31   954.6 2477.65    1415 2479.38  1438.2 2480.32
  1451.7 2482.83  1457.6 2484.86  1466.6  2490.9  1472.6 2492.82  1493.6 2492.69
#Mann= 4 ,-1,0
       0     .05       0   724.5    .045       0     758     .05       0
  1472.6    .016       0
Bank Sta=724.5,758
XS Rating Curve= 0 ,0
Exp/Cntr(USF)=0,0
Exp/Cntr=0.3,0.1

Type RM Length L Ch R = 1 ,115028  ,482.8,500.5,370.5
Node Name=AQ
XS GIS Cut Line= 4
2285815.86634731457055.2637109682285569.57676048457263.662592137
2284825.97166176457192.6175190112283982.05447201457351.502507986
#Sta/Elev= 30
       0 2607.03    40.9 2601.33   120.3 2577.19   151.6 2569.18   177.7 2565.56
     214  2566.5   235.4 2565.28   287.8 2555.72   356.2 2531.91   368.2 2526.32
   408.4 2503.08   440.6 2489.07   484.8 2473.62   496.8 2473.29   509.42469.359
     529 2468.19   553.1 2469.94   560.9 2471.41   593.3 2470.02   609.3 2472.71
   653.5 2473.27   918.7 2471.95   930.8 2473.26  1051.3 2474.98  1262.8 2473.83
    1332 2475.31  1681.4 2475.35  1759.3 2476.92  1861.1 2485.85  1928.4 2489.74
#Mann= 6 ,-1,0
       0      .1       0   509.4    .045       0   553.1      .1       0
  592.63     .05       0 1789.62     .03       0 1889.62     .04       0
#XS Ineff= 2 , 0
                         1055.96         2480.85
Permanent Ineff=
       F       F
#Block Obstruct= 1 ,-1
 1842.36 1867.85 2506.19
Bank Sta=509.4,553.1
XS Rating Curve= 0 ,0
Exp/Cntr(USF)=0,0
Exp/Cntr=0.3,0.1

Type RM Length L Ch R = 1 ,114527  ,151.8,179.5,214.1
XS GIS Cut Line= 3
2285472.55927537456731.9075806332284929.31536953456885.981646838
2283967.68068046457237.961194634
#Sta/Elev= 30
       0 2562.89     8.7 2564.01    30.5 2562.81    62.8  2556.4    87.7  2548.2
   129.3 2530.09   154.2 2514.37   183.3 2490.17   195.8 2474.84     200 2471.83
   204.1 2470.57   229.1 2467.18   245.7 2468.43   280.52467.373   300.5 2466.35
   309.1  2467.3   316.4 2469.76   344.7 2472.32   416.2 2472.24   445.3 2470.98
   500.2 2473.56     732 2473.75   930.7 2471.21  1039.5 2473.59  1294.6 2473.25
  1421.2 2474.88  1431.8 2474.92  1477.4 2477.37  1537.1 2487.97  1588.7 2492.75
#Mann= 6 ,-1,0
       0      .1       0   204.1     .05       0   280.5    .045       0
   309.1     .05       0  1421.2    .045       0  1431.8     .05       0
#XS Ineff= 2 , 0
                          718.76         2482.02
Permanent Ineff=
       F       F
#Block Obstruct= 4 ,-1
  992.67 1046.84 2493.63 1301.27 1318.63 2493.45 1348.44 1383.66 2494.43
 1515.13 1541.77 2508.54
Bank Sta=280.5,309.1
XS Rating Curve= 0 ,0
Exp/Cntr(USF)=0,0
Exp/Cntr=0.3,0.1

Type RM Length L Ch R = 1 ,114348  ,594.3,577.3,173.2
XS GIS Cut Line= 3
2285443.31047392456643.1357679872284927.87816837456629.834289134
2283860.43449042457241.702316368
#Sta/Elev= 30
       0 2536.97    47.2 2529.82    99.2  2517.4   127.2 2506.15   143.2 2495.23
   159.2 2477.44   163.2 2474.19   171.2 2470.81   183.2 2468.86   207.2 2469.53
   223.2 2466.28   239.4 2468.05   255.2 2466.09   279.2  2466.3   285.3 2468.39
   291.2 2470.61   371.6 2468.85   459.3 2471.33   602.9 2469.59   690.5  2472.5
  1048.3 2470.54  1096.2  2472.8  1209.5 2473.52  1446.6 2472.77  1520.4 2476.27
  1598.7 2488.52  1648.4 2492.68  1677.1    2496  1736.9 2500.03    1746 2500.21
#Mann= 8 ,-1,0
       0     .12       0   143.2     .05       0   239.4    .045       0
   285.3     .05       0  1446.6     .04       0  1648.4     .05       0
  1677.1     .04       0  1736.9    .016       0
#XS Ineff= 2 , 0
                          702.76         2475.75
Permanent Ineff=
       F       F
#Block Obstruct= 2 ,-1
 1581.22 1599.03 2508.54 1611.53 1646.61 2512.52
Bank Sta=239.4,285.3
XS Rating Curve= 0 ,0
Exp/Cntr(USF)=0,0
Exp/Cntr=0.3,0.1

Type RM Length L Ch R = 1 ,113771  ,593.1,921.4,166.1
XS GIS Cut Line= 4
2285288.39639915  455951.29165562284971.88187106456149.440811941
2284909.78777611456626.4010075312283850.32415169457238.555702495
#Sta/Elev= 30
       0  2529.4    39.3 2522.57    99.4 2508.51   161.9 2498.88   170.2 2495.78
     189 2482.39   198.5 2477.97   231.5 2475.57   250.4 2467.85   279.72467.852
   288.9 2468.22   297.6 2466.91   320.8 2470.05   413.5 2467.68   453.8 2469.24
   611.2 2469.69   772.7 2468.03   836.9  2470.9   934.8 2469.64   971.9 2472.38
  1367.1  2470.5  1424.5 2472.85  1784.8 2473.52  1849.5  2476.6  1923.4 2488.41
  1987.3 2494.01  1995.3 2494.74  2054.8 2499.94  2071.3 2500.28    2078 2502.33
#Mann= 8 ,-1,0
       0      .1       0   250.4    .045       0   279.7      .1       0
   288.9     .05       0  1784.8     .04       0  1987.3     .05       0
  1995.3     .04       0  2054.8    .016       0
#XS Ineff= 2 , 0
                         1004.23         2481.11
Permanent Ineff=
       F       F
#Block Obstruct= 2 ,-1
 1904.64 1922.51 2508.29 1935.64 1972.08 2512.61
Bank Sta=250.4,279.7
XS Rating Curve= 0 ,0
Exp/Cntr(USF)=0,0
Exp/Cntr=0.3,0.1

Type RM Length L Ch R = 1 ,112849  ,273.4,490.8,473.6
XS GIS Cut Line= 3
2284488.75215375455920.2233034562284796.61413729 456673.30107859
2283806.71945174457255.870678222
#Sta/Elev= 30
       0 2472.49   126.4 2471.13   251.8 2467.99   299.2 2468.95   381.3 2465.81
   411.6 2467.81     498 2465.94     623 2466.85   649.2  2466.3   670.8 2463.44
   705.8 2465.32   738.4 2464.99   770.2 2463.84   775.72465.282   779.4 2469.52
   783.2 2472.06   809.1 2472.44  1208.6 2470.35  1273.6 2473.05  1599.8 2472.38
  1635.6 2473.25  1644.9 2472.82  1690.3 2477.02  1759.7 2488.17  1824.7 2493.88
  1835.2 2494.69  1891.9  2500.1  1904.8 2500.35  1921.2 2503.54  1962.2 2508.35
#Mann= 8 ,-1,0
       0     .05       0   738.4    .045       0   775.7     .05       0
  1635.6     .04       0  1824.7     .03       0  1835.2     .04       0
  1891.9    .016       0  1904.8     .05       0
#XS Ineff= 2 , 0
           230.3    2475
Permanent Ineff=
       F       F
#Block Obstruct= 2 ,-1
  1740.9 1758.86 2508.06 1772.62  1809.1 2512.58
Bank Sta=738.4,775.7
XS Rating Curve= 0 ,0
Exp/Cntr(USF)=0,0
Exp/Cntr=0.3,0.1

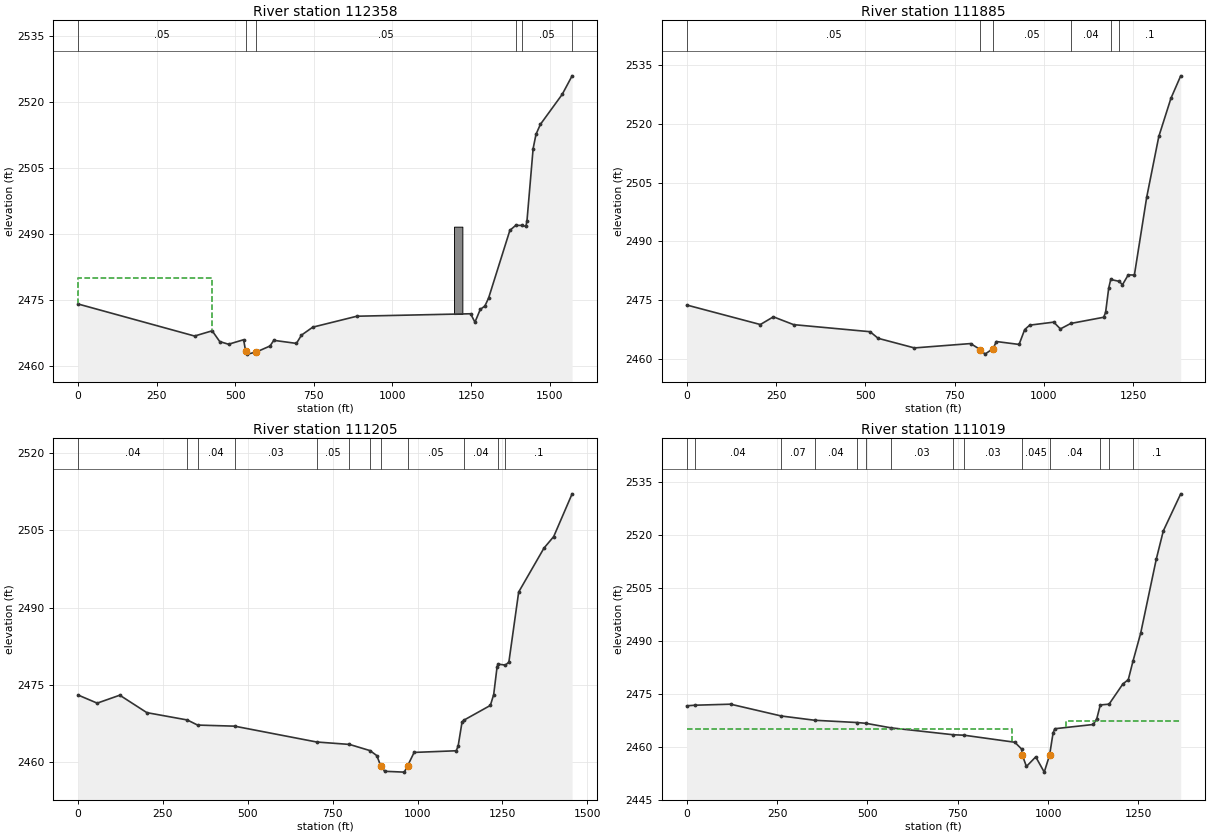
Type RM Length L Ch R = 1 ,112358  ,365.8,473.8,463.7
Node Name=AP
XS GIS Cut Line= 4
2284420.91484441455864.6623840022284353.32498537456089.046821639
2284358.74216046456628.3000503642283668.93355079457029.351567611
#Sta/Elev= 30
       0 2474.06   370.5 2466.77   426.5 2467.96   450.5 2465.51   478.5  2464.9
   526.5 2465.93     5332463.297   538.5 2462.65   566.5 2463.12   610.5  2464.5
   622.5 2465.79   694.5 2465.09   710.5 2466.97   746.5 2468.79   886.8 2471.28
  1248.5 2471.84  1262.4 2469.93  1279.4 2472.84    1294  2473.6  1305.7 2475.39
  1373.5 2490.83    1392 2491.96    1412 2491.96  1424.4 2491.73    1428 2493.06
  1447.5 2509.46  1456.7 2512.71  1470.6 2514.96    1540 2521.79  1571.5 2526.01
#Mann= 6 ,-1,0
       0     .05       0     533    .045       0   566.5     .05       0
    1392    .016       0    1412     .05       0  1571.5     .05       0
#XS Ineff= 2 , 0
           426.5    2480
Permanent Ineff=
       F       F
#Block Obstruct= 1 ,-1
 1195.86 1222.36 2491.67
Bank Sta=533,566.5
XS Rating Curve= 0 ,0
Exp/Cntr(USF)=0,0
Exp/Cntr=0.3,0.1

Type RM Length L Ch R = 1 ,111885  ,500.7,679.6,242
XS GIS Cut Line= 4
 2284316.4985724455761.0599125232284040.00445494 456150.98105043
2283850.45838128456683.0402045462283569.53917448456874.796197096
#Sta/Elev= 30
       0 2473.82   206.1 2468.85   242.6 2470.81   299.3 2468.82   513.3 2467.02
   535.9 2465.34   637.4 2462.89   794.6    2464   822.42462.441   835.1 2461.31
   857.9 2462.74   866.7 2464.52   930.4 2463.78   946.1 2467.56   960.2 2468.69
  1027.5 2469.46    1046 2467.73    1075 2469.12  1167.2  2470.7  1172.6 2471.93
  1181.4 2478.17    1187 2480.32  1210.1 2479.86  1219.9    2479    1236 2481.49
  1253.2 2481.46  1287.7 2501.29  1321.6 2516.76  1355.5 2526.47  1382.9  2532.2
#Mann= 6 ,-1,0
       0     .05       0   822.4    .045       0   857.9     .05       0
    1075     .04       0    1187    .016       0  1210.1      .1       0
Bank Sta=822.4,857.9
XS Rating Curve= 0 ,0
Exp/Cntr(USF)=0,0
Exp/Cntr=0.3,0.1

Type RM Length L Ch R = 1 ,111205  ,76.6,185.5,225.9
BEGIN DESCRIPTION:
structure xs 4
END DESCRIPTION:
XS GIS Cut Line= 5
2284062.69253907455610.4511865972283826.14331923456106.012417203
2283590.61273625456292.1106556082283692.38521038456446.223259287
2283448.13127248456789.341886345
#Sta/Elev= 30
       0 2473.06    56.2 2471.49   122.7 2473.03   202.5 2469.65   321.6 2468.23
     352 2467.24   460.8 2467.03   702.6 2463.96   799.4 2463.49   859.9 2462.29
   880.1 2461.31   891.32459.332   903.3 2458.28   960.9 2458.12   970.62459.343
   989.8 2461.94  1113.7 2462.26  1119.4 2463.15  1130.9 2467.81  1135.8 2468.17
  1214.4 2471.05  1224.2 2473.16  1234.2 2478.53    1237 2479.06  1258.6 2478.86
  1268.9 2479.44  1297.8 2493.03  1372.3 2501.54    1401 2503.78  1455.2 2512.06
#Mann= 12 ,-1,0
       0     .04       0   321.6     .07       0     352     .04       0
   460.8     .03       0   702.6     .05       0   799.4     .03       0
   859.9     .05       0   891.3    .045       0   970.6     .05       0
  1135.8     .04       0    1237    .016       0  1258.6      .1       0
Bank Sta=891.3,970.6
XS Rating Curve= 0 ,0
Exp/Cntr(USF)=0,0
Exp/Cntr=0.5,0.3

Type RM Length L Ch R = 1 ,111019  ,97.1,84.5,87.7
BEGIN DESCRIPTION:
Structure XS 3 - channel burned within banks
END DESCRIPTION:
XS GIS Cut Line= 4
2284037.97636678455596.966409783  2283795.611577456104.558524716
2283507.74086446456322.6423978462283257.67135661456689.023304705
#Sta/Elev= 30
       0 2471.58    22.5 2471.75   121.5 2472.04   261.8  2468.7   354.8 2467.49
   472.5 2466.85   496.2 2466.63   565.4 2465.35   737.4  2463.4   767.5 2463.27
     908 2461.28   926.7 2459.38  928.64 2457.69  940.15 2454.43  965.97 2457.14
   989.5 2452.83  1004.3 2457.65  1013.9 2463.89  1018.7  2465.1  1125.3  2466.3
    1135 2467.97  1144.6 2471.82  1168.9 2472.05  1207.2 2477.77  1222.1 2478.98
  1235.1 2484.21  1256.4 2492.12  1299.6 2513.06    1319 2521.03  1367.2 2531.52
#Mann= 14 ,-1,0
       0     .05       0    22.5     .04       0   261.8     .07       0
   354.8     .04       0   472.5     .03       0   496.2     .04       0
   565.4     .03       0   737.4     .05       0   767.5     .03       0
  928.64    .045       0  1004.3     .04       0  1144.6    .016       0
  1168.9      .1       0  1235.1      .1       0
#XS Ineff= 2 , 0
             900 2465.15    1050          2467.2
Permanent Ineff=
       F       F
Bank Sta=928.64,1004.3
XS Rating Curve= 0 ,0
Exp/Cntr(USF)=0,0
Exp/Cntr=0.5,0.3