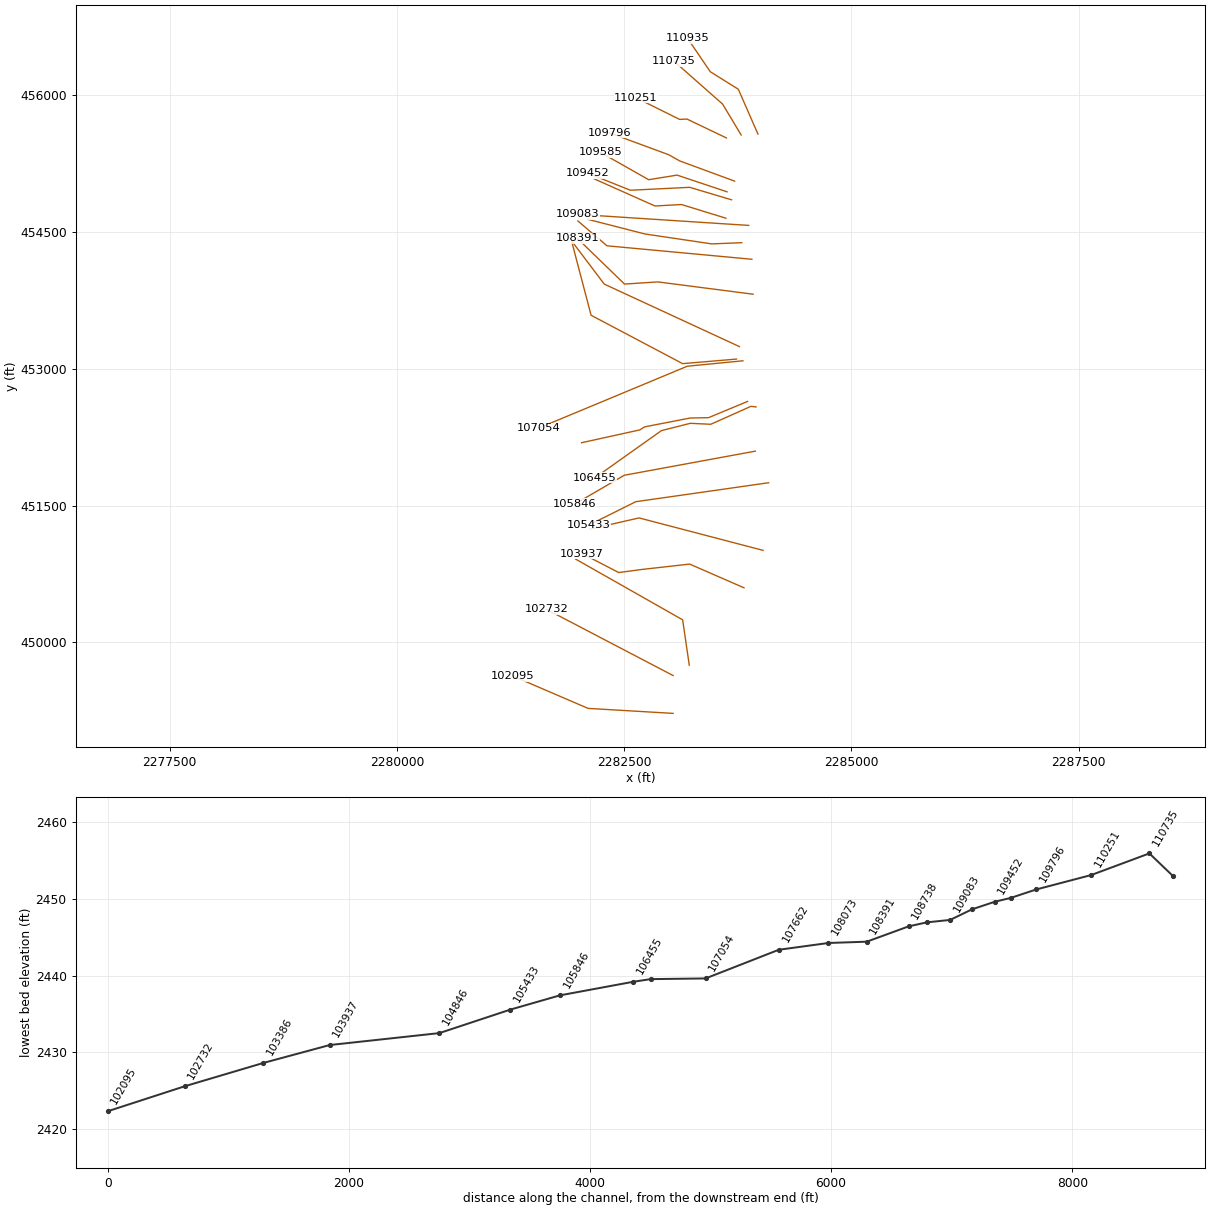
HEC-RAS study KNAPPCK.prj: KNAPPCK

--- KNAPPCK.g01 (geometry) --- (continued)

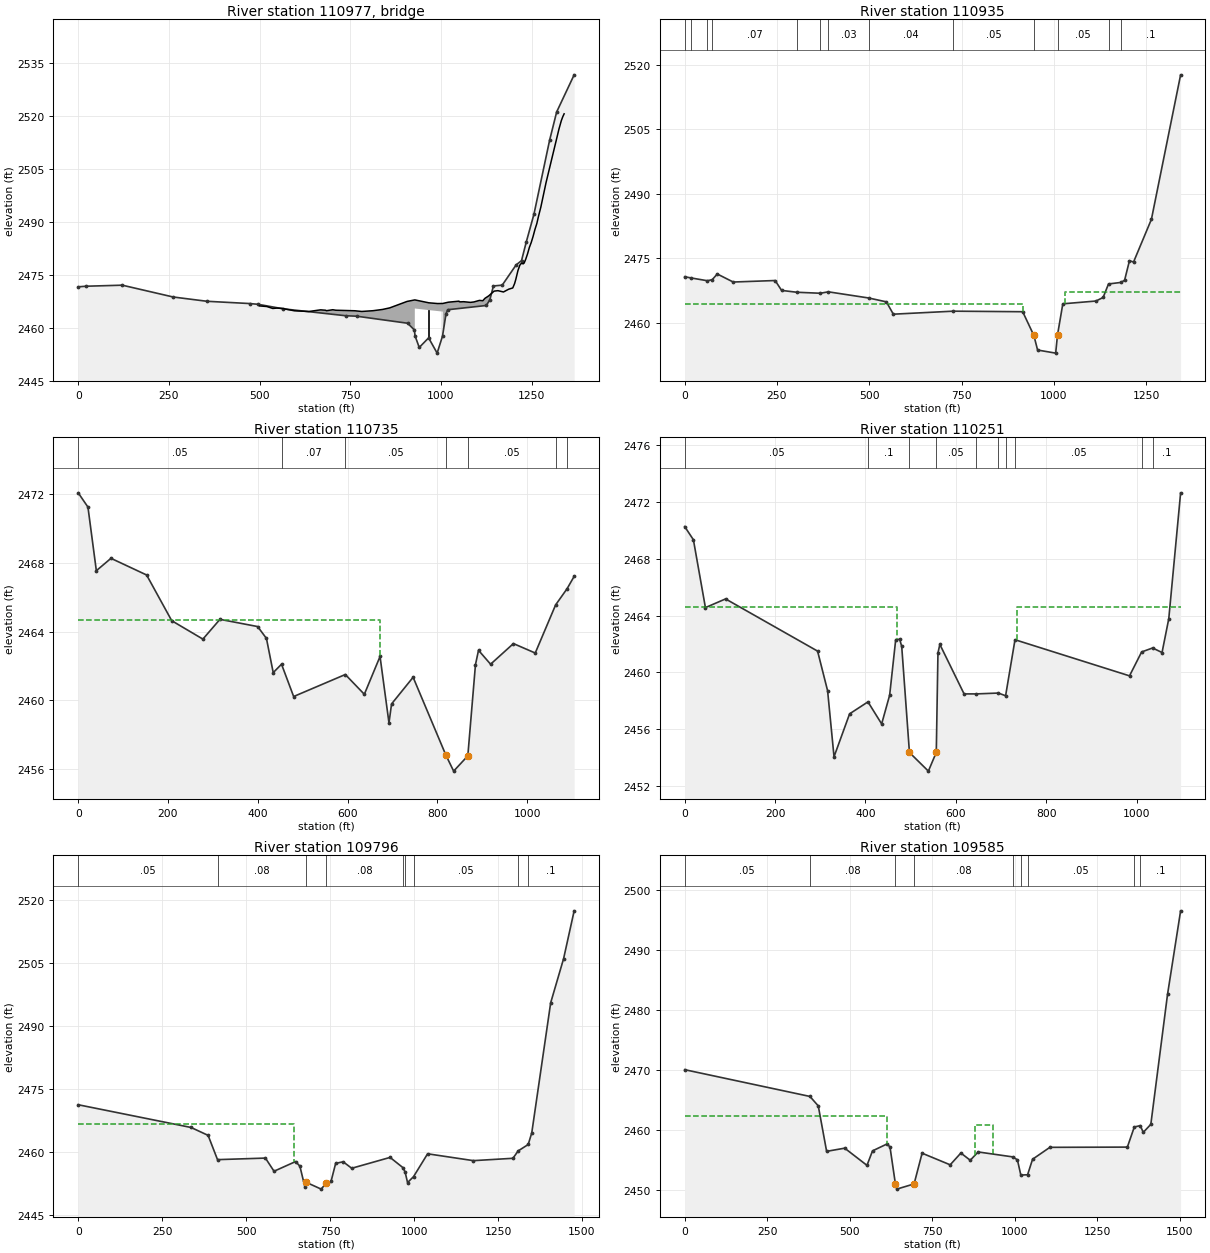
Type RM Length L Ch R = 3 ,110977  ,,,
BEGIN DESCRIPTION:
Kelly Farms Road
Bridge data: 54075KNA090
Width: 11' (measured on orthoimagery)
Rectangular Pier width: 3'
Structure bounding sections incorporate channel data from survey.
Deck from Lidar with survey data incorporated
END DESCRIPTION:
Bridge Culvert--1,0,-1,-1, 0
Deck Dist Width WeirC Skew NumUp NumDn MinLoCord MaxHiCord MaxSubmerge Is_Ogee
38,11,2.6,0, 60, 60, , , 0.98, 0, 0,0,,
  499.86  519.79  536.43  547.17  562.16  595.82  635.86  668.23  681.68  684.48
  701.85  710.22  762.38  781.71  813.17  838.91  858.93  906.59  927.96  966.51
  990.66 1004.86  1020.1  1049.7 1049.83 1052.72 1062.71  1081.2 1090.73 1106.03
 1115.37 1121.34 1131.54 1146.48 1157.06 1172.36 1186.55 1197.94 1202.97 1206.48
 1212.18 1217.36 1220.72 1223.38 1226.42 1229.26 1233.59 1238.69 1243.79 1248.89
 1253.99  1259.1  1264.2 1268.91 1275.35 1289.71 1325.42 1331.77 1335.63 1339.54
 2466.18 2466.01 2465.46 2465.56 2465.48  2464.8  2464.6 2465.07 2464.96 2464.83
  2465.1 2464.96 2464.81 2464.61 2464.83 2465.18 2465.63 2467.45 2467.88 2467.06
 2466.85 2466.87 2467.23 2467.52 2467.41 2467.33 2467.37 2467.18  2467.3 2467.74
 2467.65 2468.33 2469.01 2470.36 2470.49 2470.12  2470.9 2471.26 2472.48 2473.73
 2476.15 2477.69 2478.12 2478.22 2478.07  2478.3 2479.35 2480.89 2482.73 2484.12
 2485.83 2487.79 2489.43 2491.53 2494.11 2501.04 2516.23 2518.54 2519.62 2520.49
                                                                                
                                                                 2465.45    2465
 2464.73 2464.57
                                                                                
                                                                                
                                                                                
  250.76  270.71  284.17  315.56  329.63  345.46  356.91  372.36  393.29  423.19
  446.74  479.99  493.32  518.86  529.69  538.79  555.43  566.17  581.16  614.82
  620.96  629.12  633.42   637.7  640.86  654.86  673.78  677.74   680.5  687.23
  692.04  693.95  697.76  700.68  703.48  720.85  729.22  781.38  800.71  815.01
  832.17  857.91  877.93  925.59  946.96  985.51 1009.66 1023.86  1039.1  1068.7
 1068.83 1071.72 1081.71  1100.2 1109.73 1125.03 1134.37 1135.24 1140.34 1150.54
 2469.88 2469.31 2469.27 2468.88 2468.95 2468.77 2468.75 2468.43 2468.25 2467.72
  2467.5 2466.86 2466.72 2466.18 2466.16 2466.01 2465.46 2465.56 2465.48  2464.8
 2464.85 2464.64 2464.72 2464.65 2464.74  2464.6 2464.94 2464.93 2465.04 2465.07
 2464.98 2465.04  2464.9 2464.96 2464.83  2465.1 2464.96 2464.81 2464.61 2464.78
 2464.83 2465.18 2465.63 2467.45 2467.88 2467.06 2466.85 2466.87 2467.23 2467.52
 2467.41 2467.33 2467.37 2467.18  2467.3 2467.74 2467.65 2467.68 2468.33 2469.01
                                                                                
                                                                                
                                                                                
                                                                                
                                 2465.45    2465 2464.73 2464.57
                                                                                
Pier Skew, UpSta & Num, DnSta & Num=  ,966, 2 ,986, 2 , 0 , 0 , 0 ,,
       3       3
 2457.14    2465
       3       3
 2456.94    2465
BR Coef=-1 ,-1 , 0 ,1.25, 0 ,,,0.8,0,2,0,
WSPro=,,,, 1 ,,,, 0 ,,,, 0 ,,,,-1 ,-1 ,-1 , 0 , 0 , 0 , 0 , 0
BR U #Sta/Elev= 30
       0 2471.58    22.5 2471.75   121.5 2472.04   261.8  2468.7   354.8 2467.49
   472.5 2466.85   496.2 2466.63   565.4 2465.35   737.4  2463.4   767.5 2463.27
     908 2461.28   926.7 2459.38  928.64 2457.69  940.15 2454.43  965.97 2457.14
   989.5 2452.83  1004.3 2457.65  1013.9 2463.89  1018.7  2465.1  1125.3  2466.3
    1135 2467.97  1144.6 2471.82  1168.9 2472.05  1207.2 2477.77  1222.1 2478.98
  1235.1 2484.21  1256.4 2492.12  1299.6 2513.06    1319 2521.03  1367.2 2531.52
BR U #Mann= 14
       0     .05    22.5     .04   261.8     .07   354.8     .04   472.5     .03
   496.2     .04   565.4     .03   737.4     .05   767.5     .03  928.64     .04
  1004.3     .04  1144.6    .016  1168.9      .1  1235.1      .1
BR D #Sta/Elev= 30
       0 2470.65   17.88 2470.36   61.56 2469.72   74.67 2469.97   88.29 2471.29
  131.46 2469.42  245.05 2469.77  262.52 2467.47  303.82 2467.04  367.37 2466.81
  389.22 2467.14   498.1 2465.71  546.33 2464.81  565.18 2461.94  727.72 2462.64
  915.59 2462.51  945.84 2456.99  955.96  2453.6 1004.92 2452.88 1009.89 2457.11
 1024.28 2464.35 1114.15    2465 1133.52 2465.84 1148.05 2468.97 1181.95 2469.33
 1191.63 2469.84 1204.81 2474.39 1215.85 2474.07 1264.28 2484.01 1343.37 2517.62
BR D #Mann= 13
       0     .05   17.88     .04   61.56     .05   74.67     .07  303.82     .04
  367.37     .05  389.22     .03   498.1     .04  727.72     .05  945.84     .04
 1009.89     .05 1148.05    .016 1181.95      .1
BC Design=,, 0 ,, 0 ,,,,,,
BC Use User HTab Curves=0
BC User HTab FreeFlow(D)= 0

Type RM Length L Ch R = 1 ,110935  ,186.2,199.7,210.1
BEGIN DESCRIPTION:
Structure XS 2 - channel burned within banks
END DESCRIPTION:
XS GIS Cut Line= 4
2283972.15146041455576.8117871712283756.35647983456068.211212527
2283448.13127248456260.1250208822283198.06176462456626.505927741
#Sta/Elev= 30
       0 2470.65   17.88 2470.36   61.56 2469.72   74.67 2469.97   88.29 2471.29
  131.46 2469.42  245.05 2469.77  262.52 2467.47  303.82 2467.04  367.37 2466.81
  389.22 2467.14   498.1 2465.71  546.33 2464.81  565.18 2461.94  727.72 2462.64
  915.59 2462.51  945.84 2456.99  955.96  2453.6 1004.92 2452.88 1009.89 2457.11
 1024.28 2464.35 1114.15    2465 1133.52 2465.84 1148.05 2468.97 1181.95 2469.33
 1191.63 2469.84 1204.81 2474.39 1215.85 2474.07 1264.28 2484.01 1343.37 2517.62
#Mann= 13 ,-1,0
       0     .05       0   17.88     .04       0   61.56     .05       0
   74.67     .07       0  303.82     .04       0  367.37     .05       0
  389.22     .03       0   498.1     .04       0  727.72     .05       0
  945.84    .045       0 1009.89     .05       0 1148.05    .016       0
 1181.95      .1       0
#XS Ineff= 2 , 0
             917  2464.2    1030          2467.2
Permanent Ineff=
       F       F
Bank Sta=945.84,1009.89
XS Rating Curve= 0 ,0
Exp/Cntr(USF)=0,0
Exp/Cntr=0.5,0.3

Type RM Length L Ch R = 1 ,110735  ,432,483.7,514.4
BEGIN DESCRIPTION:
structure xs 1
END DESCRIPTION:
XS GIS Cut Line= 3
2283787.43874253455566.6106150862283583.55422922455905.253271496
2283050.57285842456373.907480922
#Sta/Elev= 30
       0 2472.07    21.7 2471.24    40.4 2467.54      73 2468.26   152.4 2467.29
   208.4 2464.63   277.8 2463.56   315.8 2464.71   399.8 2464.29   419.4  2463.6
   434.5 2461.61     453  2462.1     480 2460.22   595.1  2461.5   637.5 2460.35
   672.5 2462.55   692.4 2458.69   698.2 2459.79   746.2 2461.34   819.2 2456.81
   836.5 2455.88   868.1 2456.77   885.1 2462.07   891.9 2462.91   918.8  2462.1
   969.7  2463.3  1018.3 2462.75  1063.7 2465.55  1089.2 2466.49    1105 2467.21
#Mann= 7 ,-1,0
       0     .05       0     453     .07       0   595.1     .05       0
   819.2    .045       0   868.1     .05       0  1063.7    .016       0
  1089.2      .1       0
#XS Ineff= 2 , 0
          672.16  2464.7
Permanent Ineff=
       F       F
Bank Sta=819.2,868.1
XS Rating Curve= 0 ,0
Exp/Cntr(USF)=0,0
Exp/Cntr=0.3,0.1

Type RM Length L Ch R = 1 ,110251  ,474,455.1,418.7
XS GIS Cut Line= 4
2283625.63822122455533.9800761052283191.30874149455741.183130656
2283110.28703426 455737.198456532282630.79791443455974.950679381
#Sta/Elev= 30
       0 2470.26    19.3 2469.33    45.9 2464.56    90.5 2465.17   294.1  2461.5
   316.3 2458.71   330.5 2454.07     365 2457.09   405.6 2457.93   435.9 2456.38
   453.6  2458.4     467 2462.31   475.8 2462.33   480.3 2461.83   497.4 2454.37
   539.3 2453.06   556.8 2454.38   560.5 2461.37   564.7 2461.97   618.3 2458.49
   645.1 2458.49   694.2 2458.55   710.2 2458.36     731  2462.3   984.4 2459.76
  1011.2 2461.44  1035.5 2461.72  1056.4  2461.4  1071.3 2463.78  1097.5 2472.63
#Mann= 10 ,-1,0
       0     .05       0   405.6      .1       0   497.4    .045       0
   556.8     .05       0   645.1      .1       0   694.2    .045       0
   710.2      .1       0     731     .05       0  1011.2    .016       0
  1035.5      .1       0
#XS Ineff= 2 , 0
          470.17  2464.6  734.87          2464.6
Permanent Ineff=
       F       F
Bank Sta=497.4,556.8
XS Rating Curve= 0 ,0
Exp/Cntr(USF)=0,0
Exp/Cntr=0.3,0.1

Type RM Length L Ch R = 1 ,109796  ,185.4,211.6,238.1
XS GIS Cut Line= 4
2283715.52341843455060.1374731272283110.98042509455282.136073963
2282991.72307268455349.3040080782282338.58929535455589.599842832
#Sta/Elev= 30
       0 2471.25   335.9 2465.85   386.8 2463.97   414.8  2458.2   557.5 2458.57
   583.1 2455.44   647.2 2457.74   660.1 2456.65   674.8 2451.78   679.4 2452.79
   723.6 2451.19   739.3 2452.73   752.8 2453.01   766.6 2457.31   788.9 2457.69
   814.5 2456.15   928.7 2458.73   967.4 2456.27   973.6  2455.2   980.7 2452.75
   998.5 2454.15  1040.4 2459.59  1176.8 2457.96  1294.5 2458.52  1310.1 2460.28
    1340  2461.8  1350.6 2464.58  1406.9 2495.49  1445.3 2505.96  1476.8 2517.35
#Mann= 9 ,-1,0
       0     .05       0   414.8     .08       0   679.4    .045       0
   739.3     .08       0   967.4     .05       0   973.6    .045       0
   998.5     .05       0  1310.1    .016       0    1340      .1       0
#XS Ineff= 2 , 0
           642.7 2466.71
Permanent Ineff=
       F       F
Bank Sta=679.4,739.3
XS Rating Curve= 0 ,0
Exp/Cntr(USF)=0,0
Exp/Cntr=0.3,0.1

Type RM Length L Ch R = 1 ,109585  ,136.5,132.4,127.6
Node Name=AO
XS GIS Cut Line= 4
2283632.27934476454942.9200807492283082.39431538455126.215090544
2282770.26150884455075.7425516152282241.62807479455374.593111065
#Sta/Elev= 30
       0 2470.04   379.6 2465.57   404.9 2463.99   430.2  2456.4     485 2456.93
   552.5 2454.06   569.3 2456.48   614.3 2457.66   622.4 2457.08   638.6 2450.99
   642.7 2450.09   695.3 2450.96   719.6 2456.09   804.7 2454.15   837.1 2456.12
   865.5 2454.91   889.4  2456.3   994.7 2455.47  1008.5 2454.97  1018.8 2452.44
  1039.3 2452.49  1054.4 2455.08  1106.8 2457.07  1341.7 2457.11  1362.7 2460.46
  1380.7  2460.7  1389.9 2459.57  1412.8 2460.91  1463.4  2482.6  1503.1 2496.57
#Mann= 9 ,-1,0
       0     .05       0   379.6     .08       0   638.6    .045       0
   695.3     .08       0   994.7     .05       0  1018.8    .045       0
  1039.3     .05       0  1362.7    .016       0  1380.7      .1       0
#XS Ineff= 2 ,-1
       0  612.96 2462.37  878.49  933.56 2460.73
Permanent Ineff=
       F       F
Bank Sta=638.6,695.3
XS Rating Curve= 0 ,0
Exp/Cntr(USF)=0,0
Exp/Cntr=0.3,0.1

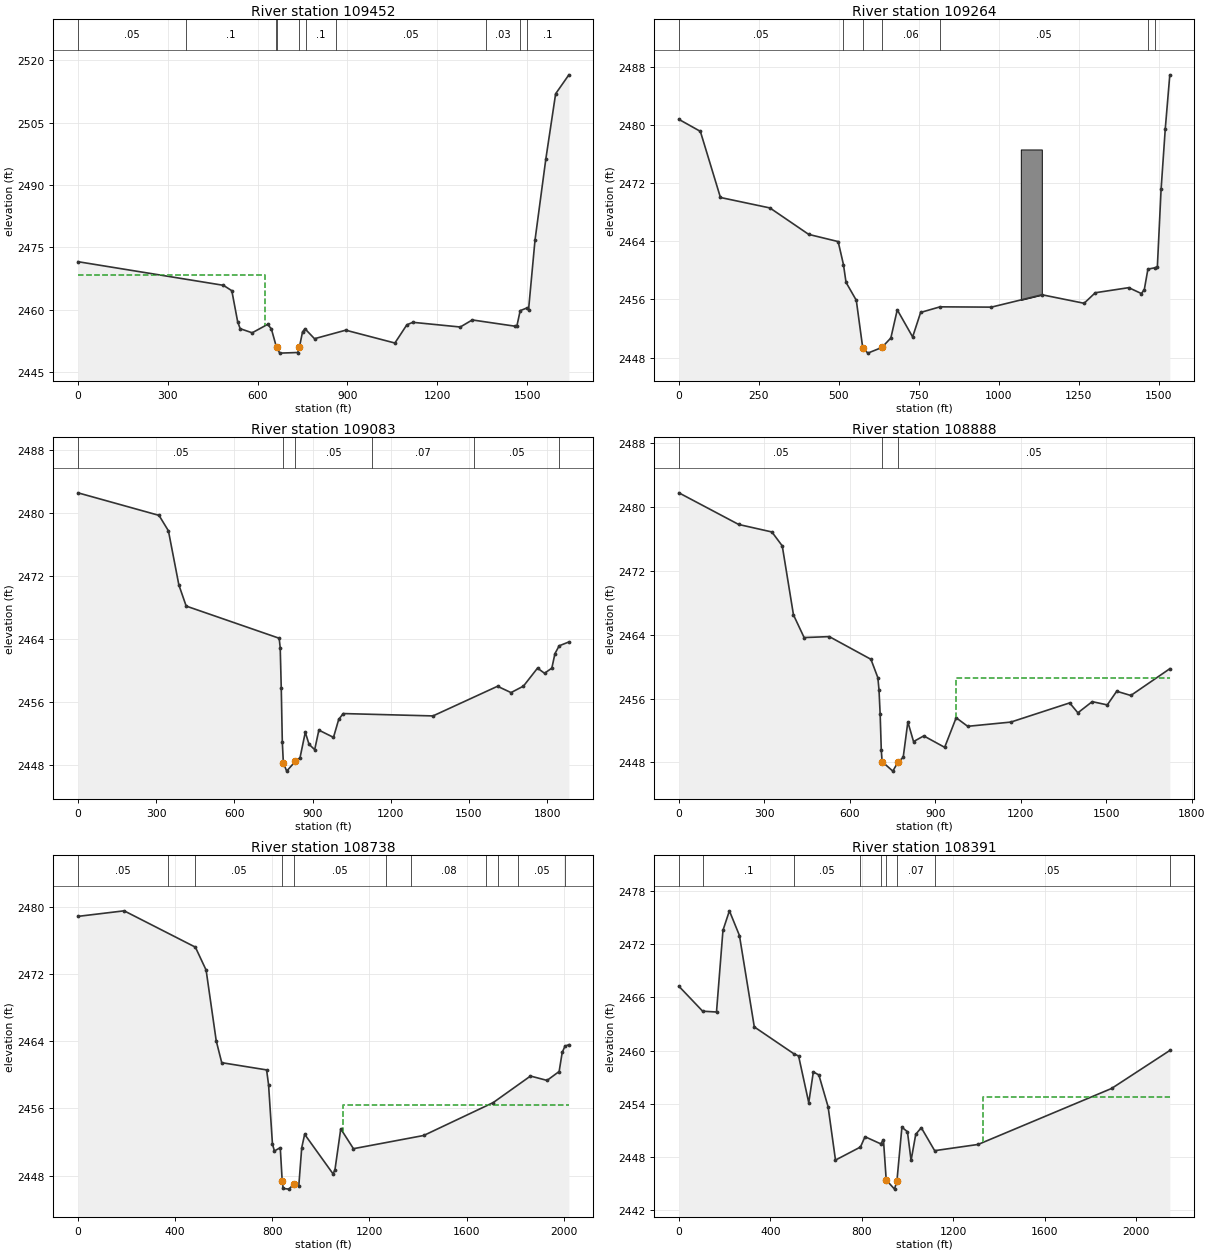
Type RM Length L Ch R = 1 ,109452  ,185.4,188.2,185.4
XS GIS Cut Line= 4
2283681.99122868454855.3640961812283221.27471148454992.210586437
2282568.97310793 454960.279738712282099.13349138455147.303275394
#Sta/Elev= 30
       0 2471.58   485.7  2465.9   513.8  2464.6   533.3 2457.15   541.7 2455.47
   581.8 2454.48   633.5 2456.51   645.9 2455.41   663.12450.974   673.9 2449.59
     734 2449.74   739.7  2451.1     750  2454.7     758 2455.45     790 2453.06
   894.2 2455.11  1058.4 2452.02  1098.4 2456.41  1118.5    2457  1276.7 2455.87
  1316.7 2457.57  1458.3 2456.08  1466.1 2456.22  1476.8  2459.8  1498.3 2460.43
  1504.8 2460.05  1526.3 2476.76  1562.6 2496.35  1595.2 2511.97  1639.4 2516.52
#Mann= 10 ,-1,0
       0     .05       0     360      .1       0  660.61     .05       0
   663.1    .045       0   739.7     .05       0  760.61      .1       0
  860.61     .05       0 1363.69     .03       0  1476.8    .016       0
  1498.3      .1       0
#XS Ineff= 2 , 0
          623.66 2468.34
Permanent Ineff=
       F       F
Bank Sta=663.1,739.7
XS Rating Curve= 0 ,0
Exp/Cntr(USF)=0,0
Exp/Cntr=0.3,0.1

Type RM Length L Ch R = 1 ,109264  ,178.1,181.4,168
XS GIS Cut Line= 4
2283620.32532238 454653.36709426 2283131.5386296454803.456486339
2282839.32919369454787.5177898352282171.23216523455085.040124576
#Sta/Elev= 30
       0 2480.78    67.1 2479.13   129.9 2470.03   284.7 2468.59     406 2464.95
   498.1 2463.96   514.7 2460.78   522.7 2458.35   554.8 2455.88   574.8 2449.38
   590.8 2448.61   634.9 2449.39   662.9  2450.7   682.9 2454.57     731 2450.84
     756 2454.21   816.7 2454.98   977.3 2454.94  1135.8 2456.64  1267.2 2455.47
  1302.2 2456.92  1406.9 2457.62  1446.3 2456.81  1455.5 2457.35  1466.8 2460.17
  1489.3 2460.36  1496.3 2460.44    1508 2471.13  1521.1 2479.49  1535.3 2486.91
#Mann= 7 ,-1,0
       0     .05       0   514.7     .08       0   574.8    .045       0
   634.9     .06       0   816.7     .05       0  1466.8    .016       0
  1489.3      .1       0
#Block Obstruct= 1 ,-1
 1069.25 1134.98 2476.64
Bank Sta=574.8,634.9
XS Rating Curve= 0 ,0
Exp/Cntr(USF)=0,0
Exp/Cntr=0.3,0.1

Type RM Length L Ch R = 1 ,109083  ,197.6,195.1,191.5
XS GIS Cut Line= 2
2283870.52634191454574.4510701822281990.94128222454695.686167277
#Sta/Elev= 30
       0 2482.52     311 2479.66   347.1  2477.7   387.2 2470.83   415.2 2468.16
     772 2464.08     776 2462.86     780 2457.76     784 2450.98     788 2448.28
   800.8 2447.23     8342448.466     852 2448.93   872.2 2452.16   886.5 2450.64
   908.2 2449.95   924.3 2452.43   980.4 2451.51  1000.4 2453.79  1017.7 2454.53
  1362.1 2454.23  1609.7 2457.99  1661.6 2457.19  1709.2 2458.01  1763.2 2460.29
  1790.1 2459.64  1818.1 2460.29  1830.1 2462.13  1846.2 2463.12  1883.5 2463.61
#Mann= 6 ,-1,0
       0     .05       0     788    .045       0     834     .05       0
    1130     .07       0    1520     .05       0  1846.2    .016       0
Bank Sta=788,834
XS Rating Curve= 0 ,0
Exp/Cntr(USF)=0,0
Exp/Cntr=0.3,0.1

Type RM Length L Ch R = 1 ,108888  ,148.7,149.4,152.7
XS GIS Cut Line= 4
2283794.32275922454385.0657031092283463.59480676454371.783456023
2282727.75831816454480.6978821332282099.50803096454641.413071882
#Sta/Elev= 30
       0 2481.75   209.8 2477.79   326.4 2476.85   362.8 2475.11   402.2 2466.47
   439.6 2463.63     528 2463.75   674.1 2460.91   698.4 2458.61   702.4 2457.11
   706.5 2454.02   710.5 2449.51  713.37  2448.1   750.9 2446.91     770 2448.09
   787.3 2448.62   803.7 2453.07   823.7 2450.61   859.6 2451.32   932.9 2449.89
   973.3 2453.59  1013.8 2452.52  1165.3 2453.05  1371.7 2455.45  1400.6 2454.21
  1450.9 2455.61  1503.8  2455.2  1536.8 2456.91  1586.4 2456.38  1723.3 2459.73
#Mann= 3 ,-1,0
       0     .05       0  713.37    .045       0     770     .05       0
#XS Ineff= 2 , 0
                          972.81         2458.56
Permanent Ineff=
       F       F
Bank Sta=713.37,770
XS Rating Curve= 0 ,0
Exp/Cntr(USF)=0,0
Exp/Cntr=0.3,0.1

Type RM Length L Ch R = 1 ,108738  ,350.5,347.7,346.3
XS GIS Cut Line= 3
2283905.50716276454203.0624926262282311.55003923454350.788150838
2281991.44496902454623.132040424
#Sta/Elev= 30
       0 2478.83   190.1 2479.49   483.4 2475.17   527.6 2472.44   569.3 2464.02
   591.9 2461.43   776.6 2460.57   784.7 2458.81   800.7 2451.76   808.8 2450.93
   832.9 2451.32   840.9 2447.33   844.9 2446.47     869 2446.39888.09962446.995
   909.2  2446.8   921.3 2451.32   933.3 2452.91  1049.8 2448.22  1057.8 2448.64
  1081.9 2453.56  1134.2  2451.2  1423.4 2452.77  1709.4 2456.68  1863.1 2459.84
  1931.2 2459.32    1981 2460.38  1993.6 2462.64    2005 2463.39  2021.1 2463.57
#Mann= 11 ,-1,0
       0     .05       0     370      .1       0     480     .05       0
   840.9    .045       0888.0996     .05       0    1270     .07       0
    1370     .08       0 1680.79     .05       0 1730.79     .08       0
 1810.79     .05       0    2005    .016       0
#XS Ineff= 2 , 0
                         1092.94         2456.35
Permanent Ineff=
       F       F
Bank Sta=840.9,888.0996
XS Rating Curve= 0 ,0
Exp/Cntr(USF)=0,0
Exp/Cntr=0.3,0.1

Type RM Length L Ch R = 1 ,108391  ,344.2,317.6,299.9
XS GIS Cut Line= 4
2283919.19181179453819.892319909 2282871.2065867453954.720897502
2282504.58679823453931.0374943392281984.89757149454432.621549501
#Sta/Elev= 30
       0 2467.24   103.9 2464.43   164.4 2464.34   192.6 2473.53   220.8 2475.73
   264.7 2472.95   329.7 2462.66   503.1 2459.63   523.3 2459.39   567.7 2454.13
   587.8  2457.6     612 2457.25   652.3 2453.67   684.6 2447.67   793.8 2449.14
   813.7  2450.3   882.2  2449.5   894.3 2449.96   906.4 2445.43   942.7  2444.4
  953.34 2445.35     975 2451.37   999.2 2450.86  1015.1 2447.63  1035.5 2450.57
  1059.7 2451.32  1118.2 2448.73  1308.2 2449.43  1891.6 2455.73  2146.3 2460.01
#Mann= 9 ,-1,0
       0     .05       0   103.9      .1       0   503.1     .05       0
   793.8     .07       0   882.2     .05       0   906.4    .045       0
  953.34     .07       0  1118.2     .05       0  2146.3     .05       0
#XS Ineff= 2 , 0
                          1329.6         2454.73
Permanent Ineff=
       F       F
Bank Sta=906.4,953.34
XS Rating Curve= 0 ,0
Exp/Cntr(USF)=0,0
Exp/Cntr=0.3,0.1

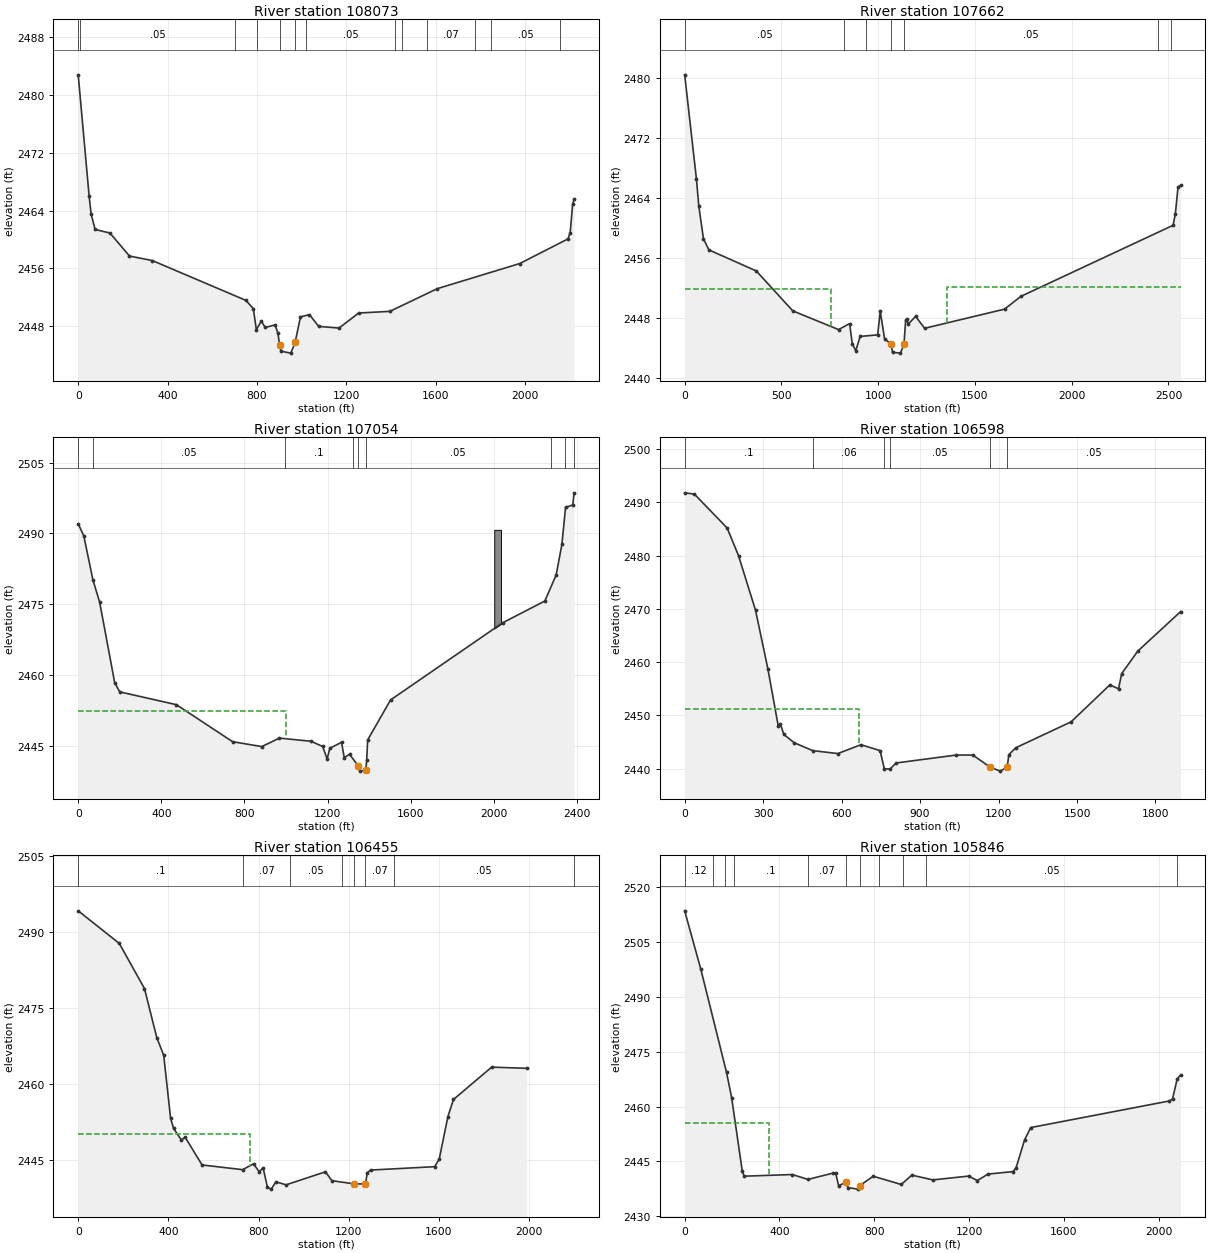
Type RM Length L Ch R = 1 ,108073  ,424.5,411.5,405.2
XS GIS Cut Line= 3
2283768.66067251453245.1370608322282281.60319862453930.465137429
2281929.36498828454395.367119217
#Sta/Elev= 30
       0 2482.81      49 2465.96    57.8 2463.52    75.4 2461.37   142.1 2460.88
   229.5 2457.69     332 2457.06   751.1 2451.54   784.3 2450.38   797.7 2447.47
   819.7 2448.67   837.4 2447.79   881.4 2448.14   894.6 2446.96901.69982445.316
   907.8  2444.5   951.9 2444.23971.09972445.707   995.3 2449.26  1035.6 2449.56
  1076.7 2447.94  1167.7  2447.7  1255.8 2449.79  1395.4 2450.02  1608.1 2453.17
  1977.2 2456.65  2192.8 2460.06  2202.9 2460.93  2214.2 2464.94  2220.7 2465.53
#Mann= 13 ,-1,0
       0     .04       0      10     .05       0     700      .1       0
     800     .05       0901.6998    .045       0971.0997      .1       0
    1020     .05       0    1420     .07       0    1450     .05       0
    1560     .07       0 1777.38     .08       0 1847.38     .05       0
 2157.38     .04       0
Bank Sta=901.6998,971.0997
XS Rating Curve= 0 ,0
Exp/Cntr(USF)=0,0
Exp/Cntr=0.3,0.1

Type RM Length L Ch R = 1 ,107662  ,442.2,607.9,641.6
Node Name=AN
XS GIS Cut Line= 4
2283736.72982478453108.290570576  2283143.728367453058.113524149
2282136.75525348453588.9693789622281925.24080854454390.743692201
#Sta/Elev= 30
       0 2480.36    60.8  2466.5    72.8 2462.95    96.9 2458.57     125 2457.08
     370 2454.28   558.5 2448.97   795.4 2446.48   852.4 2447.28   865.9 2444.62
     884 2443.66   906.6 2445.57   997.1 2445.78  1010.6  2448.9  1033.2 2445.23
1066.5992444.574  1073.9 2443.47  1115.2 2443.35  1133.22444.545  1141.8  2447.7
  1146.3 2447.86  1155.3 2447.22  1193.5 2448.24  1239.6 2446.65  1652.7  2449.2
  1737.4  2450.9  2523.8 2460.35  2535.5 2461.88  2549.2 2465.41  2562.7 2465.68
#Mann= 7 ,-1,0
       0     .05       0  825.12      .1       0  935.12     .05       0
1066.599    .045       0  1133.2     .05       0 2443.45     .03       0
 2513.45     .04       0
#XS Ineff= 2 , 0
          758.48 2451.86  1353.8          2452.1
Permanent Ineff=
       F       F
Bank Sta=1066.599,1133.2
XS Rating Curve= 0 ,0
Exp/Cntr(USF)=0,0
Exp/Cntr=0.3,0.1

Type RM Length L Ch R = 1 ,107054  ,520.2,455.4,444.9
XS GIS Cut Line= 3
 2283806.8619056453089.3381751222283195.61424913453030.038029345
2281558.01791573452350.367127739
#Sta/Elev= 30
       0 2492.03    26.8 2489.49      71  2480.1   103.2 2475.43   175.5 2458.38
   199.6 2456.42   472.9  2453.7   742.9 2445.86   883.7 2444.82   968.6 2446.62
  1120.2 2445.95  1176.5 2444.85  1198.2 2442.19  1211.2 2444.47  1267.5 2445.72
  1280.5 2442.48    1306 2443.18    13472440.792  1358.4 2439.62  1384.22439.867
  1388.7 2441.97  1393.1 2446.21  1503.3  2454.7  2042.7 2471.05  2246.2 2475.67
  2300.7 2481.21  2328.3 2487.69  2345.8 2495.51  2380.5 2496.03  2387.2  2498.6
#Mann= 9 ,-1,0
       0      .1       0      70     .05       0  994.12      .1       0
 1324.12     .05       0    1347    .045       0  1384.2     .05       0
 2274.12     .04       0 2344.12     .05       0 2384.12     .04       0
#XS Ineff= 2 , 0
          998.28 2452.37
Permanent Ineff=
       F       F
#Block Obstruct= 1 ,-1
  2002.7 2035.05 2490.76
Bank Sta=1347,1384.2
XS Rating Curve= 0 ,0
Exp/Cntr(USF)=0,0
Exp/Cntr=0.3,0.1

Type RM Length L Ch R = 1 ,106598  ,91.1,142.9,155
XS GIS Cut Line= 6
2283858.28410287452643.6278923992283429.26752197452465.645781438
2283227.37736626452461.6611073122282725.30842638452364.700703579
2282673.50766274452331.4950858632282031.97512846452190.703266744
#Sta/Elev= 30
       0 2491.81    37.2 2491.57   162.5 2485.19   205.8 2480.01   270.8 2469.77
   318.4 2458.67   357.4  2448.1   366.1 2448.36     379 2446.43     418 2444.88
   489.5 2443.38   585.6 2442.83   673.7 2444.49   747.1 2443.39   763.4 2439.94
   785.6 2439.95   808.2 2441.06  1038.3 2442.55  1101.5 2442.55  1166.7 2440.31
  1206.5 2439.53  1233.2  2440.3  1239.3 2442.62  1265.8 2443.92  1477.4 2448.79
  1625.6 2455.73  1658.8 2454.99  1670.6 2457.84  1732.6 2462.09  1896.1  2469.5
#Mann= 6 ,-1,0
       0      .1       0   489.5     .06       0   763.4    .045       0
   785.6     .05       0  1166.7    .045       0  1233.2     .05       0
#XS Ineff= 2 , 0
          668.17 2451.11
Permanent Ineff=
       F       F
Bank Sta=1166.7,1233.2
XS Rating Curve= 0 ,0
Exp/Cntr(USF)=0,0
Exp/Cntr=0.3,0.1

Type RM Length L Ch R = 1 ,106455  ,547.4,609.6,315.4
XS GIS Cut Line= 6
2283951.12265951452583.7123579272283895.39564379452589.852782321
 2283453.0922806 452393.038367122283228.76617295452403.619787292
2282911.08933357452323.7040264412282179.04653182 451806.04424348
#Sta/Elev= 30
       0 2494.24   182.2 2487.79   293.9 2478.87   348.5 2469.16   379.2 2465.67
   409.8 2453.18     423  2451.2     458 2448.88   474.1 2449.48   549.4 2443.97
   729.3 2443.04   777.7  2444.2   802.5 2442.62     820  2443.4   839.6 2439.53
   856.1 2439.19   876.7 2440.63   922.1 2440.04  1096.7 2442.62  1125.3 2440.86
  1222.5 2440.24  1274.2  2440.2  1282.1 2442.43  1296.8 2442.96  1580.9 2443.63
  1601.3 2445.12  1639.7 2453.51  1664.4 2456.92  1833.8 2463.32  1988.9 2463.09
#Mann= 8 ,-1,0
       0      .1       0   729.3     .07       0     940     .05       0
 1172.04     .07       0  1222.5    .045       0  1274.2     .07       0
 1402.04     .05       0 2199.81     .04       0
#XS Ineff= 2 , 0
          761.69 2450.05
Permanent Ineff=
       F       F
Bank Sta=1222.5,1274.2
XS Rating Curve= 0 ,0
Exp/Cntr(USF)=0,0
Exp/Cntr=0.3,0.1

Type RM Length L Ch R = 1 ,105846  ,351.3,412.7,331.2
XS GIS Cut Line= 3
2283943.04348714452098.2588835392282501.59378978451833.689002377
2281958.76937843451518.942074788
#Sta/Elev= 30
       0 2513.51      68 2497.56   176.6 2469.34   198.1 2462.46   242.9 2442.41
     251 2440.96   454.3 2441.41   520.3 2440.07   625.1 2441.79   637.3 2441.74
   649.8 2438.35   680.42439.299   690.2 2437.81   730.9 2437.42   738.22438.348
   795.9 2440.94   913.9 2438.69   958.6 2441.25  1047.4 2439.94  1198.6 2440.99
  1235.2 2439.75  1279.9 2441.53  1385.6 2442.21  1398.5 2443.21  1434.4 2450.88
  1460.3 2454.25  2045.1 2461.52    2059 2462.11  2078.6 2467.58    2093 2468.65
#Mann= 11 ,-1,0
       0     .12       0     120      .1       0     170     .12       0
     210      .1       0     520     .07       0   680.4    .045       0
   738.2     .07       0     820     .05       0     920     .07       0
    1020     .05       0  2078.6    .016       0
#XS Ineff= 2 , 0
          357.14 2455.61
Permanent Ineff=
       F       F
Bank Sta=680.4,738.2
XS Rating Curve= 0 ,0
Exp/Cntr(USF)=0,0
Exp/Cntr=0.3,0.1

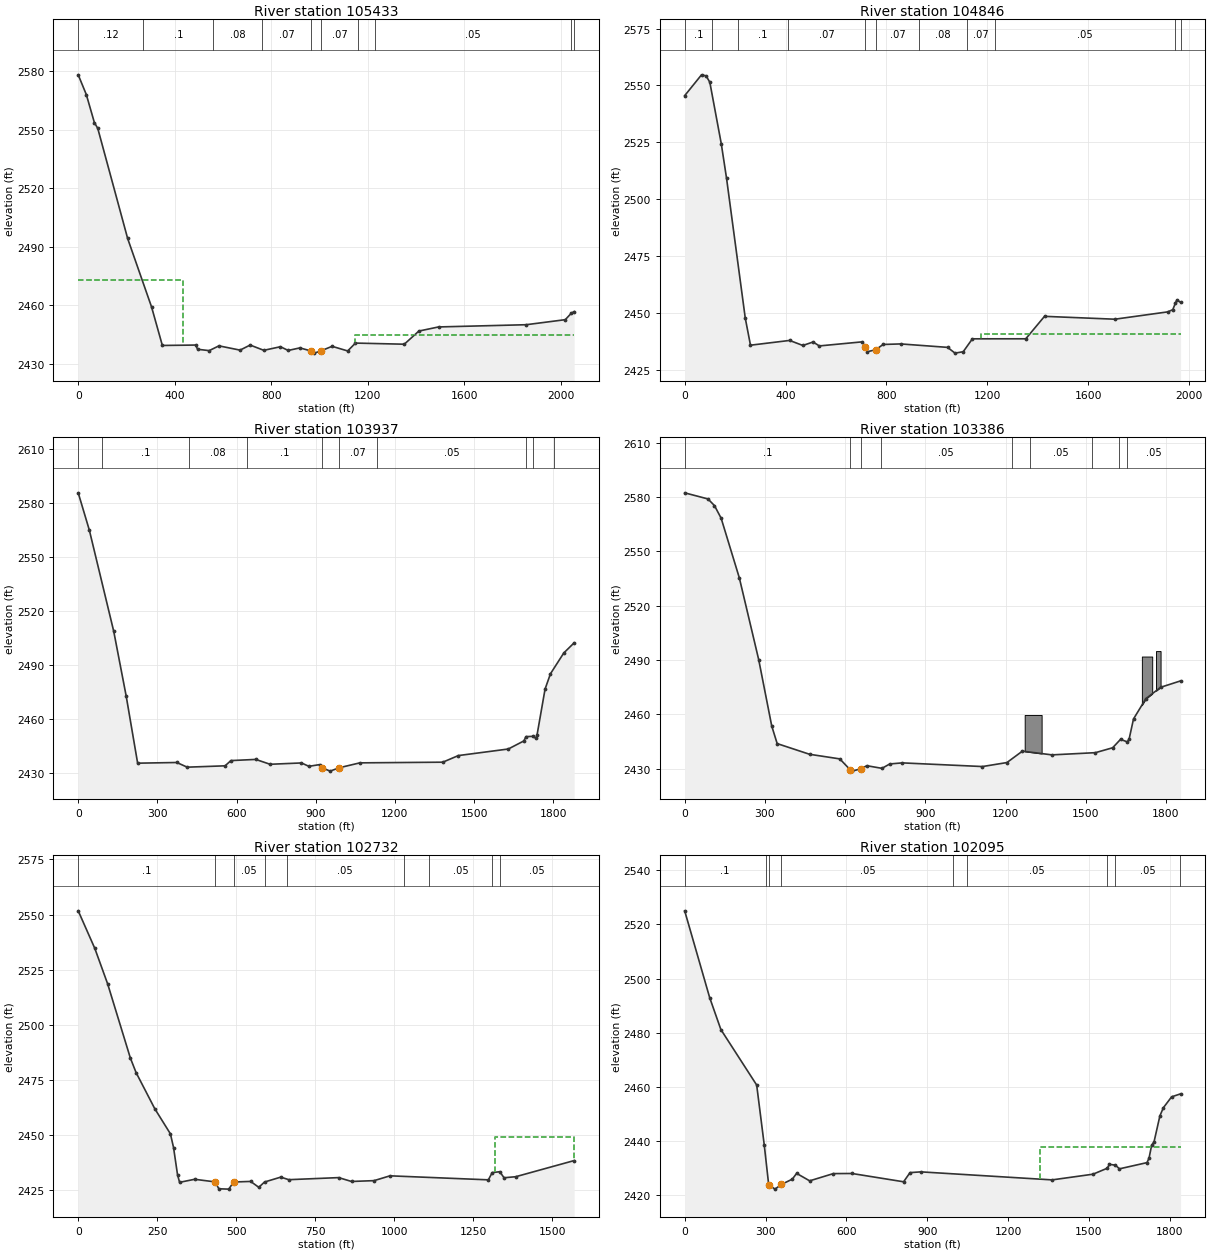
Type RM Length L Ch R = 1 ,105433  ,514.3,587.6,324.5
XS GIS Cut Line= 3
2284089.33333574451751.666874288 2282628.2732537 451543.67903198
2282110.03643125451286.111413542
#Sta/Elev= 30
       0 2578.21    33.5 2568.12    66.9 2553.77      81 2550.75   204.8 2494.32
   303.9 2459.21   348.6 2439.49     486  2439.7   494.8 2437.53   542.6 2436.84
     583 2439.29   670.4  2437.1   712.3  2439.7   768.8    2437   837.9 2438.84
   869.8 2436.93   918.3 2438.24   964.52436.676   978.3 2435.56  1007.2 2436.81
  1051.7 2439.05  1116.3 2436.68  1148.6 2440.71  1350.8 2440.13  1411.2 2446.87
  1492.6 2448.98  1855.6 2450.12  2017.8 2452.71  2043.2 2456.08  2054.5 2456.82
#Mann= 10 ,-1,0
       0     .12       0     270      .1       0     560     .08       0
     760     .07       0   964.5    .045       0  1007.2     .07       0
    1160      .1       0    1230     .05       0  2043.2    .016       0
  2054.5     .05       0
#XS Ineff= 2 , 0
           434.6 2473.07 1145.68         2444.89
Permanent Ineff=
       F       F
Bank Sta=964.5,1007.2
XS Rating Curve= 0 ,0
Exp/Cntr(USF)=0,0
Exp/Cntr=0.3,0.1

Type RM Length L Ch R = 1 ,104846  ,555.3,909,513.9
Node Name=AM
XS GIS Cut Line= 3
2284028.66900399451009.9777199812282664.76565111451365.778594647
2282121.94123976451242.616753416
#Sta/Elev= 30
       0 2545.52    66.7 2554.67      85 2554.21    99.7 2551.41   145.2 2524.35
   165.9 2509.32   240.3 2447.82   260.9 2435.99   416.1 2438.08   468.6 2435.87
     509  2437.4   533.8 2435.67   704.6 2437.47     7152435.355   723.9 2433.12
   757.4 2433.99   786.6 2436.31   856.2 2436.55  1042.2 2435.04  1071.8 2432.51
  1104.3 2433.13  1140.7 2438.79  1352.3  2438.8  1426.6 2448.66  1705.5  2447.4
  1915.4 2450.62  1935.2 2451.59  1945.4 2454.44  1951.6 2455.91  1966.2 2454.76
#Mann= 11 ,-1,0
       0      .1       0     110     .12       0     210      .1       0
     410     .07       0     715    .045       0   757.4     .07       0
     930     .08       0    1120     .07       0    1230     .05       0
  1945.4    .016       0  1966.2     .05       0
#XS Ineff= 2 , 0
                         1173.64         2440.81
Permanent Ineff=
       F       F
Bank Sta=715,757.4
XS Rating Curve= 0 ,0
Exp/Cntr(USF)=0,0
Exp/Cntr=0.3,0.1

Type RM Length L Ch R = 1 ,103937  ,548.1,550.7,360
XS GIS Cut Line= 5
2283818.83771893450599.4382492122283221.27471148450859.446580699
2282692.13494916450800.1464349212282440.93706606450766.547846468
2282038.08927241450974.692528396
#Sta/Elev= 30
       0 2585.69    42.2 2564.92   134.7 2508.62   181.8  2472.7   225.2 2435.38
   373.7 2435.76     413 2433.16   556.6 2433.91   578.7 2436.82   672.9 2437.47
   727.1 2434.77     846 2435.51   874.2 2433.63   914.4 2434.58   922.3 2432.94
   954.7 2430.96   988.42432.805  1067.3 2435.56  1381.6 2435.93  1440.6 2439.61
  1629.8 2443.26  1688.7 2447.74  1697.1 2450.14  1721.6 2450.29  1734.9 2449.26
  1739.1 2451.32  1769.2  2476.6  1789.6 2485.08  1840.1 2496.65  1879.4  2502.3
#Mann= 10 ,-1,0
       0     .12       0      90      .1       0     420     .08       0
     640      .1       0   922.3    .045       0   988.4     .07       0
 1131.68     .05       0  1697.1    .016       0  1721.6     .04       0
 1804.13     .05       0
Bank Sta=922.3,988.4
XS Rating Curve= 0 ,0
Exp/Cntr(USF)=0,0
Exp/Cntr=0.3,0.1

Type RM Length L Ch R = 1 ,103386  ,621.2,653.7,608.9
XS GIS Cut Line= 3
2283216.71316181449750.990009624  2283143.728367450248.198924221
 2281966.8485508450914.185176802
#Sta/Elev= 30
       0 2582.25    87.1 2578.87   111.4  2575.2   136.4 2568.23   204.4 2535.31
   276.8 2490.19   325.6 2453.53   345.9 2443.83   467.1 2437.93   580.2 2435.38
   618.2 2429.51   626.1 2428.63   658.8 2429.91   681.3 2431.62   737.7 2430.17
   767.1 2432.59     814 2433.18  1113.7 2431.16  1205.2 2433.36  1263.1 2439.67
  1373.6  2437.6  1536.1 2438.82  1600.5 2441.52    1630 2446.15  1655.6 2444.77
  1662.3 2446.39  1678.6 2457.43  1724.6 2468.58  1779.6 2474.88  1854.8 2478.45
#Mann= 9 ,-1,0
       0      .1       0   618.2    .045       0   658.8      .1       0
  732.54     .05       0 1222.54     .04       0 1292.54     .05       0
 1522.54     .04       0 1622.54    .016       0  1655.6     .05       0
#Block Obstruct= 3 ,-1
 1271.61 1334.94 2459.62 1709.86 1748.55 2491.89 1762.68 1779.85 2494.89
Bank Sta=618.2,658.8
XS Rating Curve= 0 ,0
Exp/Cntr(USF)=0,0
Exp/Cntr=0.3,0.1

Type RM Length L Ch R = 1 ,102732  ,587.8,636.8,701.7
XS GIS Cut Line= 2
2283038.81272447449636.9512677442281647.54007353450362.237666101
#Sta/Elev= 30
       0 2551.71    52.6 2534.65    93.2 2518.57   164.9 2485.04     183 2478.43
   242.3 2462.01   291.7 2450.65   301.6 2444.44   314.2 2432.12   320.7 2428.67
   368.4 2430.05   433.1 2428.87     445 2425.74   476.5 2425.59   491.4 2428.82
   545.6 2429.08   571.3 2426.41   589.4 2428.81   640.8 2431.03   666.3 2429.87
     824 2430.81   864.6 2429.06   936.1 2429.44   986.4 2431.62  1297.6  2429.8
  1309.8 2433.09  1333.7 2433.48  1347.2 2430.74  1383.9 2431.21    1569 2438.53
#Mann= 9 ,-1,0
       0      .1       0   433.1    .045       0   491.4     .05       0
     590     .07       0     660     .05       0    1030     .07       0
    1110     .05       0  1309.8    .016       0  1333.7     .05       0
#XS Ineff= 2 , 0
                          1319.1         2449.02
Permanent Ineff=
       F       F
Bank Sta=433.1,491.4
XS Rating Curve= 0 ,0
Exp/Cntr(USF)=0,0
Exp/Cntr=0.3,0.1

Type RM Length L Ch R = 1 ,102095  ,516.8,511.5,480.4
XS GIS Cut Line= 3
2283038.81272447  449221.85024732282103.69504105449276.588843402
2281273.49300017449632.389718068
#Sta/Elev= 30
       0 2525.03    92.7 2493.02   134.3 2481.23   267.1 2460.76   295.1 2438.75
   311.72423.961   335.2 2422.35   358.62424.064   399.3 2426.03   415.3 2428.16
   463.7 2425.41   551.6 2428.08   620.6 2428.12   812.2 2425.06   836.1 2428.44
   876.3 2428.72  1363.3 2425.76    1515 2427.86  1567.8 2430.06  1575.9  2431.5
  1598.3 2431.18  1613.1 2429.84  1715.2 2432.13  1722.8 2433.77  1732.6 2438.59
  1741.3 2439.76  1763.1 2449.38  1776.1  2452.4  1806.6  2456.4    1840 2457.51
#Mann= 9 ,-1,0
       0      .1       0     300     .05       0   311.7    .045       0
   358.6     .05       0  996.72     .07       0 1046.72     .05       0
  1567.8    .016       0  1598.3     .05       0 1836.72      .1       0
#XS Ineff= 2 , 0
                         1318.42         2437.85
Permanent Ineff=
       F       F
Bank Sta=311.7,358.6
XS Rating Curve= 0 ,0
Exp/Cntr(USF)=0,0
Exp/Cntr=0.3,0.1