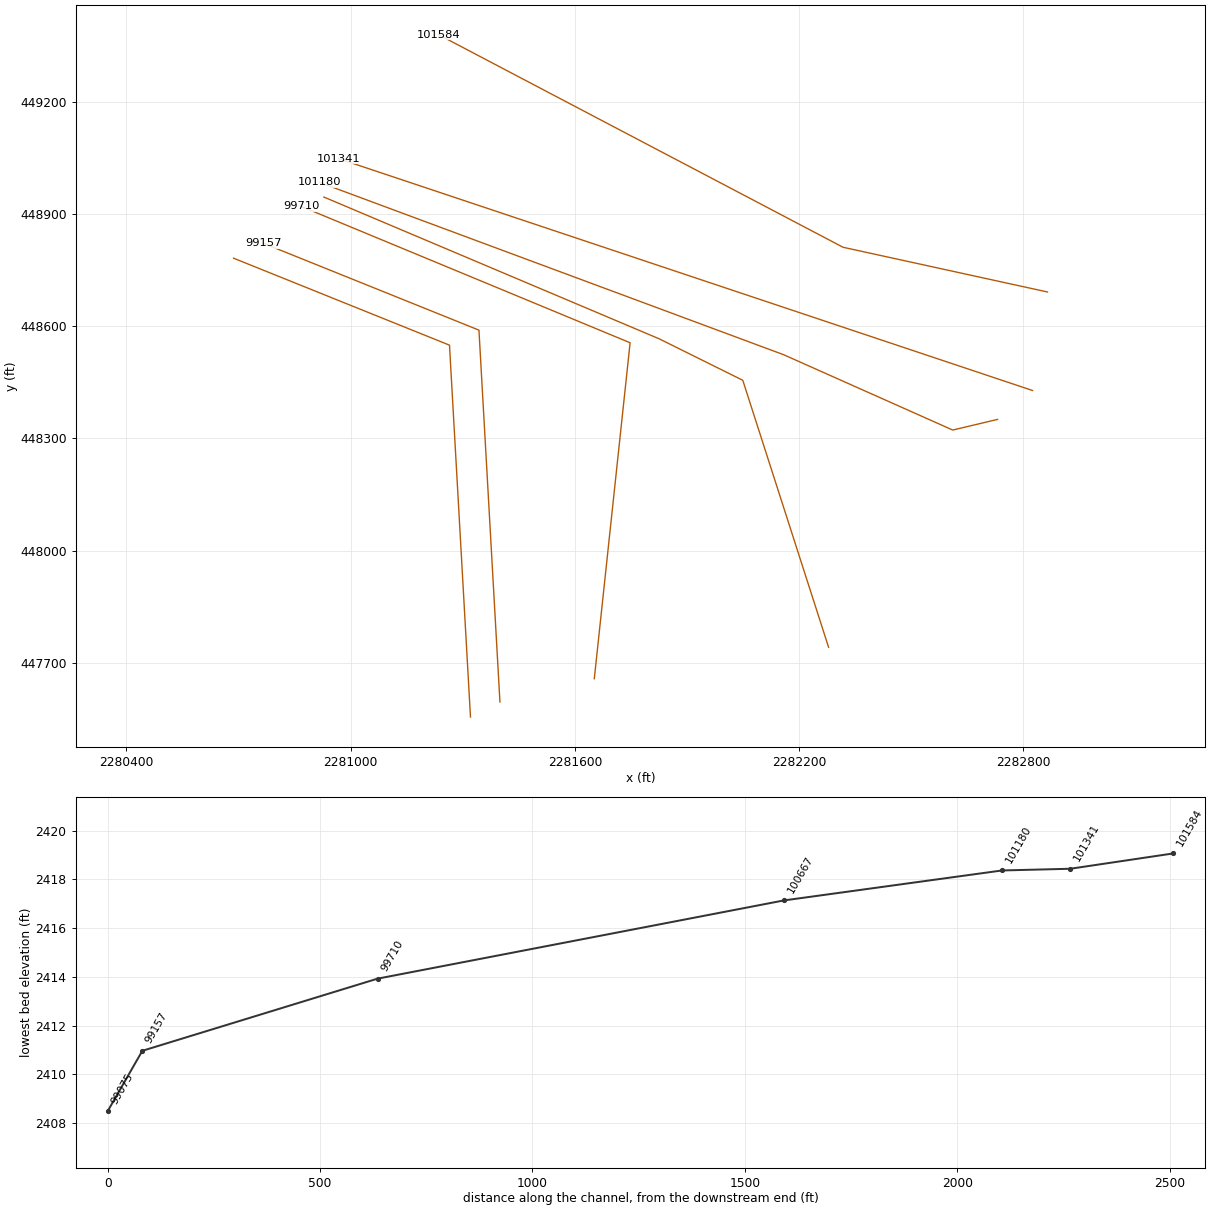
HEC-RAS study KNAPPCK.prj: KNAPPCK

--- KNAPPCK.g01 (geometry) --- (continued)

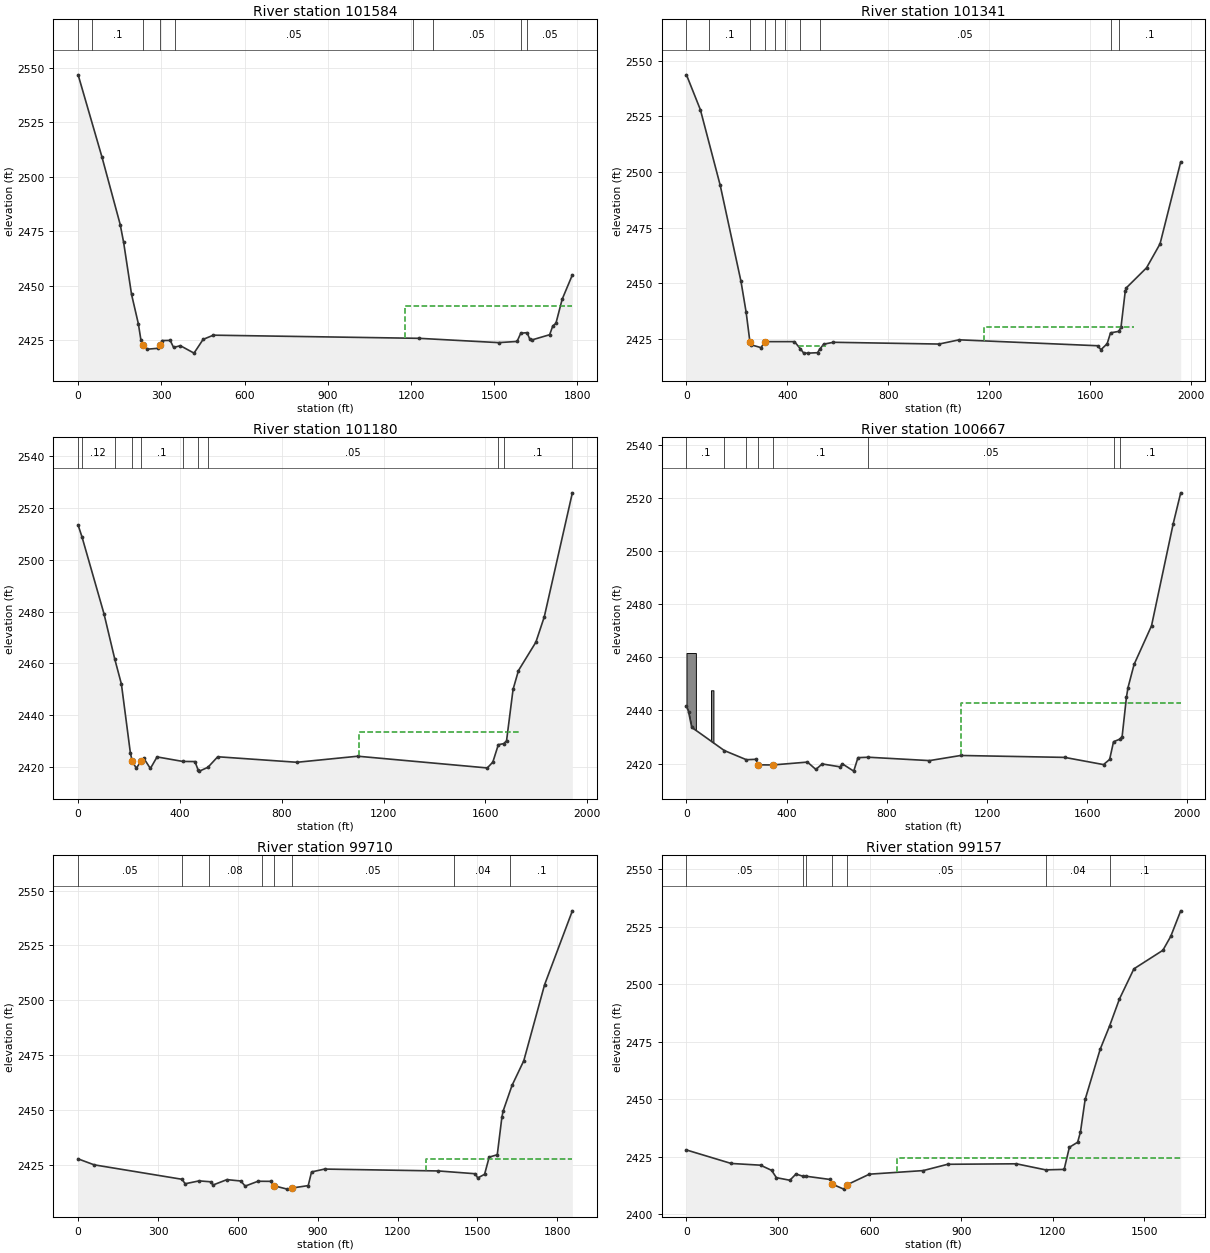
Type RM Length L Ch R = 1 ,101584  ,247.7,243,219.3
Node Name=AL
XS GIS Cut Line= 3
2282864.37354043448691.7052944542282317.55265138448811.310776531
2281235.73777095449379.834476906
#Sta/Elev= 30
       0 2546.78    86.2 2508.94   151.7 2478.08     164 2469.94   192.6 2446.02
   217.2 2432.51   226.5 2425.01   233.22422.795   249.9 2420.88   286.8 2421.28
   294.32422.801   303.2 2424.84   331.9 2424.91   344.2 2421.68   368.7 2422.48
   417.8 2419.07   450.6 2425.37   487.5 2427.31  1230.1 2425.86  1515.9 2423.89
  1582.5 2424.43  1595.9 2428.21  1618.7 2428.46  1627.7  2425.7  1636.8 2425.15
    1700 2427.52  1711.4 2431.56  1722.6 2432.72  1745.2 2443.82  1781.9 2454.96
#Mann= 9 ,-1,0
       0     .12       0      50      .1       0   233.2    .045       0
   294.3      .1       0     350     .05       0 1208.42     .07       0
 1278.42     .05       0  1595.9    .016       0  1618.7     .05       0
#XS Ineff= 2 , 0
                         1177.28         2440.59
Permanent Ineff=
       F       F
Bank Sta=233.2,294.3
XS Rating Curve= 0 ,0
Exp/Cntr(USF)=0,0
Exp/Cntr=0.3,0.1

Type RM Length L Ch R = 1 ,101341  ,164.8,160.6,145.1
XS GIS Cut Line= 2
2282824.41988974448428.1406038142280967.86917193449048.511359642
#Sta/Elev= 30
       0 2543.76    55.1 2528.04   133.8 2493.93     216  2450.7   236.4 2436.79
  251.22 2423.59   257.5 2422.14   295.5 2420.91  310.32 2423.62   427.8 2423.62
   451.5 2420.34   464.2 2418.47   481.5 2418.44     519 2418.63   527.4 2420.13
   543.5 2422.49   582.3 2423.32  1000.4 2422.53  1079.9 2424.43  1628.2 2421.77
  1641.6 2419.99  1666.1 2422.66  1679.6 2427.57  1712.5 2428.24    1721 2430.12
  1737.8 2446.26    1742 2447.82  1822.2 2456.86  1875.6 2467.63  1957.5 2504.57
#Mann= 10 ,-1,0
       0     .12       0      90      .1       0  251.22    .045       0
  310.32     .12       0     350     .05       0     390      .1       0
   451.5    .045       0   527.4     .05       0  1679.6    .016       0
  1712.5      .1       0
#XS Ineff= 2 ,-1
   446.7  553.42 2421.64 1177.55 1773.07    2430
Permanent Ineff=
       T       F
Bank Sta=251.22,310.32
XS Rating Curve= 0 ,0
Exp/Cntr(USF)=0,0
Exp/Cntr=0.3,0.1

Type RM Length L Ch R = 1 ,101180  ,545.5,513.6,267.1
XS GIS Cut Line= 4
 2282730.8522237448350.857324201 2282610.9393535448322.373478295
2282158.43363716448523.933146993 2280917.6921255448984.649664189
#Sta/Elev= 30
       0  2513.4    15.1 2508.88   101.4 2479.24   143.8 2461.72   170.1 2451.99
   205.1 2425.54  212.05  2422.4   228.5 2419.47   248.1 2422.34   257.6  2423.4
   283.9 2419.39   310.2 2423.86   410.9 2422.12   459.1 2422.06   472.2 2418.62
   476.6 2418.37   510.1 2419.85   548.6 2423.92     860 2421.79  1098.9 2424.13
  1607.7  2419.6  1629.5 2421.84  1651.2 2428.58  1672.3 2428.99  1683.5  2430.1
  1709.1 2449.95  1730.4 2457.24  1798.7 2468.18  1831.7 2477.96  1942.1 2525.88
#Mann= 11 ,-1,0
       0      .1       0    15.1     .12       0   143.8      .1       0
  212.05    .045       0   248.1      .1       0   410.9     .05       0
   472.2    .045       0   510.1     .05       0  1651.2    .016       0
  1672.3      .1       0  1942.1      .1       0
#XS Ineff= 2 ,-1
  439.64   542.7 2421.02    1103 1732.64 2433.36
Permanent Ineff=
       T       F
Bank Sta=212.05,248.1
XS Rating Curve= 0 ,0
Exp/Cntr(USF)=0,0
Exp/Cntr=0.3,0.1

Type RM Length L Ch R = 1 ,100667  ,568.4,956.5,403.5
XS GIS Cut Line= 4
2282278.84855868447741.2768080382282049.27885595448455.493660983
2281825.17509852448566.6345488132280928.76006881448945.606756498
#Sta/Elev= 30
       0 2441.58     8.3 2439.51    20.9 2433.63   151.2 2424.88   239.4 2421.43
   277.2 2421.59   285.6 2419.51   344.4 2419.46   483.1 2420.54   516.7 2417.78
   541.9 2419.85   613.3 2418.75   622.1  2419.9   667.9 2417.14   684.8 2422.21
   726.3 2422.37   970.4  2421.1  1095.3 2423.03  1510.2 2422.31  1665.4  2419.6
  1689.8 2421.54  1705.4 2428.21    1731 2429.19  1739.7 2430.17    1757 2445.01
  1763.1 2448.55  1787.5 2457.31    1857 2471.81  1943.8  2510.3  1973.6 2521.87
#Mann= 8 ,-1,0
       0      .1       0   151.2     .06       0   239.4      .1       0
   285.6    .045       0   344.4      .1       0   726.3     .05       0
  1705.4    .016       0    1731      .1       0
#XS Ineff= 2 , 0
                         1097.17         2442.68
Permanent Ineff=
       F       F
#Block Obstruct= 2 ,-1
       0   37.53 2461.58   97.83  107.64 2447.56
Bank Sta=285.6,344.4
XS Rating Curve= 0 ,0
Exp/Cntr(USF)=0,0
Exp/Cntr=0.3,0.1

Type RM Length L Ch R = 1 ,99710   ,322.2,553.6,492.8
XS GIS Cut Line= 3
2281652.10162321447657.2387087042281747.89416639448555.863994719
2280867.51507907448920.787968736
#Sta/Elev= 30
       0 2427.71    60.3    2425   390.1 2418.42   402.2 2416.38   454.6 2417.69
     498 2417.27   506.8 2415.81   559.1 2418.26   611.4 2417.63   627.5  2415.3
   675.7 2417.52     724 2417.47   735.52415.484   785.2 2413.93     8022414.402
   864.4 2415.54   876.9 2421.76   925.9 2423.07  1353.7 2422.21  1492.3 2420.94
    1501 2419.02  1526.9 2420.68  1544.3 2428.53  1574.6 2429.59  1591.9 2446.63
  1596.3  2449.4    1630 2461.18  1674.2 2472.44  1752.4 2507.09  1856.7 2540.75
#Mann= 8 ,-1,0
       0     .05       0     390      .1       0     490     .08       0
     690      .1       0   735.5    .045       0     802     .05       0
 1413.72     .04       0 1623.72      .1       0
#XS Ineff= 2 , 0
                         1305.59         2427.87
Permanent Ineff=
       F       F
Bank Sta=735.5,802
XS Rating Curve= 0 ,0
Exp/Cntr(USF)=0,0
Exp/Cntr=0.3,0.1

Type RM Length L Ch R = 1 ,99157   ,81.1,81.7,81.4
BEGIN DESCRIPTION:
structure xs 4
END DESCRIPTION:
XS GIS Cut Line= 3
2281399.69022807447595.0341299362281343.54301565 448589.64189271
2280766.02883081448822.251772714
#Sta/Elev= 30
       0 2427.99   146.4 2422.13   242.5 2421.38   278.8 2419.14   294.6 2415.95
   338.7 2414.83   358.7 2417.54   382.8 2416.51   390.8 2416.59   470.9 2415.16
   477.22413.173     515 2410.97   525.1 2412.81   599.1 2417.47   775.4 2419.03
   855.5 2421.77  1080.6 2421.98  1176.6 2419.34    1237 2419.55  1254.2 2429.17
  1281.2 2431.35  1290.5 2435.85  1305.8 2449.96    1355 2471.77  1385.8 2481.88
  1418.1 2493.62  1465.5 2506.74  1560.4  2514.8  1586.3 2520.89  1618.8 2531.96
#Mann= 7 ,-1,0
       0     .05       0   382.8    .016       0   390.8     .05       0
   477.2    .045       0   525.1     .05       0  1176.6     .04       0
  1385.8      .1       0
#XS Ineff= 2 , 0
                          690.62         2424.35
Permanent Ineff=
       F       F
Bank Sta=477.2,525.1
XS Rating Curve= 0 ,0
Exp/Cntr(USF)=0,0
Exp/Cntr=0.5,0.3

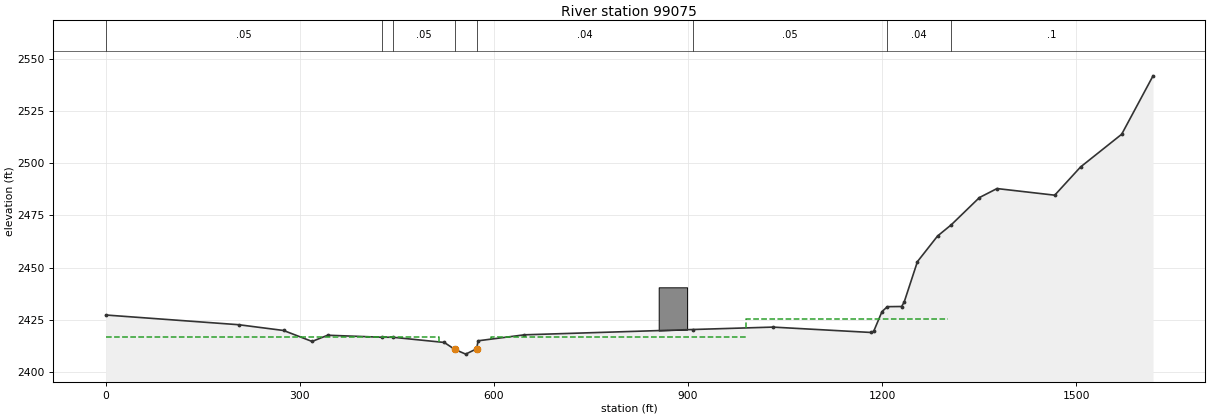
Type RM Length L Ch R = 1 ,99075   ,55.3,56.1,55.6
BEGIN DESCRIPTION:
Structure XS 3 - channel burned within banks
END DESCRIPTION:
XS GIS Cut Line= 3
2281320.88115952447554.825992438 2281264.7339471448549.433755212
2280687.21976226448782.043635216
#Sta/Elev= 30
       0 2427.25   205.6 2422.59   274.8 2419.83   318.9 2414.57   342.9 2417.55
   426.4 2416.59   443.3 2416.59   523.2 2414.09   539.2 2410.81  556.28 2408.49
  573.25 2411.04   575.5 2414.88   647.2 2417.75   907.8  2420.3  1031.3 2421.45
  1182.2 2418.89    1187 2419.44  1199.8 2428.88  1208.1 2431.25  1230.1 2431.33
    1234 2433.36  1254.6 2452.85  1285.7 2465.13  1306.9 2470.51  1350.4 2483.57
  1377.6 2487.89  1466.8 2484.71  1506.7 2498.23  1570.3 2513.93  1618.8 2541.95
#Mann= 8 ,-1,0
       0     .05       0   426.4    .016       0   443.3     .05       0
   539.2    .045       0  573.25     .04       0   907.8     .05       0
  1208.1     .04       0  1306.9      .1       0
#XS Ineff= 3 ,-1
       0     515  2416.6     595  989.17  2416.7  989.17 1302.06 2425.24
Permanent Ineff=
       F       F       F
#Block Obstruct= 1 ,-1
  854.64  898.54 2440.53
Bank Sta=539.2,573.25
XS Rating Curve= 0 ,0
Exp/Cntr(USF)=0,0
Exp/Cntr=0.5,0.3