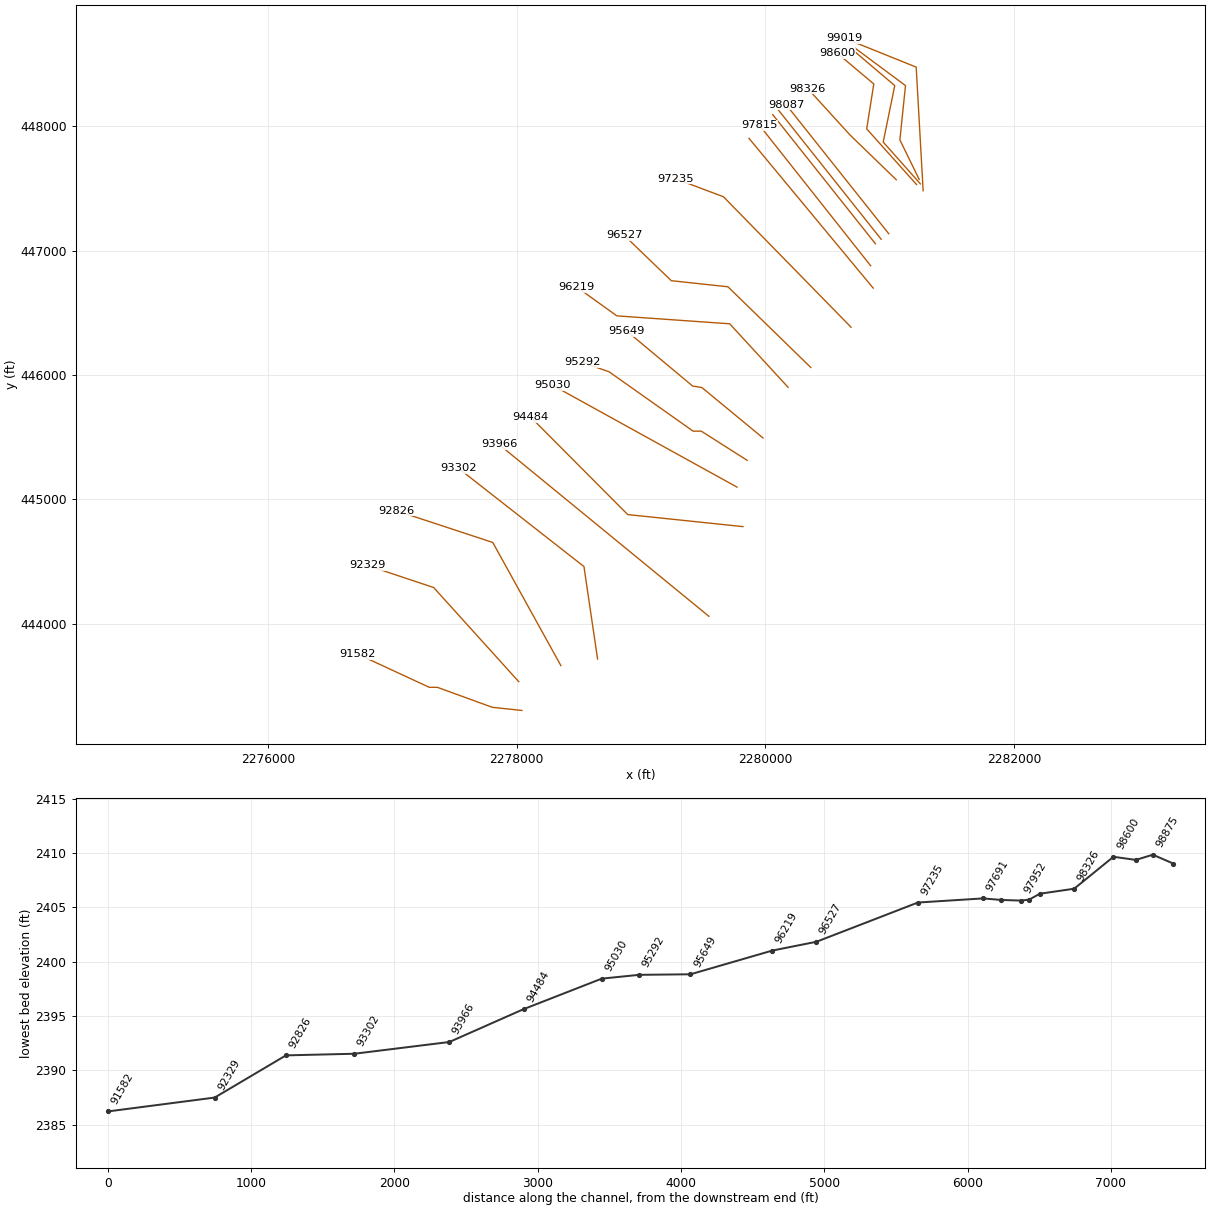
HEC-RAS study KNAPPCK.prj: KNAPPCK

--- KNAPPCK.g01 (geometry) --- (continued)

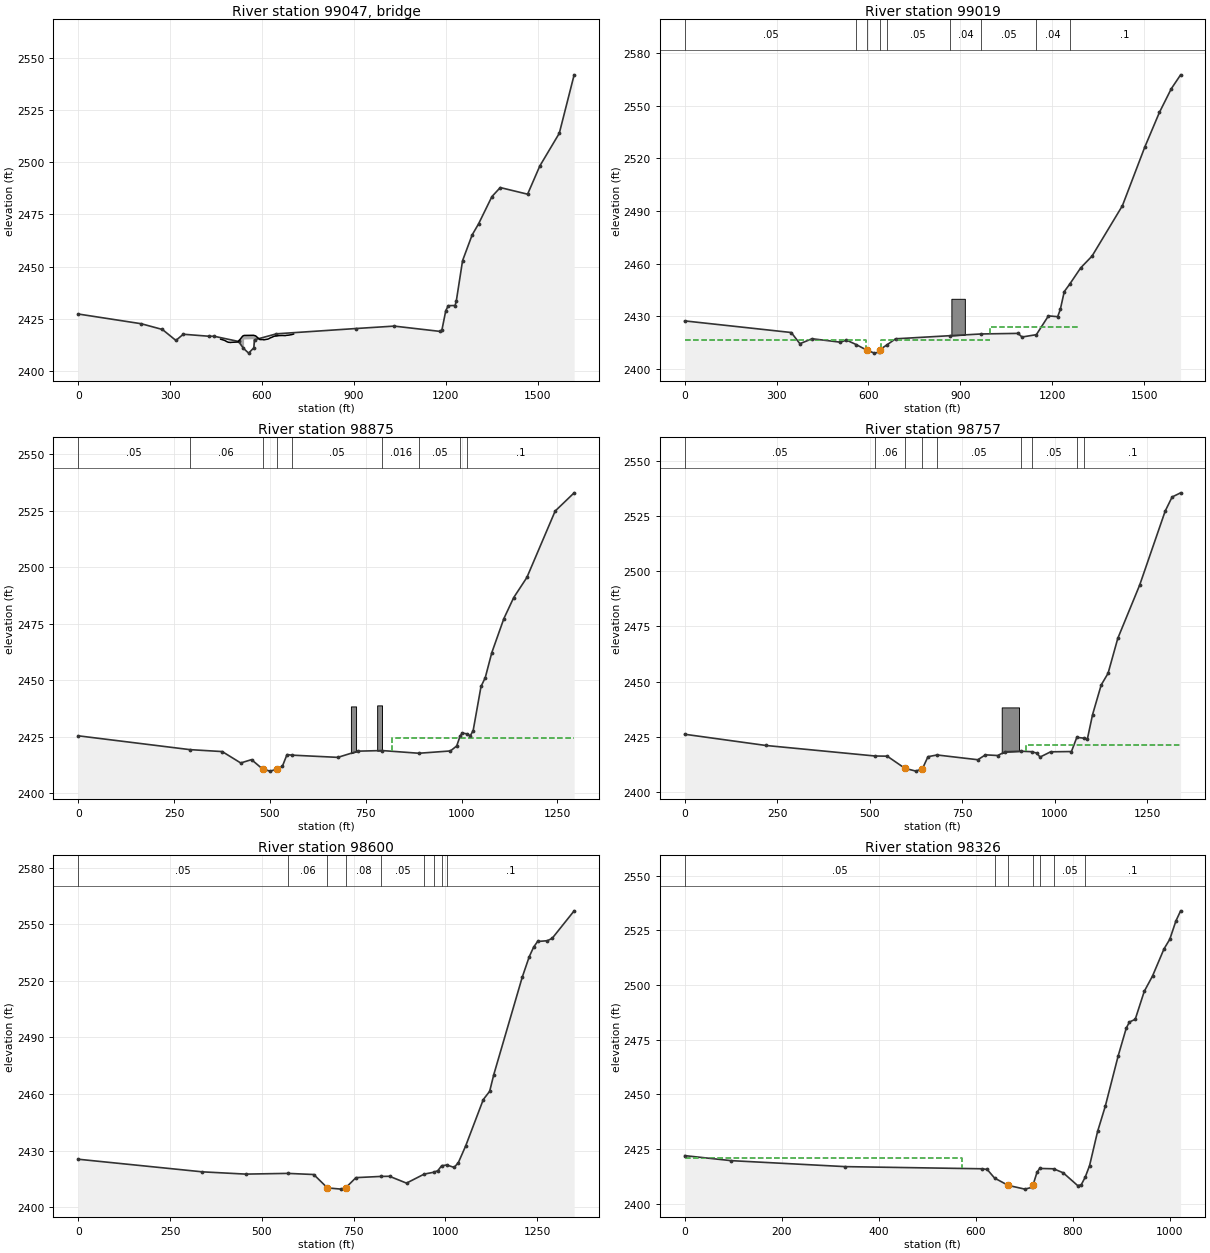
Type RM Length L Ch R = 3 ,99047   ,,,
BEGIN DESCRIPTION:
Unnamed Road- wooden bridge
Bridge data: 54075KNA070
Width: 13' (measured on orthoimagery)
Structure has wooden railing which was not modeled since flows are not obstructed
Structure bounding sections incorporate channel data from survey.
Deck from Lidar with survey data incorporated
END DESCRIPTION:
Bridge Culvert--1,0,-1,-1, 0
Deck Dist Width WeirC Skew NumUp NumDn MinLoCord MaxHiCord MaxSubmerge Is_Ogee
22,13,2.6,0, 97, 97, , , 0.98, 0, 0,0,,
     465  466.19  466.34  466.51  470.03  470.35  473.87  474.35  478.35  483.24
  485.39  486.36  487.42  489.23  490.37   491.6  493.08  495.78  496.92  498.37
     499   521.5  536.79  541.47  554.85  572.27  579.17  592.88  606.31  606.47
  608.31  608.64  610.47  612.15  612.82  614.48     616     617  618.48  619.84
  621.18  622.48  623.68  625.07  625.46  626.53  627.17  629.69  630.66  630.99
  633.75  634.78  636.52  637.04  638.91  640.34  642.05  643.04  646.92  647.16
  647.58  650.21  651.29   653.1   653.5  655.42  656.79  658.63  660.09  662.22
  663.38  663.67   667.8  669.69  669.96  671.92  673.25  676.05  676.54  680.18
  680.75  683.13   684.3  686.28  688.43  689.71  691.81  692.56     693  694.75
  696.29  696.68  697.34  699.58  700.81  702.87  702.92
 2415.16  2415.1  2415.1 2415.09 2414.95 2414.93 2414.78 2414.76 2414.54 2414.15
 2413.98  2413.9 2413.85 2413.75  2413.7 2413.68 2413.67 2413.62  2413.6 2413.58
 2413.66 2413.81 2416.66 2416.98    2417 2417.05 2416.75 2414.99    2415 2414.88
 2414.93 2414.94    2415 2415.04 2415.06  2415.1 2415.13 2415.16 2415.19 2415.26
 2415.35 2415.42 2415.52 2415.65 2415.68 2415.78 2415.81 2415.95 2415.99 2416.02
  2416.2 2416.28 2416.39 2416.43 2416.55  2416.6 2416.63 2416.66 2416.74 2416.74
 2416.75 2416.79  2416.8 2416.84 2416.85  2416.9  2416.9 2416.92 2416.92 2416.93
 2416.93 2416.94 2416.94 2416.92 2416.92 2416.91  2416.9  2416.9 2416.91 2417.04
 2417.04 2417.06 2417.08 2417.11 2417.15 2417.18 2417.25 2417.26 2417.28 2417.32
 2417.34 2417.35 2417.38 2417.49 2417.54 2417.63 2417.63
                                                                                
                                                                                
                         2415.01 2415.08 2415.17
                                                                                
                                                                                
                                                                                
                                                                                
                                                                                
                                                                                
                                                        
     528  529.19  529.34  529.51  533.03  533.35  536.87  537.35  541.35  546.24
  548.39  549.36  550.42  552.23  553.37   554.6  556.08  558.78  559.92  561.37
     562   584.5  599.79  604.47  617.85  635.27  642.17  655.88  669.31  669.47
  671.31  671.64  673.47  675.15  675.82  677.48     679     680  681.48  682.84
  684.18  685.48  686.68  688.07  688.46  689.53  690.17  692.69  693.66  693.99
  696.75  697.78  699.52  700.04  701.91  703.34  705.05  706.04  709.92  710.16
  710.58  713.21  714.29   716.1   716.5  718.42  719.79  721.63  723.09  725.22
  726.38  726.67   730.8  732.69  732.96  734.92  736.25  739.05  739.54  743.18
  743.75  746.13   747.3  749.28  751.43  752.71  754.81  755.56     756  757.75
  759.29  759.68  760.34  762.58  763.81  765.87  765.92
 2415.16  2415.1  2415.1 2415.09 2414.95 2414.93 2414.78 2414.76 2414.54 2414.15
 2413.98  2413.9 2413.85 2413.75  2413.7 2413.68 2413.67 2413.62  2413.6 2413.58
 2413.66 2413.81 2416.66 2416.98    2417 2417.05 2416.75 2414.99    2415 2414.88
 2414.93 2414.94    2415 2415.04 2415.06  2415.1 2415.13 2415.16 2415.19 2415.26
 2415.35 2415.42 2415.52 2415.65 2415.68 2415.78 2415.81 2415.95 2415.99 2416.02
  2416.2 2416.28 2416.39 2416.43 2416.55  2416.6 2416.63 2416.66 2416.74 2416.74
 2416.75 2416.79  2416.8 2416.84 2416.85  2416.9  2416.9 2416.92 2416.92 2416.93
 2416.93 2416.94 2416.94 2416.92 2416.92 2416.91  2416.9  2416.9 2416.91 2417.04
 2417.04 2417.06 2417.08 2417.11 2417.15 2417.18 2417.25 2417.26 2417.28 2417.32
 2417.34 2417.35 2417.38 2417.49 2417.54 2417.63 2417.63
                                                                                
                                                                                
                         2415.01 2415.08 2415.17
                                                                                
                                                                                
                                                                                
                                                                                
                                                                                
                                                                                
                                                        
BR Coef=-1 ,-1 , 0 ,, 0 ,,,0.8,0,1.2,0,
WSPro=,,,, 1 ,,,, 0 ,,,, 0 ,,,,-1 ,-1 ,-1 , 0 , 0 , 0 , 0 , 0
BR U #Sta/Elev= 30
       0 2427.25   205.6 2422.59   274.8 2419.83   318.9 2414.57   342.9 2417.55
   426.4 2416.59   443.3 2416.59   523.2 2414.09   539.2 2410.81  556.28 2408.49
  573.25 2411.04   575.5 2414.88   647.2 2417.75   907.8  2420.3  1031.3 2421.45
  1182.2 2418.89    1187 2419.44  1199.8 2428.88  1208.1 2431.25  1230.1 2431.33
    1234 2433.36  1254.6 2452.85  1285.7 2465.13  1306.9 2470.51  1350.4 2483.57
  1377.6 2487.89  1466.8 2484.71  1506.7 2498.23  1570.3 2513.93  1618.8 2541.95
BR U #Mann= 8
       0     .05   426.4    .016   443.3     .05   539.2     .04  573.25     .04
   907.8     .05  1208.1     .04  1306.9      .1
BR D #Sta/Elev= 30
       0  2427.4   347.8 2420.78   376.1  2414.4   415.9 2417.22   508.1 2415.26
   528.1 2416.45   560.2 2413.87     596 2410.57  619.57 2409.02  635.89 2409.67
   636.3 2410.87   660.1 2413.73   688.4 2417.18   864.6 2418.95   968.8 2419.95
  1088.1 2420.28    1101 2418.21  1147.9 2419.54  1187.3 2430.25  1217.5 2429.81
  1226.1 2433.94    1239 2444.11  1256.3 2448.23  1292.8 2457.67  1329.7 2464.36
  1428.8 2493.08  1501.8 2526.49  1549.5 2546.25  1588.3 2559.77  1618.8  2567.7
BR D #Mann= 9
       0     .05   560.2     .04     596     .04   636.3     .04   660.1     .05
   864.6     .04   968.8     .05  1147.9     .04  1256.3      .1
BC Design=,, 0 ,, 0 ,,,,,,
BC Use User HTab Curves=0
BC User HTab FreeFlow(D)= 0

Type RM Length L Ch R = 1 ,99019   ,155,144.1,125.1
BEGIN DESCRIPTION:
Structure XS 2 - channel burned within banks
END DESCRIPTION:
XS GIS Cut Line= 3
2281269.56722062447481.908120026 2281213.4200082  448476.5158828
2280635.90582336448709.125762804
#Sta/Elev= 30
       0  2427.4   347.8 2420.78   376.1  2414.4   415.9 2417.22   508.1 2415.26
   528.1 2416.45   560.2 2413.87     596 2410.57  619.57 2409.02  635.89 2409.67
   636.3 2410.87   660.1 2413.73   688.4 2417.18   864.6 2418.95   968.8 2419.95
  1088.1 2420.28    1101 2418.21  1147.9 2419.54  1187.3 2430.25  1217.5 2429.81
  1226.1 2433.94    1239 2444.11  1256.3 2448.23  1292.8 2457.67  1329.7 2464.36
  1428.8 2493.08  1501.8 2526.49  1549.5 2546.25  1588.3 2559.77  1618.8  2567.7
#Mann= 9 ,-1,0
       0     .05       0   560.2     .04       0     596    .045       0
   636.3     .04       0   660.1     .05       0   864.6     .04       0
   968.8     .05       0  1147.9     .04       0  1256.3      .1       0
#XS Ineff= 3 ,-1
       0     593  2416.6     642  996.61  2416.7  996.61 1286.96 2424.09
Permanent Ineff=
       F       F       F
#Block Obstruct= 1 ,-1
  870.57  914.46    2440
Bank Sta=596,636.3
XS Rating Curve= 0 ,0
Exp/Cntr(USF)=0,0
Exp/Cntr=0.5,0.3

Type RM Length L Ch R = 1 ,98875   ,120.9,117.9,108.2
BEGIN DESCRIPTION:
structure xs 1
END DESCRIPTION:
XS GIS Cut Line= 4
2281237.65271939447573.4494675652281082.36064457447891.092347894
2281127.48354596448327.8436727152280725.03145924448626.694232165
#Sta/Elev= 30
       0 2425.47     291 2419.36   375.8 2418.49     424 2413.45   452.2 2414.93
     481 2410.77   500.4 2409.84   519.8 2410.73   532.6 2411.95   544.7 2417.15
   556.7 2416.92   677.4 2415.93   729.6 2418.68   793.1 2418.94   888.8 2417.75
   971.1 2418.77   987.5 2420.98   996.1 2425.24  1001.8 2426.71  1013.3 2426.36
    1023 2425.53  1030.4 2427.77  1050.9  2447.3  1061.9 2451.17    1079 2462.24
  1110.6 2477.37  1136.2 2486.64  1170.6 2495.55  1244.4 2524.94  1293.9 2532.99
#Mann= 9 ,-1,0
       0     .05       0     291     .06       0     481    .045       0
   519.8     .08       0   556.7     .05       0   793.1    .016       0
   888.8     .05       0   996.1    .016       0  1013.3      .1       0
#XS Ineff= 2 , 0
                          818.31         2424.44
Permanent Ineff=
       F       F
#Block Obstruct= 2 ,-1
  711.47  724.92 2438.47  779.95  792.65 2438.93
Bank Sta=481,519.8
XS Rating Curve= 0 ,0
Exp/Cntr(USF)=0,0
Exp/Cntr=0.3,0.1

Type RM Length L Ch R = 1 ,98757   ,155,156.4,160.1
Node Name=AK
XS GIS Cut Line= 4
2281247.02376974447537.5499710592280948.17321029447873.590822351
 2281041.1489399448327.8436727152280715.73388628448604.114412117
#Sta/Elev= 30
       0 2426.09     219 2421.01   514.6 2416.22   547.3 2416.15   595.1 2410.64
   624.9 2409.36   642.5 2410.47   657.5 2415.91     682 2416.69   792.3 2414.53
   812.7 2416.75   845.9 2416.44   865.7 2418.13   908.5 2418.39   937.7 2418.18
   951.4 2417.53   960.4 2415.74   988.8 2418.12  1045.2 2418.25  1059.7 2424.69
  1079.6  2424.3  1088.1 2423.84  1102.3 2435.04  1125.6 2448.46  1144.1 2453.74
  1170.4 2469.59  1229.5 2493.76  1298.6 2527.39  1317.2 2533.74  1340.2 2535.63
#Mann= 9 ,-1,0
       0     .05       0   514.6     .06       0   595.1    .045       0
   642.5     .08       0     682     .05       0   908.5    .016       0
   937.7     .05       0  1059.7    .016       0  1079.6      .1       0
#XS Ineff= 2 , 0
                          923.13         2421.42
Permanent Ineff=
       F       F
#Block Obstruct= 1 ,-1
  856.76  903.52 2438.27
Bank Sta=595.1,642.5
XS Rating Curve= 0 ,0
Exp/Cntr(USF)=0,0
Exp/Cntr=0.3,0.1

Type RM Length L Ch R = 1 ,98600   ,227.4,274.5,334
XS GIS Cut Line= 4
2281216.47460144447532.2370722242280815.35073943447979.848799044
 2280872.4644019448341.1259198022280578.92674129448588.175715613
#Sta/Elev= 30
       0 2425.49     338 2418.81     456 2417.61   570.6 2417.99   641.4 2417.39
   678.6 2410.31   715.8 2409.65   728.8 2410.42   756.3 2415.74   825.1 2416.39
   847.7 2416.45     894 2412.83   942.1 2417.61   968.8 2418.62   979.3 2419.44
   989.8 2422.06  1004.2 2422.42  1023.8 2421.14  1035.2 2423.71  1055.1 2432.54
  1103.1 2457.12  1120.4 2461.48  1131.7 2470.37  1209.2 2521.97  1228.2 2532.81
  1240.2 2537.87  1250.9 2540.86  1277.5 2541.26  1290.7 2542.54  1350.5  2557.1
#Mann= 9 ,-1,0
       0     .05       0   570.6     .06       0   678.6    .045       0
   728.8     .08       0   825.1     .05       0   942.1    .016       0
   968.8     .05       0   989.8    .016       0  1004.2      .1       0
Bank Sta=678.6,728.8
XS Rating Curve= 0 ,0
Exp/Cntr(USF)=0,0
Exp/Cntr=0.3,0.1

Type RM Length L Ch R = 1 ,98326   ,243.6,239.4,236.5
XS GIS Cut Line= 3
2281053.10296228447570.7555887752280681.20004385447930.704484824
2280341.17451843448303.935627959
#Sta/Elev= 30
       0 2422.02    95.5 2419.73   331.3 2416.99   612.9 2416.01   623.7  2415.7
     639 2411.75     667 2408.42   701.3 2406.71   715.4 2407.49   718.2 2408.61
   726.5 2414.45   731.9 2416.16   760.7    2416   780.4 2414.17   810.1 2408.36
   817.4 2408.64   825.8 2412.17   834.8 2417.48   851.3 2433.05   867.2  2444.6
   893.8 2467.63   910.5 2480.34     917 2483.07   928.9 2484.31   947.6 2497.12
   964.6 2504.11   988.3 2516.51  1000.2  2520.9  1012.7  2529.2  1022.5 2533.88
#Mann= 7 ,-1,0
       0     .05       0     639     .08       0     667    .045       0
   718.2     .08       0   731.9    .016       0   760.7     .05       0
   825.8      .1       0
#XS Ineff= 2 , 0
          572.75 2420.88
Permanent Ineff=
       F       F
Bank Sta=667,718.2
XS Rating Curve= 0 ,0
Exp/Cntr(USF)=0,0
Exp/Cntr=0.3,0.1

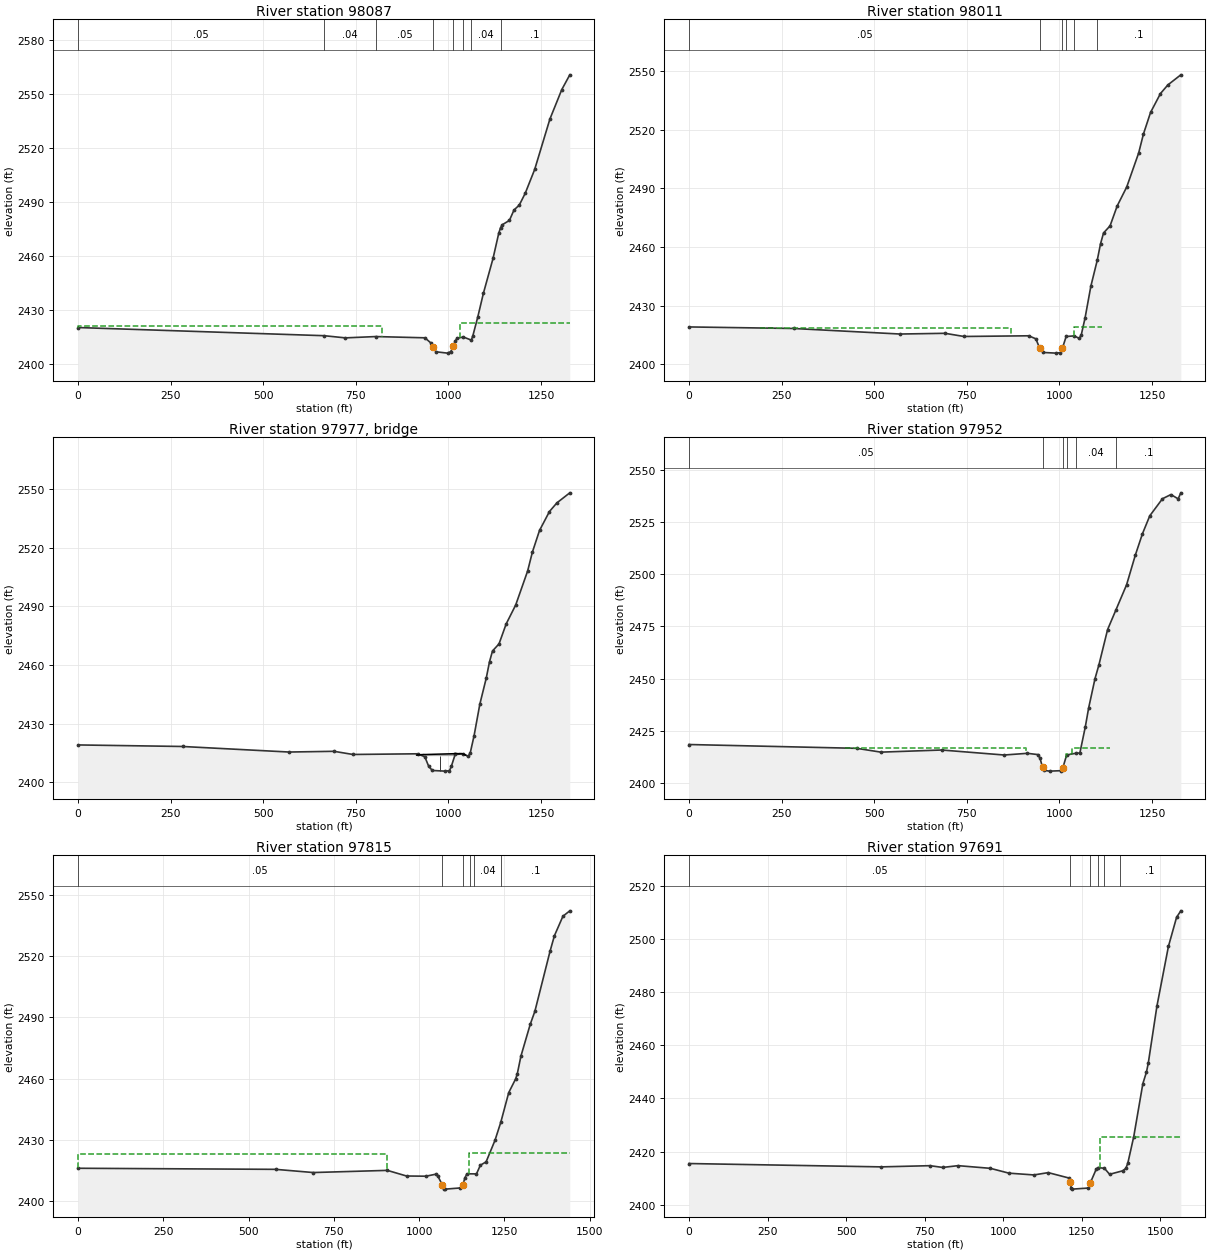
Type RM Length L Ch R = 1 ,98087   ,76,75.4,75.4
BEGIN DESCRIPTION:
structure xs 4
END DESCRIPTION:
XS GIS Cut Line= 2
2280992.91811666447136.297769916  2280166.727016448175.391961904
#Sta/Elev= 30
       0 2420.45   664.5 2415.92   721.7 2414.71   803.4 2415.44   936.3 2414.75
     952 2411.98   958.8 2409.62   966.2 2406.99   997.4 2406.25  1006.1 2407.07
    1013 2410.01  1018.1 2412.92  1023.1 2414.49  1040.2  2415.2  1061.7 2413.46
  1065.9 2415.94  1079.4 2426.54  1094.3 2439.47  1120.3 2458.78  1135.6 2472.67
  1140.7 2475.87  1145.2 2477.47  1164.5 2479.88  1176.9 2485.66  1191.1 2488.37
  1207.2 2494.93  1232.7 2508.14  1273.8 2536.11  1305.9 2552.47  1327.5 2560.64
#Mann= 8 ,-1,0
       0     .05       0   664.5     .04       0   803.4     .05       0
   958.8    .045       0    1013     .03       0  1040.2    .016       0
  1061.7     .04       0  1140.7      .1       0
#XS Ineff= 2 , 0
          820.55 2421.55 1031.79         2423.18
Permanent Ineff=
       F       F
Bank Sta=958.8,1013
XS Rating Curve= 0 ,0
Exp/Cntr(USF)=0,0
Exp/Cntr=0.5,0.3

Type RM Length L Ch R = 1 ,98011   ,58.9,58.7,58.7
BEGIN DESCRIPTION:
structure xs 3
END DESCRIPTION:
XS GIS Cut Line= 2
2280931.51155504 447092.350876952280105.32045437448131.445068937
#Sta/Elev= 30
       0  2419.1   282.1 2418.31   569.5 2415.47   690.9 2415.84   742.1 2414.22
   916.8 2414.57   936.2 2413.02   946.82408.085   956.6 2406.03   990.8  2405.7
  1002.7 2405.93  1007.9 2408.24    1018 2414.21  1040.1 2414.53  1053.4 2413.21
  1058.9 2415.14  1069.1 2423.79  1084.7 2439.99  1101.8 2453.13  1110.8 2461.68
  1118.9 2467.19  1136.5 2470.82  1155.8 2481.04  1181.5 2490.72  1213.7 2508.11
  1226.5 2517.75  1245.8 2528.85  1272.6 2538.53  1292.6 2542.94  1327.5 2548.09
#Mann= 6 ,-1,0
       0     .05       0   946.8    .045       0  1007.9     .03       0
    1018    .016       0  1040.1     .04       0  1101.8      .1       0
#XS Ineff= 4 ,-1
  191.66  869.97  2418.7  869.97     914  2414.2    1036 1038.92  2414.6
 1038.92 1114.232419.271
Permanent Ineff=
       F       F       F       F
Bank Sta=946.8,1007.9
XS Rating Curve= 0 ,0
Exp/Cntr(USF)=0,0
Exp/Cntr=0.5,0.3

Type RM Length L Ch R = 3 ,97977   ,,,
BEGIN DESCRIPTION:
Unnamed Road
Bridge data: 54075KNA060
Width: 13.3' (measured on orthoimagery)
Structure was not fully surveyed due to damage to the bridge, invert from lidar
A triangular nose pier exists on this bridge as seen in images, but pier data is not available, pier assumed 2' per imagery
No channel data available
Deck from Lidar
END DESCRIPTION:
Bridge Culvert--1,0,-1,-1, 0
Deck Dist Width WeirC Skew NumUp NumDn MinLoCord MaxHiCord MaxSubmerge Is_Ogee
27,13.3,2.6,0, 36, 36, , , 0.98, 0, 0,0,,
     914  915.28  918.12  919.09  920.97  923.34  923.82   924.2  926.67   929.3
  929.51  929.78  932.36  934.41  939.41 1014.93 1016.11 1017.77 1019.87 1020.62
 1021.22 1023.47  1026.3 1026.39 1029.16 1031.43 1032.01 1034.86 1036.54  1037.7
 1039.18 1040.55 1041.64 1045.61 1046.24 1046.27
  2413.9 2413.94    2414 2414.01 2414.04 2414.06 2414.06 2414.07 2414.14 2414.16
 2414.17 2414.17 2414.23 2414.21 2414.21 2414.62 2414.74 2414.75 2414.72 2414.71
 2414.71 2414.68 2414.63 2414.63 2414.69  2414.7  2414.7 2414.69 2414.64 2414.56
 2414.47 2414.38 2414.29 2413.91 2413.86 2413.86
                                                                                
                                 2413.38 2413.38
                                                                                
                                                
     914  915.28  918.12  919.09  920.97  923.34  923.82   924.2  926.67   929.3
  929.51  929.78  932.36  934.41  939.41 1014.93 1016.11 1017.77 1019.87 1020.62
 1021.22 1023.47  1026.3 1026.39 1029.16 1031.43 1032.01 1034.86 1036.54  1037.7
 1039.18 1040.55 1041.64 1045.61 1046.24 1046.27
  2413.9 2413.94    2414 2414.01 2414.04 2414.06 2414.06 2414.07 2414.14 2414.16
 2414.17 2414.17 2414.23 2414.21 2414.21 2414.62 2414.74 2414.75 2414.72 2414.71
 2414.71 2414.68 2414.63 2414.63 2414.69  2414.7  2414.7 2414.69 2414.64 2414.56
 2414.47 2414.38 2414.29 2413.91 2413.86 2413.86
                                                                                
                                 2413.38 2413.38
                                                                                
                                                
Pier Skew, UpSta & Num, DnSta & Num=  ,977.15, 2 ,977.15, 2 , 0 , 0 , 0 ,,
       2       2
       0    2414
       2       2
       0    2414
BR Coef=-1 ,-1 , 0 ,1.05, 0 ,,,0.8,0,1.6,0,
WSPro=,,,, 1 ,,,, 0 ,,,, 0 ,,,,-1 ,-1 ,-1 , 0 , 0 , 0 , 0 , 0
BR U #Sta/Elev= 30
       0  2419.1   282.1 2418.31   569.5 2415.47   690.9 2415.84   742.1 2414.22
   916.8 2414.57   936.2 2413.02   946.82408.085   956.6 2406.03   990.8  2405.7
  1002.7 2405.93  1007.9 2408.24    1018 2414.21  1040.1 2414.53  1053.4 2413.21
  1058.9 2415.14  1069.1 2423.79  1084.7 2439.99  1101.8 2453.13  1110.8 2461.68
  1118.9 2467.19  1136.5 2470.82  1155.8 2481.04  1181.5 2490.72  1213.7 2508.11
  1226.5 2517.75  1245.8 2528.85  1272.6 2538.53  1292.6 2542.94  1327.5 2548.09
BR U #Mann= 6
       0     .05   946.8     .04  1007.9     .03    1018    .016  1040.1     .04
  1101.8      .1
BR D #Sta/Elev= 30
       0 2418.38   452.3 2416.56   517.8 2414.73     682 2415.75   850.6 2413.35
   913.5 2414.16   942.6 2413.53   947.6 2411.71   954.22407.448     959 2405.97
   973.3 2405.62  1003.9 2405.83  1009.1 2407.25  1019.3 2413.36    1044 2414.19
    1055 2414.32  1069.7 2426.88  1078.6 2435.85  1095.9 2450.02  1106.2 2456.46
  1129.8  2473.5  1152.1 2482.85  1181.1    2495  1204.6 2509.17  1223.9 2519.47
  1243.7 2528.08  1277.9 2536.26  1300.7 2538.27  1320.3 2536.22  1327.5  2539.1
BR D #Mann= 6
       0     .05   954.2     .04  1009.1     .03  1019.3    .016    1044     .04
  1152.1      .1
BC Design=,, 0 ,, 0 ,,,,,,
BC Use User HTab Curves=0
BC User HTab FreeFlow(D)= 0

Type RM Length L Ch R = 1 ,97952   ,139.8,137.8,137.8
BEGIN DESCRIPTION:
structure xs 2
END DESCRIPTION:
XS GIS Cut Line= 2
2280885.89159262447055.3560890522280059.70049195448094.450281039
#Sta/Elev= 30
       0 2418.38   452.3 2416.56   517.8 2414.73     682 2415.75   850.6 2413.35
   913.5 2414.16   942.6 2413.53   947.6 2411.71   954.22407.448     959 2405.97
   973.3 2405.62  1003.9 2405.83  1009.1 2407.25  1019.3 2413.36    1044 2414.19
    1055 2414.32  1069.7 2426.88  1078.6 2435.85  1095.9 2450.02  1106.2 2456.46
  1129.8  2473.5  1152.1 2482.85  1181.1    2495  1204.6 2509.17  1223.9 2519.47
  1243.7 2528.08  1277.9 2536.26  1300.7 2538.27  1320.3 2536.22  1327.5  2539.1
#Mann= 6 ,-1,0
       0     .05       0   954.2    .045       0  1009.1     .03       0
  1019.3    .016       0    1044     .04       0  1152.1      .1       0
#XS Ineff= 4 ,-1
  422.06     909 2416.59     909     933  2413.6    1017 1034.84  2413.9
 1034.84 1137.33 2416.67
Permanent Ineff=
       F       F       F       F
Bank Sta=954.2,1009.1
XS Rating Curve= 0 ,0
Exp/Cntr(USF)=0,0
Exp/Cntr=0.5,0.3

Type RM Length L Ch R = 1 ,97815   ,124.8,124.1,125.1
BEGIN DESCRIPTION:
structure xs 1
END DESCRIPTION:
XS GIS Cut Line= 2
2280846.84944143446879.1930246642279952.23509564448009.518210156
#Sta/Elev= 30
       0 2415.93     579  2415.4   689.6 2413.83   906.7 2414.89   962.9 2412.13
  1019.9 2412.03  1048.4    2413  1054.1 2412.28  1067.8 2407.83  1073.8 2405.75
  1076.8 2405.68  1121.1 2406.27  1128.1 2407.64  1133.8 2411.15  1140.1  2413.2
    1168 2413.17  1179.3 2417.42  1196.2 2419.09  1222.1  2429.6  1239.1 2438.45
  1262.5 2453.09  1282.9 2459.88  1287.6 2462.32  1298.2    2471  1325.6 2486.68
  1339.1 2493.02  1383.6 2522.54  1396.5 2530.21  1421.4 2539.75  1441.5  2542.4
#Mann= 6 ,-1,0
       0     .05       0  1067.8    .045       0  1128.1     .04       0
    1150    .016       0    1160     .04       0    1240      .1       0
#XS Ineff= 2 , 0
          904.61 2422.91 1144.72         2423.46
Permanent Ineff=
       F       F
Bank Sta=1067.8,1128.1
XS Rating Curve= 0 ,0
Exp/Cntr(USF)=0,0
Exp/Cntr=0.3,0.1

Type RM Length L Ch R = 1 ,97691   ,443.8,455.1,453.9
XS GIS Cut Line= 2
2280867.51507907 446699.31327691 2279868.5357002447903.562391165
#Sta/Elev= 30
       0 2415.47   611.6 2414.21   766.4 2414.66   807.2    2414   855.9 2414.67
   958.7 2413.66  1017.8 2411.84  1097.4 2411.17  1142.8 2412.04  1208.2 2410.03
  1211.72408.432  1216.7 2406.12  1219.5 2405.82  1270.6 2406.23    1277 2408.26
  1295.8 2413.42  1301.7 2413.96  1321.8 2413.66  1338.1 2411.41  1379.7 2412.73
  1389.8 2413.66  1396.1 2415.63  1414.9  2425.6  1443.9 2445.59  1455.3 2449.94
    1461 2453.21  1488.8 2474.92  1525.2 2497.31  1551.2 2508.31  1564.7 2510.75
#Mann= 6 ,-1,0
       0     .05       0  1211.7    .045       0    1277     .04       0
    1300    .016       0    1320     .04       0    1370      .1       0
#XS Ineff= 2 , 0
                         1307.04         2425.33
Permanent Ineff=
       F       F
Bank Sta=1211.7,1277
XS Rating Curve= 0 ,0
Exp/Cntr(USF)=0,0
Exp/Cntr=0.3,0.1

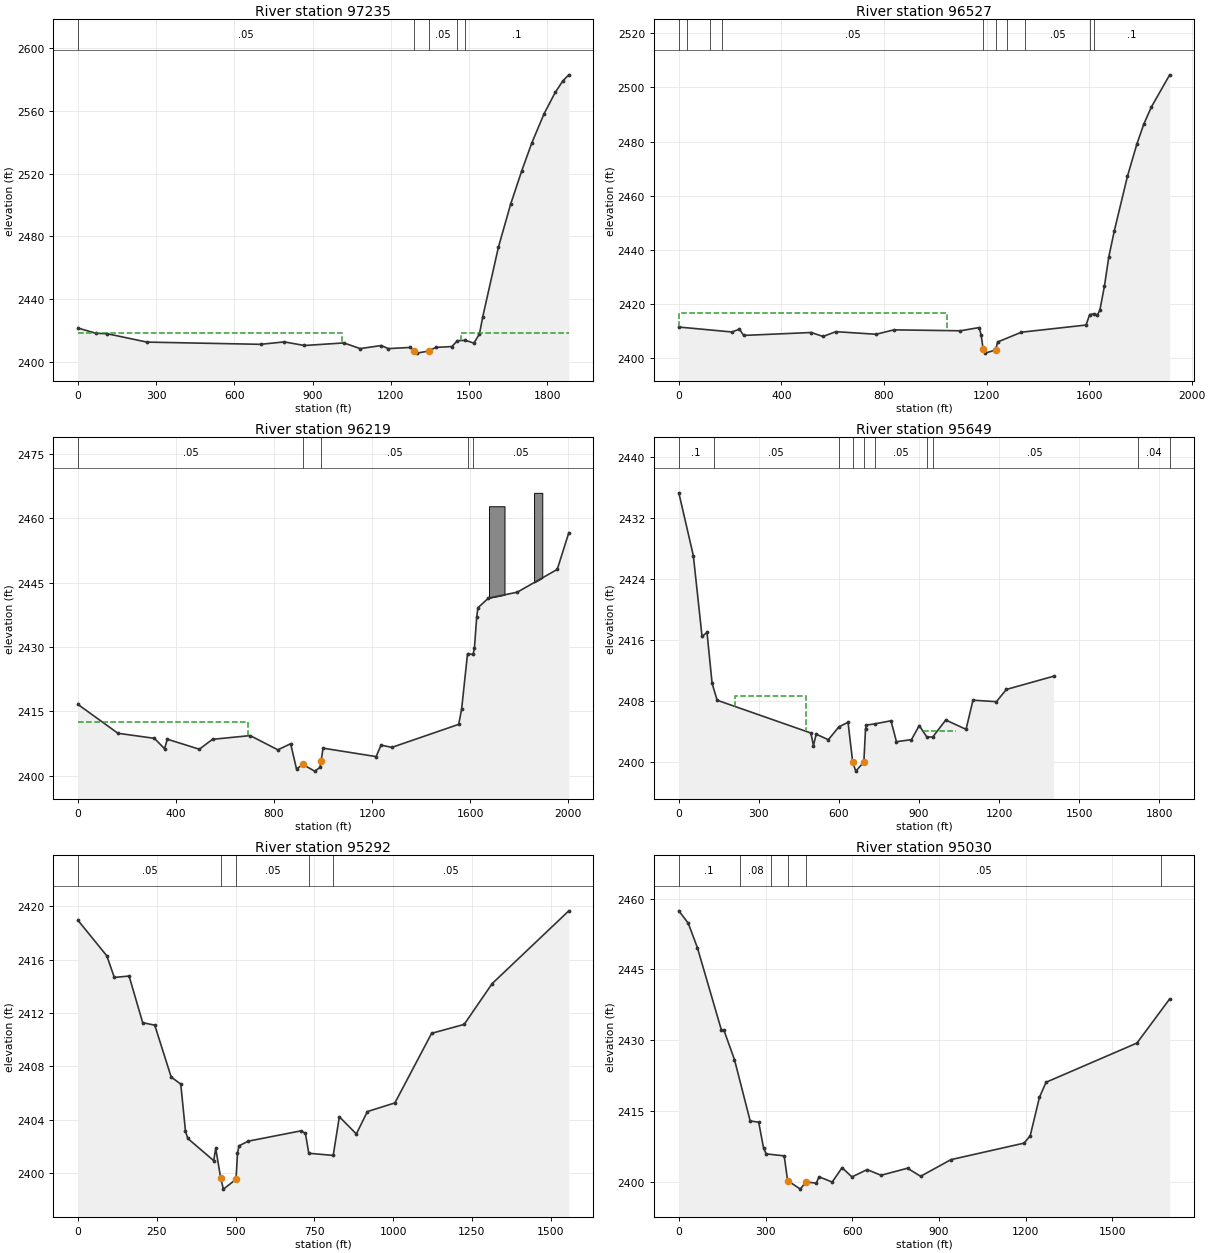
Type RM Length L Ch R = 1 ,97235   ,658.1,708.1,785.6
XS GIS Cut Line= 3
2280689.61464174446384.5663493212279663.26596482447433.722774619
2279275.53424243447579.692364225
#Sta/Elev= 30
       0 2421.47      68 2418.14   112.8  2417.8   264.5 2412.48   699.9 2411.06
   791.4 2412.61   868.2 2410.31  1019.7 2411.95    1082 2408.33  1163.2  2410.3
  1189.5 2408.32  1274.3 2409.08  1287.42406.909  1299.1 2405.44    1345 2406.77
  1371.8 2409.09  1433.4 2409.64    1455 2413.38  1485.2 2413.61    1518 2411.85
  1539.4 2417.67  1552.2 2428.77    1612 2472.98    1659 2500.53  1701.8 2521.93
  1740.3 2539.68  1787.3 2558.27    1830 2571.88  1859.9 2579.37    1882 2583.09
#Mann= 5 ,-1,0
       0     .05       0  1287.4    .045       0    1345     .05       0
    1455    .016       0  1485.2      .1       0
#XS Ineff= 2 , 0
         1013.07 2417.99 1468.11         2418.56
Permanent Ineff=
       F       F
Bank Sta=1287.4,1345
XS Rating Curve= 0 ,0
Exp/Cntr(USF)=0,0
Exp/Cntr=0.3,0.1

Type RM Length L Ch R = 1 ,96527   ,345.6,308,310.2
Node Name=AJ
XS GIS Cut Line= 4
 2280365.7446148446060.6963223812279699.41914003446709.643512723
2279243.55930175446758.8370204522278864.99311438447123.059223722
#Sta/Elev= 30
       0 2411.47   207.1 2409.64   236.2 2410.68   252.9 2408.37   516.3 2409.45
   562.5 2407.98   612.4 2409.76   768.9  2408.8   838.7 2410.43  1098.3 2410.09
  1170.8 2411.27  1178.8 2408.62  1186.8 2403.19  1194.9 2401.83  1235.1 2402.99
  1243.2 2405.95  1335.7 2409.56  1587.9 2412.21    1602 2416.06    1617 2416.37
    1632 2415.95  1641.6 2417.61  1659.8 2426.67  1676.4 2437.27  1698.2 2447.04
  1749.1 2467.08  1785.9 2479.01  1813.2 2486.47  1842.9  2492.8    1914 2504.64
#Mann= 10 ,-1,0
       0      .1       0      30     .05       0     120      .1       0
     170     .05       0  1186.8    .045       0  1235.1     .05       0
    1280     .08       0    1350     .05       0    1602    .016       0
    1617      .1       0
#XS Ineff= 2 , 0
         1046.37 2416.74
Permanent Ineff=
       F       F
Bank Sta=1186.8,1235.1
XS Rating Curve= 0 ,0
Exp/Cntr(USF)=0,0
Exp/Cntr=0.3,0.1

Type RM Length L Ch R = 1 ,96219   ,591.7,570.4,387.2
XS GIS Cut Line= 4
2280183.28262779445901.0420837492279713.44301125446411.935647372
2278805.69462588446475.7973428252278481.82459894446708.436376261
#Sta/Elev= 30
       0 2416.58   163.2 2409.85   311.9 2408.67   353.3 2406.25   364.7 2408.47
   495.1 2406.13   549.1 2408.44   702.7 2409.31   815.7 2405.99   867.8 2407.41
   891.8 2401.52   917.5 2402.57   965.9 2401.02   988.1 2401.88   992.1 2403.35
  1000.1 2406.38  1216.6 2404.41  1236.7 2407.09  1280.8 2406.56  1553.5 2411.93
  1565.4 2415.47  1589.6 2428.43  1611.9 2428.23  1617.6 2429.63    1627 2436.97
    1632 2439.12  1674.9 2441.38  1792.5 2442.76  1955.6 2448.08  2002.8 2456.64
#Mann= 5 ,-1,0
       0     .05       0   917.5    .045       0   992.1     .05       0
  1589.6    .016       0  1611.9     .05       0
#XS Ineff= 2 , 0
          693.24 2412.59
Permanent Ineff=
       F       F
#Block Obstruct= 2 ,-1
 1677.28 1740.47 2462.81 1861.15  1894.6 2465.94
Bank Sta=917.5,992.1
XS Rating Curve= 0 ,0
Exp/Cntr(USF)=0,0
Exp/Cntr=0.3,0.1

Type RM Length L Ch R = 1 ,95649   ,314.1,357.2,342.5
XS GIS Cut Line= 4
2279981.44002421445493.8398801882279489.52684039445899.590418796
 2279415.7365788445911.0689039332278884.16846631446354.426164361
#Sta/Elev= 30
       0 2435.26    54.4 2427.04      87 2416.47   105.6 2416.99   124.7 2410.34
   143.5 2408.12   494.8 2403.83   504.6 2402.19   514.7 2403.68   560.2 2402.95
     600 2404.64   634.2 2405.22   651.82399.975   663.3 2398.84   693.42400.031
   699.8 2404.41   703.3 2404.87   734.4 2405.02   795.1 2405.43   815.6 2402.69
   871.8 2402.96     901  2404.8   929.4 2403.31   951.4  2403.3  1000.4 2405.53
  1076.4 2404.31  1102.4 2408.12  1190.3 2407.93  1227.4 2409.53  1404.5 2411.26
#Mann= 10 ,-1,0
       0      .1       0     130     .05       0     600     .08       0
   651.8    .045       0   693.4     .08       0   734.4     .05       0
   929.4    .045       0   951.4     .05       0    1720     .04       0
 1839.55     .05       0
#XS Ineff= 2 ,-1
  212.05  476.42 2408.64   917.9  1039.5 2404.03
Permanent Ineff=
       F       T
Bank Sta=651.8,693.4
XS Rating Curve= 0 ,0
Exp/Cntr(USF)=0,0
Exp/Cntr=0.3,0.1

Type RM Length L Ch R = 1 ,95292   ,260.8,262,269.8
XS GIS Cut Line= 5
2279853.55879758445314.1876768292279484.60748962445548.676730334
2279419.01614598445548.6767303342278743.42530651446025.853755299
 2278528.6136561446101.283800482
#Sta/Elev= 30
       0 2418.96    91.7 2416.29   115.4 2414.67   162.2 2414.78   205.4 2411.28
   243.7 2411.09   295.8  2407.2   326.2 2406.67   341.2 2403.14   348.6 2402.59
   430.6 2400.93   437.2 2401.84   453.1 2399.59   461.6 2398.79   501.6 2399.53
   506.2 2401.47   511.1 2402.04   540.5 2402.39     707 2403.16   721.7 2402.98
   732.4 2401.48   809.9 2401.32   829.4 2404.22   883.3 2402.93   918.4 2404.61
  1005.7 2405.26  1122.2 2410.48  1225.5 2411.15  1314.3 2414.21  1557.5 2419.67
#Mann= 5 ,-1,0
       0     .05       0   453.1    .045       0   501.6     .05       0
   732.4    .045       0   809.9     .05       0
Bank Sta=453.1,501.6
XS Rating Curve= 0 ,0
Exp/Cntr(USF)=0,0
Exp/Cntr=0.3,0.1

Type RM Length L Ch R = 1 ,95030   ,463.3,545.7,603.4
XS GIS Cut Line= 2
2279772.74315702445098.209340913 2278285.6779629 445919.28828245
#Sta/Elev= 30
       0 2457.42    32.6  2454.8    64.1 2449.64   146.9 2432.25   155.7 2432.17
   192.6 2425.89   246.9  2412.9   276.4 2412.62   293.1 2407.21   302.2 2405.91
   364.7 2405.49   376.5 2400.23     421 2398.44   439.3 2399.98   475.8  2399.7
     485 2401.06   530.7 2399.94   564.9 2402.98   599.2 2401.03   651.6 2402.58
   699.7 2401.38   791.5 2402.87   836.8 2401.16   941.7 2404.69  1194.8 2408.19
  1216.1 2409.76    1248 2417.89  1270.9 2421.09  1585.5  2429.4  1698.7 2438.75
#Mann= 6 ,-1,0
       0      .1       0     210     .08       0     320      .1       0
   376.5    .045       0   439.3     .05       0    1670     .04       0
Bank Sta=376.5,439.3
XS Rating Curve= 0 ,0
Exp/Cntr(USF)=0,0
Exp/Cntr=0.3,0.1

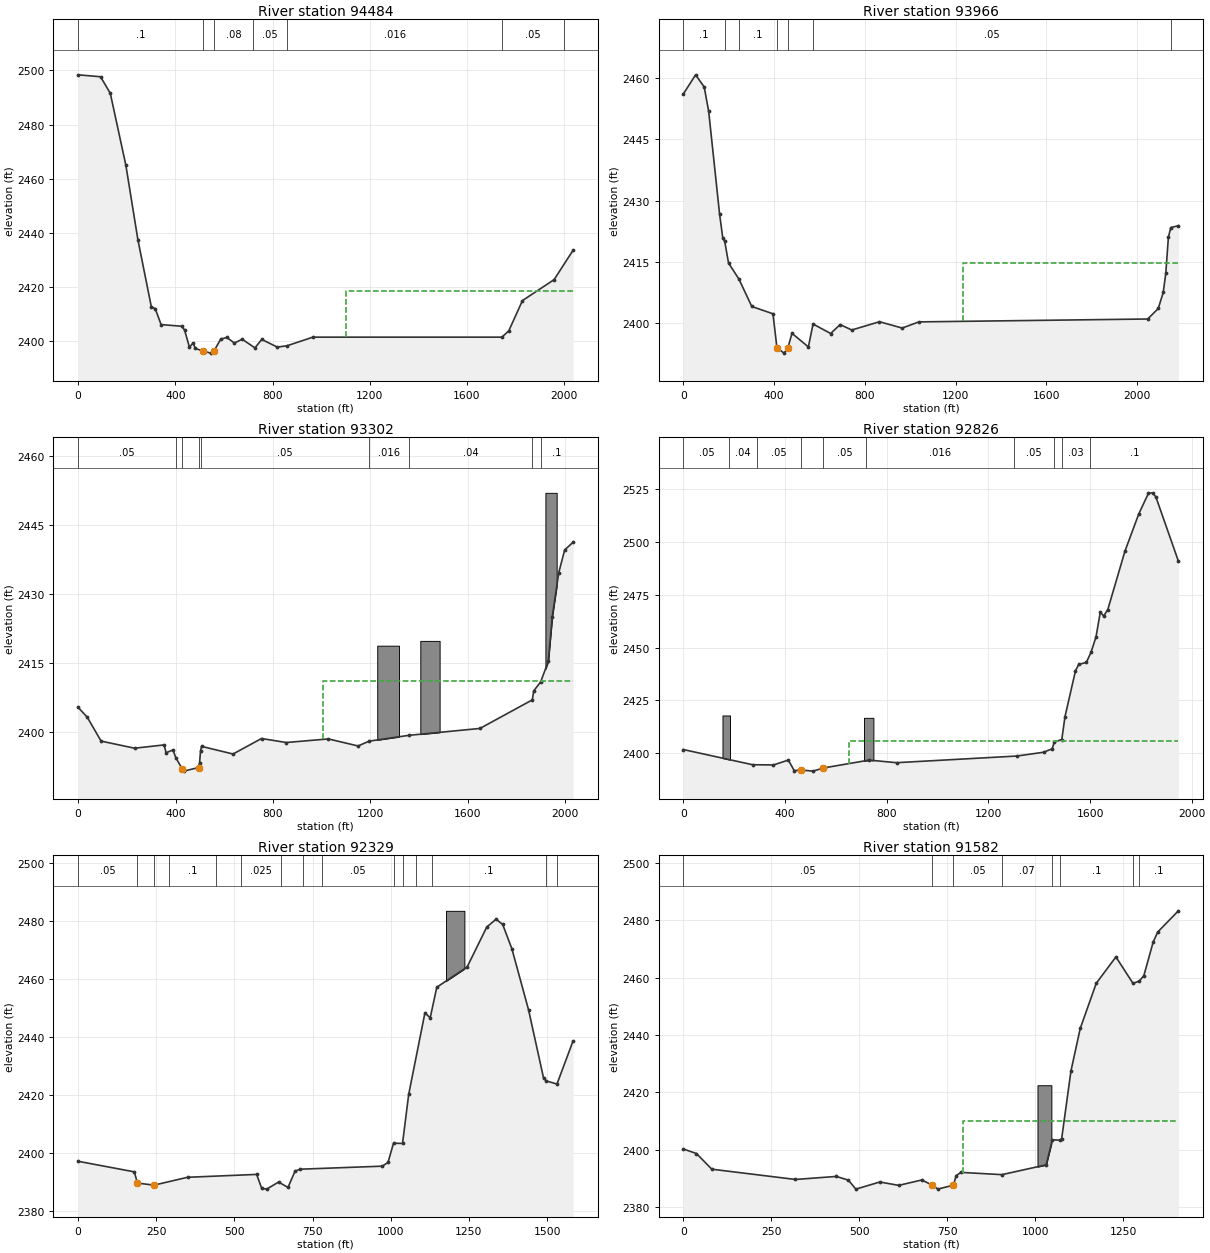
Type RM Length L Ch R = 1 ,94484   ,537.6,517.9,305.8
XS GIS Cut Line= 3
2279819.64063627 444780.74922644 2278893.1101792444877.615172912
2278113.38362852445660.801019947
#Sta/Elev= 30
       0 2498.39      92 2497.68   132.2 2491.59   196.5 2464.91   245.9 2437.46
   301.1 2412.76   317.2 2412.04   341.3 2406.17   425.8 2405.56   437.8 2404.19
   457.9 2397.83   473.3  2399.4   482.1 2397.38   512.72396.431   546.1 2395.63
   558.5 2396.36   586.6 2400.78   611.6 2401.43     643 2399.36   675.1 2400.76
   727.4 2397.58   755.6 2400.68   819.9 2397.85   860.1 2398.36   965.9 2401.53
  1743.8 2401.53    1772 2403.84  1828.5 2415.04  1958.7 2422.77  2036.7 2433.61
#Mann= 7 ,-1,0
       0      .1       0   512.7    .045       0   558.5     .08       0
     720     .05       0   860.1    .016       0  1743.8     .05       0
 1997.82     .03       0
#XS Ineff= 2 , 0
                         1101.55         2418.63
Permanent Ineff=
       F       F
Bank Sta=512.7,558.5
XS Rating Curve= 0 ,0
Exp/Cntr(USF)=0,0
Exp/Cntr=0.3,0.1

Type RM Length L Ch R = 1 ,93966   ,698.9,663.6,444.2
Node Name=AI
XS GIS Cut Line= 2
2279546.12395349444059.3454998272277858.24810038445441.320130822
#Sta/Elev= 30
       0 2456.23    53.4 2460.86    91.3 2457.88   111.1 2451.88     159 2426.76
   173.1  2420.9   181.8 2420.01   198.6  2414.7   244.3 2410.78   301.1 2404.05
   394.4 2402.26   411.9 2393.93   443.3 2392.61   460.3 2393.89   478.1 2397.47
   550.5 2394.14   571.2 2399.75   648.7 2397.42   690.6 2399.62   741.7 2398.28
   863.9 2400.31   964.1 2398.76  1037.3 2400.27  2046.4 2400.98  2092.8 2403.56
  2114.6 2407.48    2126 2412.17  2137.4 2421.02    2148  2423.4  2181.5 2423.86
#Mann= 7 ,-1,0
       0      .1       0   181.8     .05       0   244.3      .1       0
   411.9    .045       0   460.3      .1       0   571.2     .05       0
    2148    .016       0
#XS Ineff= 2 , 0
                         1230.64         2414.78
Permanent Ineff=
       F       F
Bank Sta=411.9,460.3
XS Rating Curve= 0 ,0
Exp/Cntr(USF)=0,0
Exp/Cntr=0.3,0.1

Type RM Length L Ch R = 1 ,93302   ,411.8,476.4,508.3
XS GIS Cut Line= 3
2278650.60193692443716.0597893252278541.12474472444459.592386384
 2277533.0222665445248.740480194
#Sta/Elev= 30
       0 2405.38    37.5 2403.24    94.1 2398.06   231.6 2396.51   352.9 2397.23
     361 2395.52   389.3 2396.14   401.5 2394.37   426.6 2392.09   433.7 2391.53
   494.4 2392.31   498.4 2393.28   502.5 2395.92   506.5 2396.91   635.9 2395.25
   752.8 2398.62   854.4 2397.75  1027.1 2398.53    1149    2397    1195 2398.05
  1357.6 2399.31  1649.6 2400.81  1864.6 2407.02  1870.3 2408.97  1898.8 2410.93
  1930.1 2415.38  1946.5 2425.13  1972.9 2434.63  1997.3  2439.6  2031.8 2441.28
#Mann= 9 ,-1,0
       0     .05       0   401.5      .1       0   426.6    .045       0
   494.4      .1       0   502.5     .05       0    1195    .016       0
  1357.6     .04       0  1864.6    .016       0  1898.8      .1       0
#XS Ineff= 2 , 0
                         1006.88         2411.17
Permanent Ineff=
       F       F
#Block Obstruct= 3 ,-1
 1227.82 1317.13  2418.8 1404.66 1483.96 2419.84 1918.26  1964.5 2452.02
Bank Sta=426.6,494.4
XS Rating Curve= 0 ,0
Exp/Cntr(USF)=0,0
Exp/Cntr=0.3,0.1

Type RM Length L Ch R = 1 ,92826   ,428.1,497,488.3
XS GIS Cut Line= 3
2278355.16010296443663.3358607462277807.77414193444653.192140266
2277032.31069715444908.638922077
#Sta/Elev= 30
       0  2401.6   271.8 2394.42   354.1 2394.31   412.7 2396.62     436 2391.58
     4612391.937   509.8 2391.38   550.82392.877   730.5 2396.61   838.6 2395.38
  1311.8 2398.54  1417.1 2400.34  1450.8 2401.97  1459.2 2405.16  1488.8 2406.38
  1501.4 2417.26  1542.6 2438.95  1555.3 2441.99  1585.5 2442.94  1604.1 2447.85
  1623.4 2455.01  1640.3 2466.79  1653.5 2464.95  1669.8 2468.01  1737.2 2495.67
  1791.9 2513.43  1829.8 2523.15  1846.7 2523.37  1859.3 2521.35  1947.6 2490.97
#Mann= 10 ,-1,0
       0     .05       0     180     .04       0     290     .05       0
     461    .045       0   550.8     .05       0     720    .016       0
 1301.13     .05       0  1459.2    .016       0  1488.8     .03       0
 1601.13      .1       0
#XS Ineff= 2 , 0
                          650.14         2405.53
Permanent Ineff=
       F       F
#Block Obstruct= 2 ,-1
  153.42  183.21 2417.78  710.32  747.39 2416.66
Bank Sta=461,550.8
XS Rating Curve= 0 ,0
Exp/Cntr(USF)=0,0
Exp/Cntr=0.3,0.1

Type RM Length L Ch R = 1 ,92329   ,406.8,747.1,637
XS GIS Cut Line= 3
2278016.54653207443533.5978023162277332.31408079444290.815048401
2276798.61276879444468.715485734
#Sta/Elev= 30
       0 2397.11   179.5 2393.47   189.7 2389.59   242.72388.875   349.9 2391.59
   570.9 2392.58   587.1 2387.78   603.1  2387.5     641 2389.95   671.2 2388.08
   693.8 2393.72   710.5 2394.38     973 2395.43   991.2 2396.73  1008.8 2403.37
  1037.6 2403.27  1057.3  2420.2  1109.3  2448.4  1126.1 2446.64  1147.2 2457.21
  1244.2 2464.19  1307.1    2478  1336.9  2480.7    1358 2478.87  1387.5 2470.45
  1440.8 2449.37  1488.7 2425.86  1496.9 2424.88  1531.7 2423.79  1583.1 2438.67
#Mann= 15 ,-1,0
       0     .05       0   189.7    .045       0   242.7     .05       0
     290      .1       0     440     .05       0     520    .025       0
     650     .05       0     720    .025       0     780     .05       0
  1008.8    .016       0  1037.6     .05       0 1080.56     .03       0
 1130.56      .1       0  1496.9    .016       0  1531.7      .1       0
#Block Obstruct= 1 ,-1
 1176.57 1235.43 2483.59
Bank Sta=189.7,242.7
XS Rating Curve= 0 ,0
Exp/Cntr(USF)=0,0
Exp/Cntr=0.3,0.1

Type RM Length L Ch R = 1 ,91582   ,357.1,535.6,448.6
XS GIS Cut Line= 5
2278041.80233993443302.1896004052277804.18279705443327.294453545
2277361.56831591443488.2923956342277297.01659506443488.292395634
2276723.01154705443754.062754098
#Sta/Elev= 30
       0  2400.2    36.9 2398.63    80.6 2393.17   318.4 2389.59   434.7 2390.65
   468.8 2389.35   490.1 2386.22   558.2 2388.71   611.8 2387.53   677.4 2389.41
   707.2 2387.63   723.3 2386.24   767.22387.578   775.4 2390.93   788.6 2392.06
   905.3 2391.27  1031.1 2394.69  1048.7 2403.41  1069.9  2403.3  1075.1 2403.76
  1101.6 2427.45    1128 2442.28  1173.5 2458.01  1229.4 2467.21  1277.9 2457.99
  1295.5 2458.76  1308.8 2460.67  1335.2 2472.33  1348.2 2475.88    1407 2483.28
#Mann= 8 ,-1,0
       0     .05       0   707.2    .045       0   767.2     .05       0
   905.3     .07       0  1048.7    .016       0  1069.9      .1       0
  1277.9    .016       0  1295.5      .1       0
#XS Ineff= 2 , 0
                          795.87         2409.85
Permanent Ineff=
       F       F
#Block Obstruct= 1 ,-1
 1006.39 1045.91 2422.45
Bank Sta=707.2,767.2
XS Rating Curve= 0 ,0
Exp/Cntr(USF)=0,0
Exp/Cntr=0.3,0.1