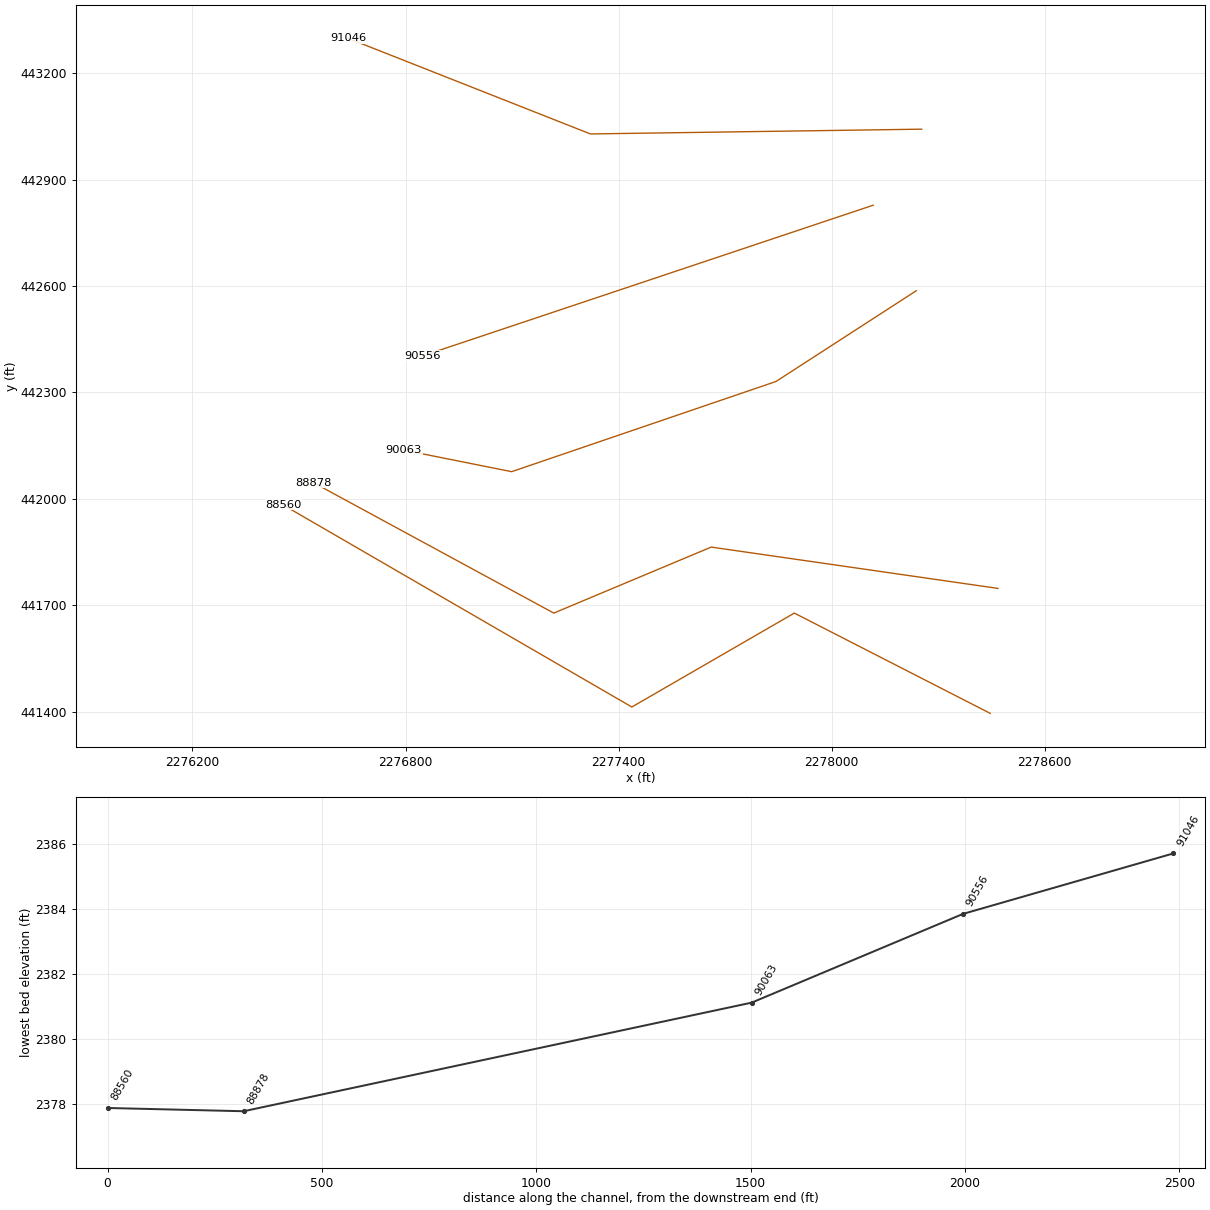
HEC-RAS study KNAPPCK.prj: KNAPPCK

--- KNAPPCK.g01 (geometry) --- (continued)

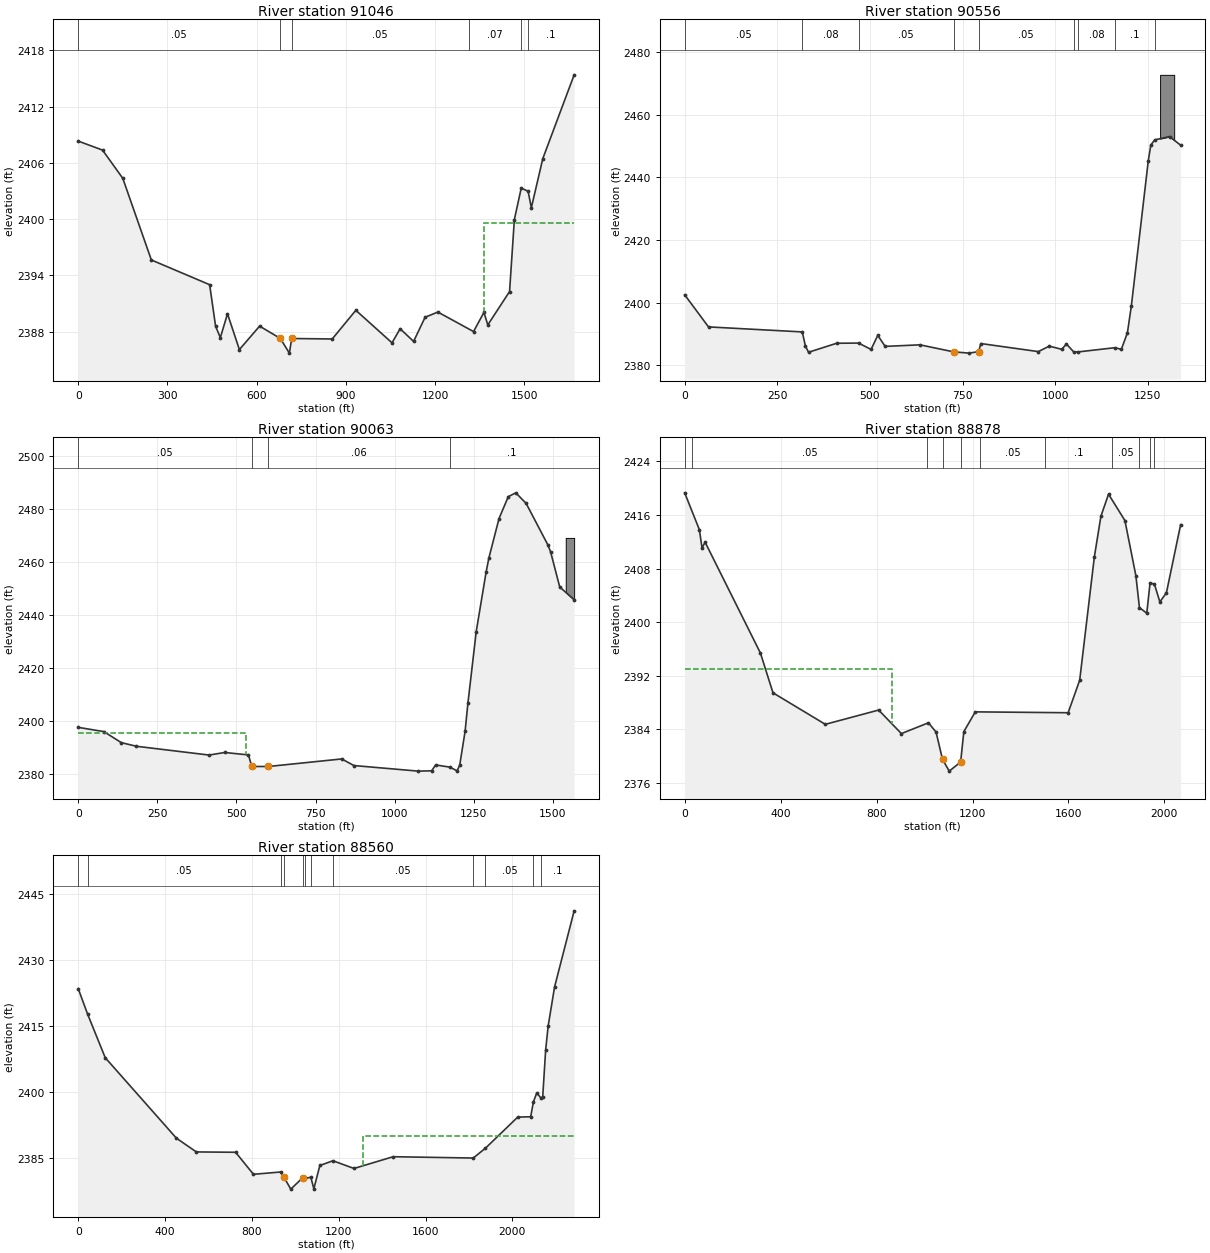
Type RM Length L Ch R = 1 ,91046   ,358.5,490.7,506.3
Node Name=AH
XS GIS Cut Line= 3
2278253.93755119443042.0094939842277320.76247772443028.550238116
2276638.19254368443298.003635818
#Sta/Elev= 30
       0 2408.33    81.8 2407.37   149.8 2404.36   245.8 2395.65   441.8 2393.01
   461.8 2388.58   477.8 2387.36   501.8 2389.91   541.8 2386.09   609.8 2388.59
  679.33 2387.28   709.8 2385.71   717.72387.271   853.9 2387.22   933.2 2390.28
  1054.8 2386.81  1082.2 2388.31  1127.4 2386.96  1166.1 2389.54  1209.1 2390.09
  1328.9 2388.01  1363.9 2390.06  1376.8 2388.72    1450 2392.28  1466.1 2399.96
  1489.2 2403.31  1512.3 2402.98  1523.2 2401.22  1561.8 2406.47  1667.1  2415.4
#Mann= 6 ,-1,0
       0     .05       0  679.33    .045       0   717.7     .05       0
 1313.27     .07       0  1489.2    .016       0  1512.3      .1       0
#XS Ineff= 2 , 0
                         1363.17          2399.6
Permanent Ineff=
       F       F
Bank Sta=679.33,717.7
XS Rating Curve= 0 ,0
Exp/Cntr(USF)=0,0
Exp/Cntr=0.3,0.1

Type RM Length L Ch R = 1 ,90556   ,406.8,493.2,416.9
XS GIS Cut Line= 2
2278117.18879353442827.7137749392276847.99629414442403.009824884
#Sta/Elev= 30
       0 2402.47    64.3 2392.22   317.4 2390.62   325.9 2386.08   334.3 2384.13
   410.2    2387   469.3 2387.06     503 2385.03   521.1 2389.52     541    2386
   634.9  2386.5   725.72384.257   767.6 2383.85   793.32384.332   799.2 2386.91
   954.3 2384.34   983.9 2386.08  1017.6 2385.07  1030.3 2386.77  1049.9 2384.23
  1062.6 2384.25    1161 2385.58  1178.5 2385.07  1194.8 2390.34  1205.5 2398.96
  1251.2 2445.32    1258 2450.27  1268.5 2451.93  1308.7 2452.97  1338.4 2450.23
#Mann= 9 ,-1,0
       0     .05       0   317.4     .08       0   469.3     .05       0
   725.7    .045       0   793.3     .05       0  1049.9    .045       0
  1062.6     .08       0    1161      .1       0  1268.5     .05       0
#Block Obstruct= 1 ,-1
 1283.02 1321.06 2472.69
Bank Sta=725.7,793.3
XS Rating Curve= 0 ,0
Exp/Cntr(USF)=0,0
Exp/Cntr=0.3,0.1

Type RM Length L Ch R = 1 ,90063   ,968.1,1185,412.8
XS GIS Cut Line= 4
2278238.53277926 442586.665587072277843.34493384442330.859346882
2277098.88318355442076.6928902852276795.52321923 442137.36488315
#Sta/Elev= 30
       0 2397.65    80.9 2396.06   136.2 2391.88   183.9 2390.51   413.5 2387.19
   462.7 2388.16   537.9 2387.24  548.27 2382.87   600.6 2382.87   832.5 2385.72
     871 2383.23  1074.3 2381.12  1116.6 2381.24  1129.2 2383.46  1174.1 2382.63
  1196.9 2381.23  1205.3  2383.4  1222.2 2396.12  1231.1 2406.69  1257.4 2433.81
  1288.7 2456.34  1297.5 2461.68  1329.5 2476.55  1358.7  2484.8  1382.5 2486.25
  1415.2 2482.24  1484.5 2466.42  1492.7 2463.83  1521.2 2450.69  1566.8 2445.84
#Mann= 4 ,-1,0
       0     .05       0  548.27    .045       0   600.6     .06       0
  1174.1      .1       0
#XS Ineff= 2 , 0
          530.93 2395.38
Permanent Ineff=
       F       F
#Block Obstruct= 1 ,-1
 1540.19 1566.78 2469.23
Bank Sta=548.27,600.6
XS Rating Curve= 0 ,0
Exp/Cntr(USF)=0,0
Exp/Cntr=0.3,0.1

Type RM Length L Ch R = 1 ,88878   ,310.5,317.5,322.4
Node Name=AG
XS GIS Cut Line= 4
2278468.60367079441747.6795515482277660.95637373441864.154112015
 2277217.5748494441678.1382327522276540.12563741442046.024559795
#Sta/Elev= 30
       0 2419.29    61.1 2413.81    72.3 2411.08    85.3 2411.92   315.7  2395.4
   368.2 2389.46   586.4 2384.76   808.7 2386.89   903.6 2383.38  1016.4 2384.99
  1048.1  2383.6    10752379.516  1103.1 2377.78  1150.52379.134  1163.9 2383.67
  1211.6 2386.62  1598.8 2386.49  1646.9 2391.34  1708.1 2409.74  1735.4  2415.8
  1767.2 2419.09  1835.5 2415.15  1881.2 2406.93    1896 2402.18  1926.6 2401.33
  1940.2 2405.84  1958.4 2405.68  1981.2 2403.02  2008.5 2404.38  2067.7 2414.54
#Mann= 11 ,-1,0
       0     .12       0      30     .05       0 1010.81      .1       0
    1075    .045       0  1150.5      .1       0 1230.81     .05       0
 1501.55      .1       0 1781.55     .05       0    1896     .04       0
  1940.2    .016       0  1958.4      .1       0
#XS Ineff= 2 , 0
          864.79 2393.07
Permanent Ineff=
       F       F
Bank Sta=1075,1150.5
XS Rating Curve= 0 ,0
Exp/Cntr(USF)=0,0
Exp/Cntr=0.3,0.1

Type RM Length L Ch R = 1 ,88560   ,446.7,382,157.5
XS GIS Cut Line= 4
2278446.85355196441395.4938595362277895.02406139441678.138232752
 2277437.4093619441413.4395340262276454.88368358 441983.21469908
#Sta/Elev= 30
       0 2423.48    43.5 2417.65   124.4 2407.77   452.4 2389.46   544.1 2386.34
     725 2386.26   807.2 2381.25   932.9 2381.78     9482380.576   979.1 2377.88
  1034.6 2380.49  1043.8 2380.36  1071.5 2380.56  1085.4 2377.97  1113.1 2383.26
  1173.2 2384.33  1270.3 2382.58  1450.8 2385.25  1819.6 2384.95    1876  2387.2
  2024.5 2394.26  2084.1 2394.34    2097 2397.78  2112.3 2399.75  2132.7 2398.52
  2139.6 2398.87  2153.2 2409.58  2164.9 2415.04  2194.2 2423.85  2284.4 2441.17
#Mann= 12 ,-1,0
       0     .12       0    43.5     .05       0   932.9      .1       0
     948    .045       0  1034.6      .1       0  1043.8     .05       0
  1071.5    .025       0  1173.2     .05       0  1819.6      .1       0
    1876     .05       0    2097    .016       0  2132.7      .1       0
#XS Ineff= 2 , 0
                          1311.9            2390
Permanent Ineff=
       F       F
Bank Sta=948,1034.6
XS Rating Curve= 0 ,0
Exp/Cntr(USF)=0,0
Exp/Cntr=0.3,0.1