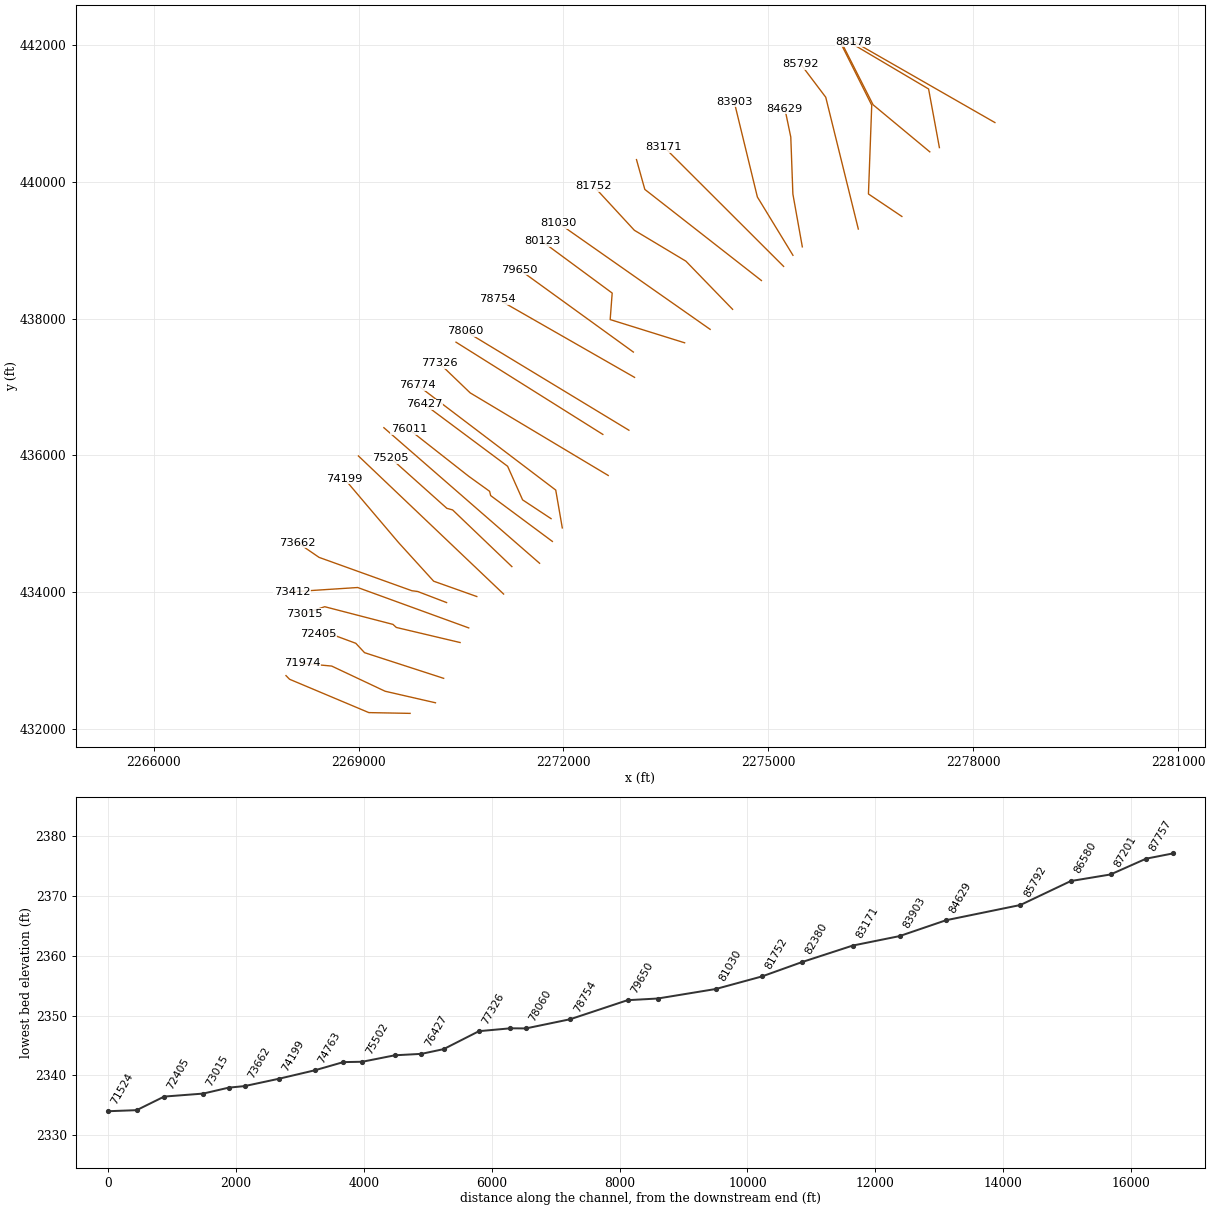
HEC-RAS study KNAPPCK.prj: KNAPPCK

--- KNAPPCK.g01 (geometry) --- (continued)

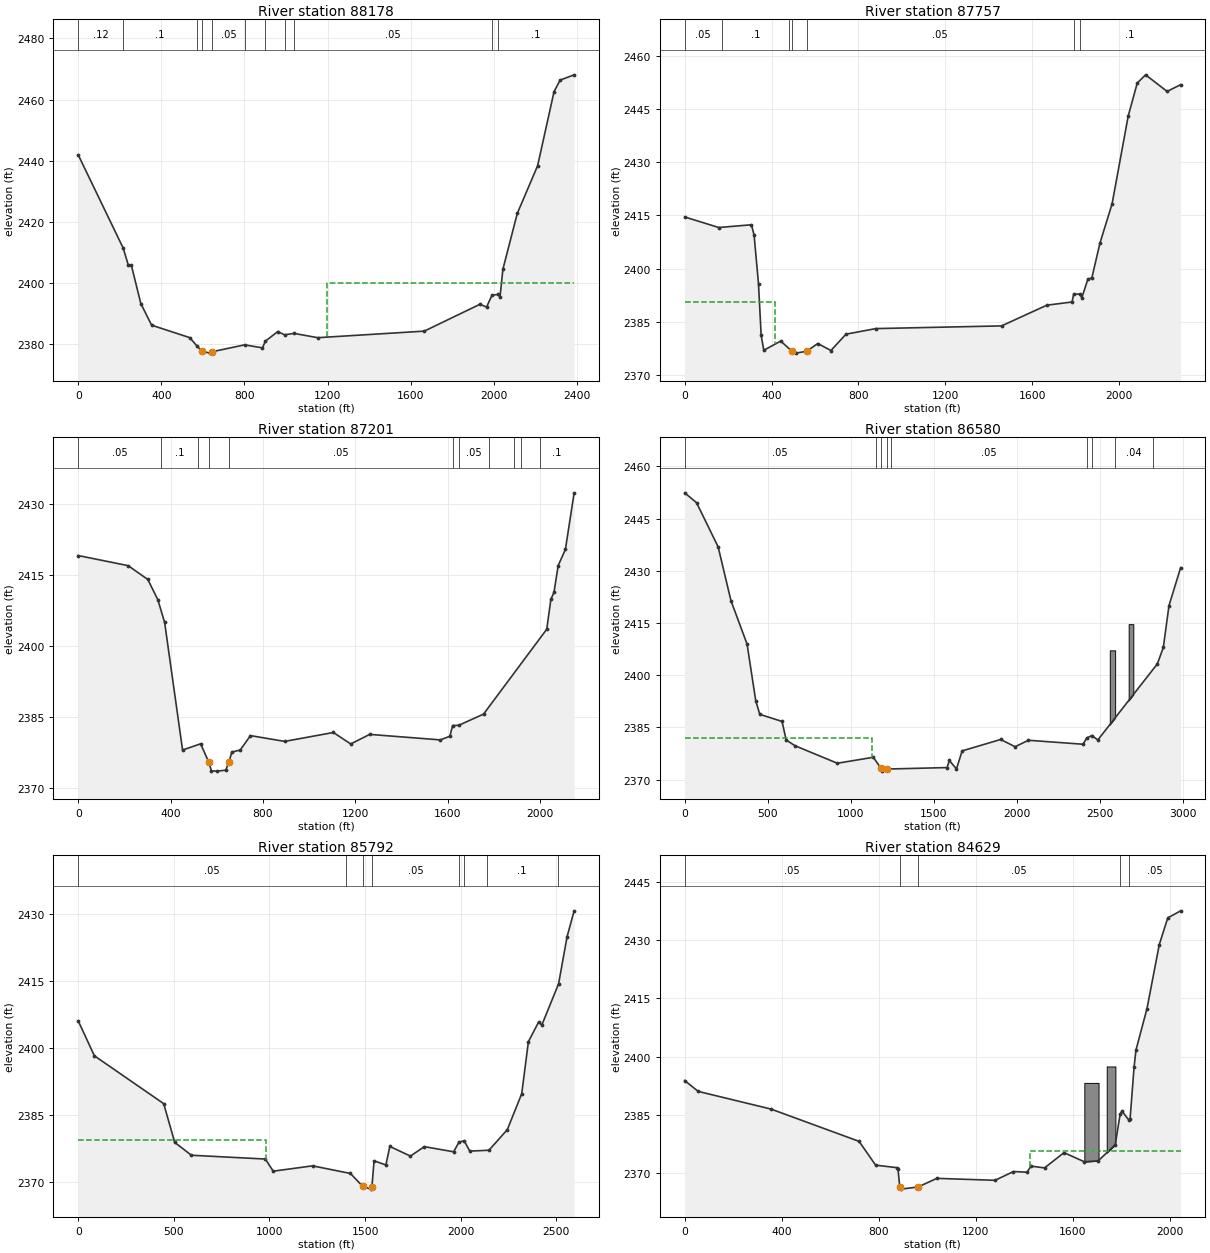
Type RM Length L Ch R = 1 ,88178   ,456.6,420.7,242.1
XS GIS Cut Line= 2
2278317.60881063440869.6527919952276246.66525809442055.655707549
#Sta/Elev= 30
       0  2441.9   216.4 2411.43   240.5    2406   255.7 2405.84   301.3 2393.29
   353.2 2386.23   536.4 2382.16   572.2 2379.37   594.7  2377.7   634.9 2377.09
     6452377.562   800.9 2379.79   886.7 2378.81   900.5    2381   960.4 2384.14
   992.7 2383.08  1038.8 2383.54  1152.6 2382.14  1665.2 2384.28    1933 2393.06
  1965.3 2392.16  1990.8 2396.01  2020.1 2396.29  2029.8 2395.41  2043.6 2404.51
  2112.8 2422.75  2210.7 2438.36  2289.8 2462.59  2319.1 2466.36  2386.5 2468.08
#Mann= 11 ,-1,0
       0     .12       0   216.4      .1       0   572.2     .05       0
   594.7    .045       0     645     .05       0   800.9      .1       0
   900.5     .05       0   992.7    .025       0  1038.8     .05       0
  1990.8    .016       0  2020.1      .1       0
#XS Ineff= 2 , 0
                          1199.5            2400
Permanent Ineff=
       F       F
Bank Sta=594.7,645
XS Rating Curve= 0 ,0
Exp/Cntr(USF)=0,0
Exp/Cntr=0.3,0.1

Type RM Length L Ch R = 1 ,87757   ,515.2,556.3,637.9
XS GIS Cut Line= 3
2277504.87707087440502.990425078 2277346.7071299441360.954022507
2276132.62651621442078.463455925
#Sta/Elev= 30
       0 2414.56     157 2411.59   307.3 2412.36   319.5 2409.43   339.8  2395.7
     352 2381.26   364.2 2377.01   442.1 2379.61   494.4  2376.7   511.3 2376.21
   562.3 2376.74   612.3 2378.92   673.3 2376.95   742.5 2381.55     880 2383.12
  1458.5 2383.88  1666.9 2389.71  1782.7 2390.61  1790.7 2392.82  1818.6 2392.84
  1827.9 2391.79  1855.6    2397  1874.3 2397.44  1911.5 2407.22  1967.2 2418.23
  2041.6 2443.02  2083.1 2452.27  2121.4 2454.59  2220.7 2449.91  2282.7 2451.82
#Mann= 7 ,-1,0
       0     .05       0     170      .1       0     480     .05       0
   494.4    .045       0   562.3     .05       0  1790.7    .016       0
  1818.6      .1       0
#XS Ineff= 2 , 0
          417.38 2390.52
Permanent Ineff=
       F       F
Bank Sta=494.4,562.3
XS Rating Curve= 0 ,0
Exp/Cntr(USF)=0,0
Exp/Cntr=0.3,0.1

Type RM Length L Ch R = 1 ,87201   ,640.1,621.4,440.6
XS GIS Cut Line= 3
2277364.24492851440440.8671225262276534.04288763441129.661123482
2276050.51862205442083.025005601
#Sta/Elev= 30
       0 2419.04   216.2 2416.91   301.4    2414     345  2409.7   374.3 2404.92
   451.9 2378.02   530.2 2379.33   565.6 2375.43   576.8 2373.63   602.5 2373.57
     639 2373.77   652.42375.496   665.4 2377.59   701.9 2378.03     746 2381.06
   894.1 2379.84  1105.1 2381.72  1180.1  2379.3  1262.1 2381.32  1567.8 2380.16
  1609.5 2380.92  1621.4 2383.19  1647.8 2383.23  1755.4  2385.6    2029  2403.5
  2046.9 2409.81  2060.4 2411.28  2078.4 2416.91  2109.8 2420.33  2147.7 2432.27
#Mann= 11 ,-1,0
       0     .05       0     360      .1       0     520     .05       0
   565.6    .045       0   652.4     .05       0  1621.4    .016       0
  1647.8     .05       0 1778.74     .04       0 1888.74     .05       0
 1918.74     .04       0 1998.74      .1       0
Bank Sta=565.6,652.4
XS Rating Curve= 0 ,0
Exp/Cntr(USF)=0,0
Exp/Cntr=0.3,0.1

Type RM Length L Ch R = 1 ,86580   ,432.5,787.4,579
Node Name=AF
XS GIS Cut Line= 4
2276955.33115207439495.3792335512276466.04830102439824.241477694
2276514.17448309441123.6483935752276024.89163205442102.214095659
#Sta/Elev= 30
       0 2452.38    71.3 2449.56   201.4 2436.85   278.5  2421.4   375.4 2408.94
   427.9 2392.59     452 2388.77   585.8 2386.74   610.5 2381.44   662.5 2379.79
   918.7 2374.73  1134.8 2376.45  1178.9 2373.44  1186.9 2372.47  1217.8 2373.07
  1579.1 2373.49  1592.2 2375.53  1635.2  2373.1  1669.4 2378.28  1901.4 2381.56
  1987.9 2379.48  2068.4 2381.33  2396.9 2380.19  2419.3 2382.01    2450 2382.69
  2485.8 2381.42  2844.1 2403.27  2879.9 2407.99  2913.9 2419.99  2983.9 2430.89
#Mann= 9 ,-1,0
       0     .05       0 1149.53     .03       0  1178.9    .045       0
  1217.8     .03       0 1239.53     .05       0  2419.3    .016       0
    2450     .05       0 2589.83     .04       0 2819.83      .1       0
#XS Ineff= 2 , 0
         1125.65 2381.86
Permanent Ineff=
       F       F
#Block Obstruct= 2 ,-1
 2557.66 2589.99 2407.15 2671.32  2699.3 2414.67
Bank Sta=1178.9,1217.8
XS Rating Curve= 0 ,0
Exp/Cntr(USF)=0,0
Exp/Cntr=0.3,0.1

Type RM Length L Ch R = 1 ,85792   ,876,1163.5,956
XS GIS Cut Line= 3
2276317.55174004439311.2905764542275840.91541448441240.005010125
2275475.12474602441724.031046162
#Sta/Elev= 30
       0 2406.07    84.4 2398.26   446.9 2387.57   504.6 2378.91   591.8 2376.04
   978.5 2375.19  1019.7 2372.48  1225.7 2373.67  1423.5 2371.97  1486.9 2369.13
  1530.6 2368.47  1535.7 2368.92  1547.1 2374.79  1608.9 2373.87  1629.5 2378.01
  1737.2 2375.85  1809.9 2377.96  1963.2 2376.81    1991 2378.95  2018.3 2379.27
  2047.7 2376.96    2148 2377.16  2243.9 2381.76  2319.1 2389.77  2354.2 2401.41
  2407.9 2405.82  2424.4 2405.13  2512.1 2414.35  2556.4 2424.86  2593.4 2430.64
#Mann= 8 ,-1,0
       0     .05       0    1400    .025       0  1486.9    .045       0
  1535.7     .05       0    1991    .016       0  2018.3     .05       0
 2136.74      .1       0 2506.74     .05       0
#XS Ineff= 2 , 0
          980.28 2379.35
Permanent Ineff=
       F       F
Bank Sta=1486.9,1535.7
XS Rating Curve= 0 ,0
Exp/Cntr(USF)=0,0
Exp/Cntr=0.3,0.1

Type RM Length L Ch R = 1 ,84629   ,620,726.1,636.9
XS GIS Cut Line= 4
 2275497.9458587439050.230668237 2275359.5428543439823.900937106
2275328.99598729440656.9973100912275242.22751293441073.055156981
#Sta/Elev= 30
       0 2393.85    55.8 2391.06   355.6 2386.52     719 2378.21   787.2 2372.09
   875.3 2371.44   879.3  2371.1     887 2366.35   891.3 2365.92   962.52366.483
  1039.4 2368.69  1279.6 2368.19  1355.6 2370.45  1411.7 2370.27  1427.5 2371.84
  1483.7 2371.38  1563.8 2375.31  1647.5 2372.96    1705  2373.2  1775.1 2377.36
  1795.5 2385.29  1803.7 2385.93  1830.1 2383.76  1836.4 2384.07  1852.7 2397.32
  1860.5 2401.68  1905.8 2412.31  1956.7 2428.84  1991.6 2435.69  2044.6 2437.51
#Mann= 5 ,-1,0
       0     .05       0     887    .045       0   962.5     .05       0
  1795.5    .016       0  1830.1     .05       0
#XS Ineff= 2 , 0
                         1425.09         2375.66
Permanent Ineff=
       F       F
#Block Obstruct= 2 ,-1
 1647.65  1706.3 2393.25 1739.92 1775.73 2397.48
Bank Sta=887,962.5
XS Rating Curve= 0 ,0
Exp/Cntr(USF)=0,0
Exp/Cntr=0.3,0.1

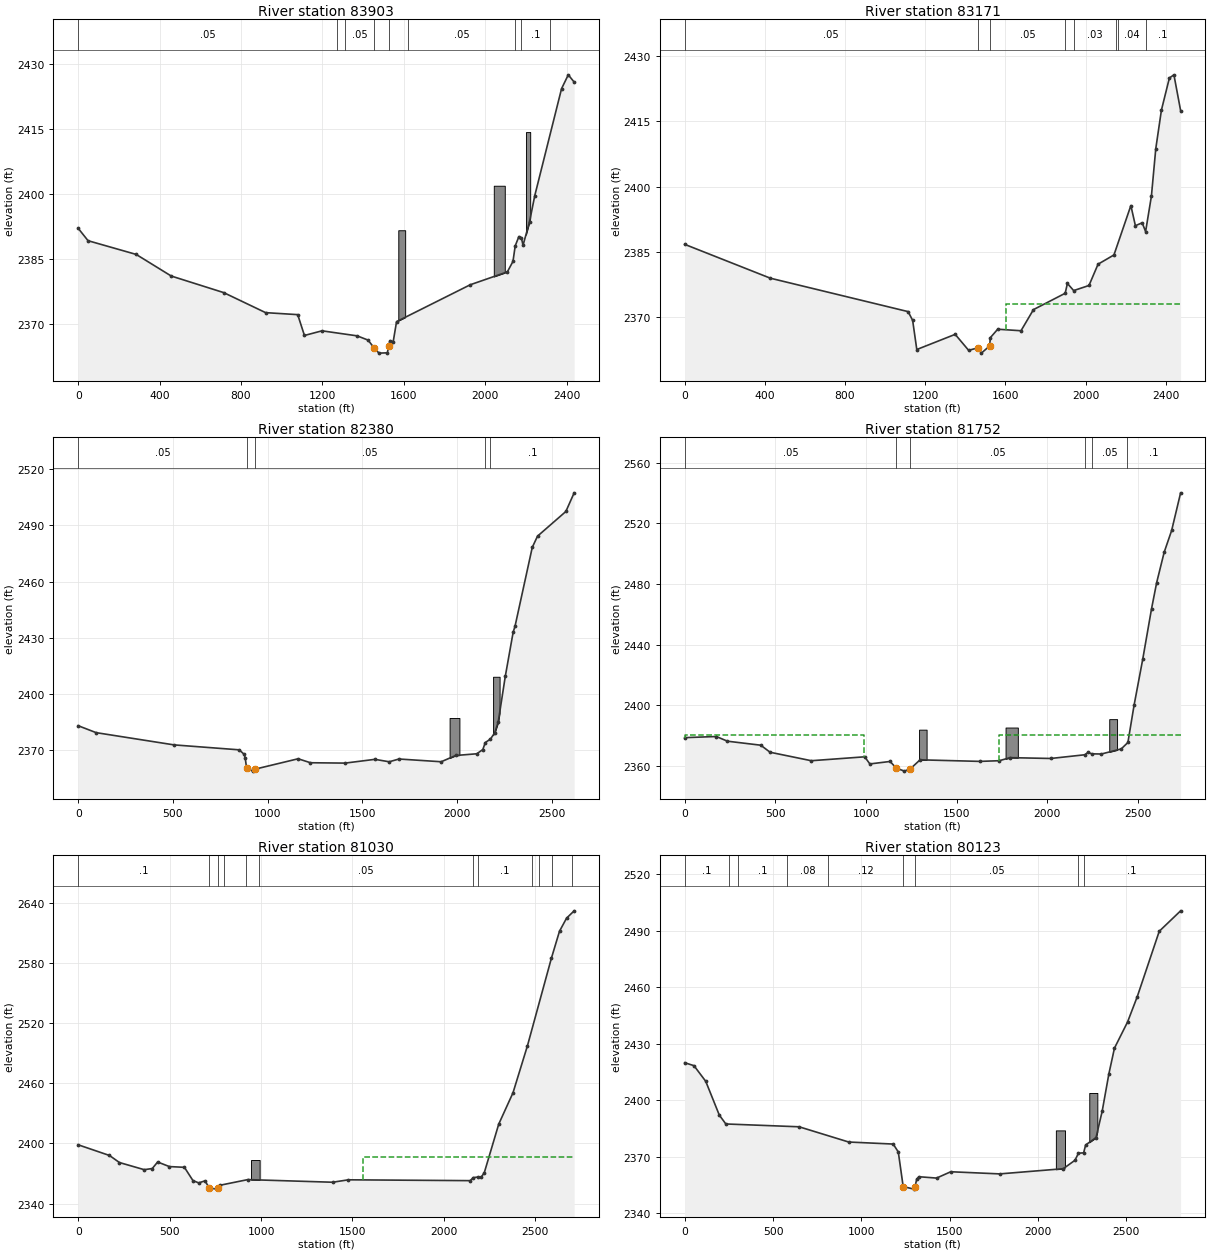
Type RM Length L Ch R = 1 ,83903   ,560.4,731.9,769.8
XS GIS Cut Line= 3
2275360.58423368438927.0256318152274839.60964527439780.537191543
2274499.68296348441177.192471098
#Sta/Elev= 30
       0 2392.03    48.4 2389.18   284.9 2386.02   457.1 2381.04   714.9 2377.22
     921  2372.6  1078.8 2372.14  1111.8 2367.34  1198.2 2368.41  1371.1 2367.25
  1424.6 2366.27  1453.22364.539  1478.2 2363.27  1519.3 2363.34  1526.82365.019
  1531.7 2366.14  1548.1 2365.91  1564.6 2370.53  1926.9 2379.03  2109.2    2382
  2136.8 2384.42  2147.7 2387.98  2165.7 2390.13    2178 2389.84  2186.2 2388.13
  2218.4  2393.6  2243.9 2399.58  2375.6 2424.23  2408.5 2427.41  2437.4 2425.74
#Mann= 9 ,-1,0
       0     .05       0 1269.95    .025       0 1309.95     .05       0
  1453.2    .045       0  1526.8     .04       0 1619.95     .05       0
  2147.7    .016       0    2178      .1       0 2319.95     .12       0
#Block Obstruct= 3 ,-1
 1573.06  1606.9 2391.59  2042.4 2096.43 2401.85 2200.47 2221.41 2414.21
Bank Sta=1453.2,1526.8
XS Rating Curve= 0 ,0
Exp/Cntr(USF)=0,0
Exp/Cntr=0.3,0.1

Type RM Length L Ch R = 1 ,83171   ,555.7,790.3,550.8
Node Name=AE
XS GIS Cut Line= 2
2275223.87458991 438764.452001392273472.51320761440512.118528453
#Sta/Elev= 30
       0 2386.72   427.4 2378.93  1114.7 2371.24  1137.3 2369.23    1158 2362.52
  1349.5 2366.01  1416.7 2362.33    1462  2362.9  1480.1 2361.69  1521.62363.344
  1524.8 2365.24  1561.6 2367.19  1677.9 2366.84    1740  2371.7  1898.3 2375.46
  1909.4 2377.72  1940.6 2376.08    2017 2377.25  2062.3 2382.15  2141.6 2384.28
    2226 2395.64  2248.6 2391.01  2282.5 2391.68  2299.5 2389.65  2328.5 2397.82
  2350.3 2408.74  2378.6 2417.64  2418.2    2425  2440.8 2425.72  2474.2 2417.49
#Mann= 8 ,-1,0
       0     .05       0    1462    .045       0  1521.6     .05       0
  1898.3    .016       0  1940.6     .03       0    2150      .1       0
    2160     .04       0    2300      .1       0
#XS Ineff= 2 , 0
                          1602.7         2373.09
Permanent Ineff=
       F       F
Bank Sta=1462,1521.6
XS Rating Curve= 0 ,0
Exp/Cntr(USF)=0,0
Exp/Cntr=0.3,0.1

Type RM Length L Ch R = 1 ,82380   ,535.9,628.9,509.1
XS GIS Cut Line= 3
2274898.72732907438557.5401081232273191.70420961 439891.38284865
2273069.77398679440327.375766607
#Sta/Elev= 30
       0 2383.15    94.6 2379.46   506.1 2372.93   850.5 2370.29   876.4 2367.88
   882.1 2365.84   889.4 2360.48   921.9 2358.94   933.82359.987  1161.4 2365.53
  1226.6 2363.41  1409.4 2363.22  1566.7 2365.22  1642.3 2363.93  1694.3  2365.4
    1917 2363.94  1993.5 2367.28  2104.8 2368.19  2136.8 2370.44  2149.8 2374.17
  2177.2 2376.05  2199.9 2379.44  2218.1 2385.11  2255.4 2409.47    2297 2433.03
    2307 2436.25  2397.9 2478.25  2425.7 2484.23  2575.3 2497.38  2619.1 2507.33
#Mann= 5 ,-1,0
       0     .05       0   889.4    .045       0   933.8     .05       0
  2149.8    .016       0  2177.2      .1       0
#Block Obstruct= 2 ,-1
 1961.28 2013.14 2387.28 2190.97 2225.36 2409.26
Bank Sta=889.4,933.8
XS Rating Curve= 0 ,0
Exp/Cntr(USF)=0,0
Exp/Cntr=0.3,0.1

Type RM Length L Ch R = 1 ,81752   ,657.4,721.9,590.7
XS GIS Cut Line= 4
 2274477.0694994438135.9992081082273793.32167309438840.847216984
2273037.98096158439293.4962463062272446.63549395439934.189393917
#Sta/Elev= 30
       0 2378.63   174.4 2379.38   235.7 2376.29   419.6 2373.64     471 2368.99
   698.2  2363.4   992.7 2365.98    1021 2361.28  1132.6 2362.91  1166.8  2358.5
  1211.8 2356.53    12452358.145    1298 2363.99  1626.9 2362.96  1734.1  2363.4
  1794.7 2365.43  2018.6 2364.88  2206.2 2367.33  2223.1 2368.83  2245.8 2367.94
  2297.6 2367.83  2407.1 2371.19  2443.9 2375.46  2477.9 2400.05  2525.8  2430.5
  2574.1 2463.67  2602.4 2480.94  2643.7 2500.95    2685 2515.37  2734.5 2540.23
#Mann= 6 ,-1,0
       0     .05       0  1166.8    .045       0    1245     .05       0
  2206.2    .016       0  2245.8     .05       0    2440      .1       0
#XS Ineff= 2 , 0
          990.42 2380.15 1734.94         2380.52
Permanent Ineff=
       F       F
#Block Obstruct= 3 ,-1
 1292.33 1333.87 2383.91  1769.2 1836.91 2385.31 2340.93 2384.11 2390.84
Bank Sta=1166.8,1245
XS Rating Curve= 0 ,0
Exp/Cntr(USF)=0,0
Exp/Cntr=0.3,0.1

Type RM Length L Ch R = 1 ,81030   ,949.3,906.7,503.1
Node Name=AD
XS GIS Cut Line= 2
2274147.97053133437843.0469824912271926.14512578439399.126869411
#Sta/Elev= 30
       0 2398.67   171.1 2388.02   225.4 2380.98   361.1 2373.84   405.1    2375
   434.4  2381.5   498.8 2376.94   580.9  2376.2   627.5 2362.97   659.1 2360.66
   693.5 2362.69   717.42355.407   761.6 2354.43   765.3 2355.33   776.8 2358.35
   927.6 2363.94  1391.5 2361.31  1477.6 2363.73  2143.9  2362.9  2161.1 2365.92
  2184.1 2366.45  2204.2 2366.35  2221.1 2370.91  2299.9 2419.29    2378 2450.59
    2457 2497.51    2588  2584.9  2632.4  2611.9    2671 2624.91  2712.5 2632.24
#Mann= 12 ,-1,0
       0      .1       0   717.4    .045       0   765.3      .1       0
     800     .05       0     920     .03       0     990     .05       0
  2161.1    .016       0  2184.1      .1       0    2480     .12       0
    2520      .1       0    2590     .12       0    2700      .1       0
#XS Ineff= 2 , 0
                         1559.38         2386.49
Permanent Ineff=
       F       F
#Block Obstruct= 1 ,-1
  945.16  992.33 2383.49
Bank Sta=717.4,765.3
XS Rating Curve= 0 ,0
Exp/Cntr(USF)=0,0
Exp/Cntr=0.3,0.1

Type RM Length L Ch R = 1 ,80123   ,281.2,473.4,585.1
XS GIS Cut Line= 4
2273774.48756914437646.0914965452272684.50527425437986.018178342
2272714.06411614438373.9779782182271686.89436028439131.423301786
#Sta/Elev= 30
       0 2419.91    52.7 2418.33   119.3 2410.02   195.9 2392.13   232.9 2387.41
   647.7 2385.91   928.4 2377.83  1180.3 2376.75  1209.1 2372.55  1236.7 2354.23
  1297.2 2352.84  1303.22353.995  1313.4 2358.08  1325.4 2359.42  1425.7  2358.7
    1506 2362.06  1783.4 2360.92  2142.8 2363.67  2209.1 2368.15    2229 2371.91
  2258.2 2372.09  2269.6 2376.28  2328.4 2380.18  2363.2 2394.21  2401.2 2414.07
  2432.6 2427.63  2506.8 2441.51    2562 2455.02  2686.2 2489.65  2807.1 2500.48
#Mann= 9 ,-1,0
       0      .1       0     250     .12       0     300      .1       0
     580     .08       0     810     .12       0  1236.7    .045       0
  1303.2     .05       0    2229    .016       0  2258.2      .1       0
#Block Obstruct= 2 ,-1
 2100.95 2152.93    2384 2290.03 2335.79 2403.86
Bank Sta=1236.7,1303.2
XS Rating Curve= 0 ,0
Exp/Cntr(USF)=0,0
Exp/Cntr=0.3,0.1

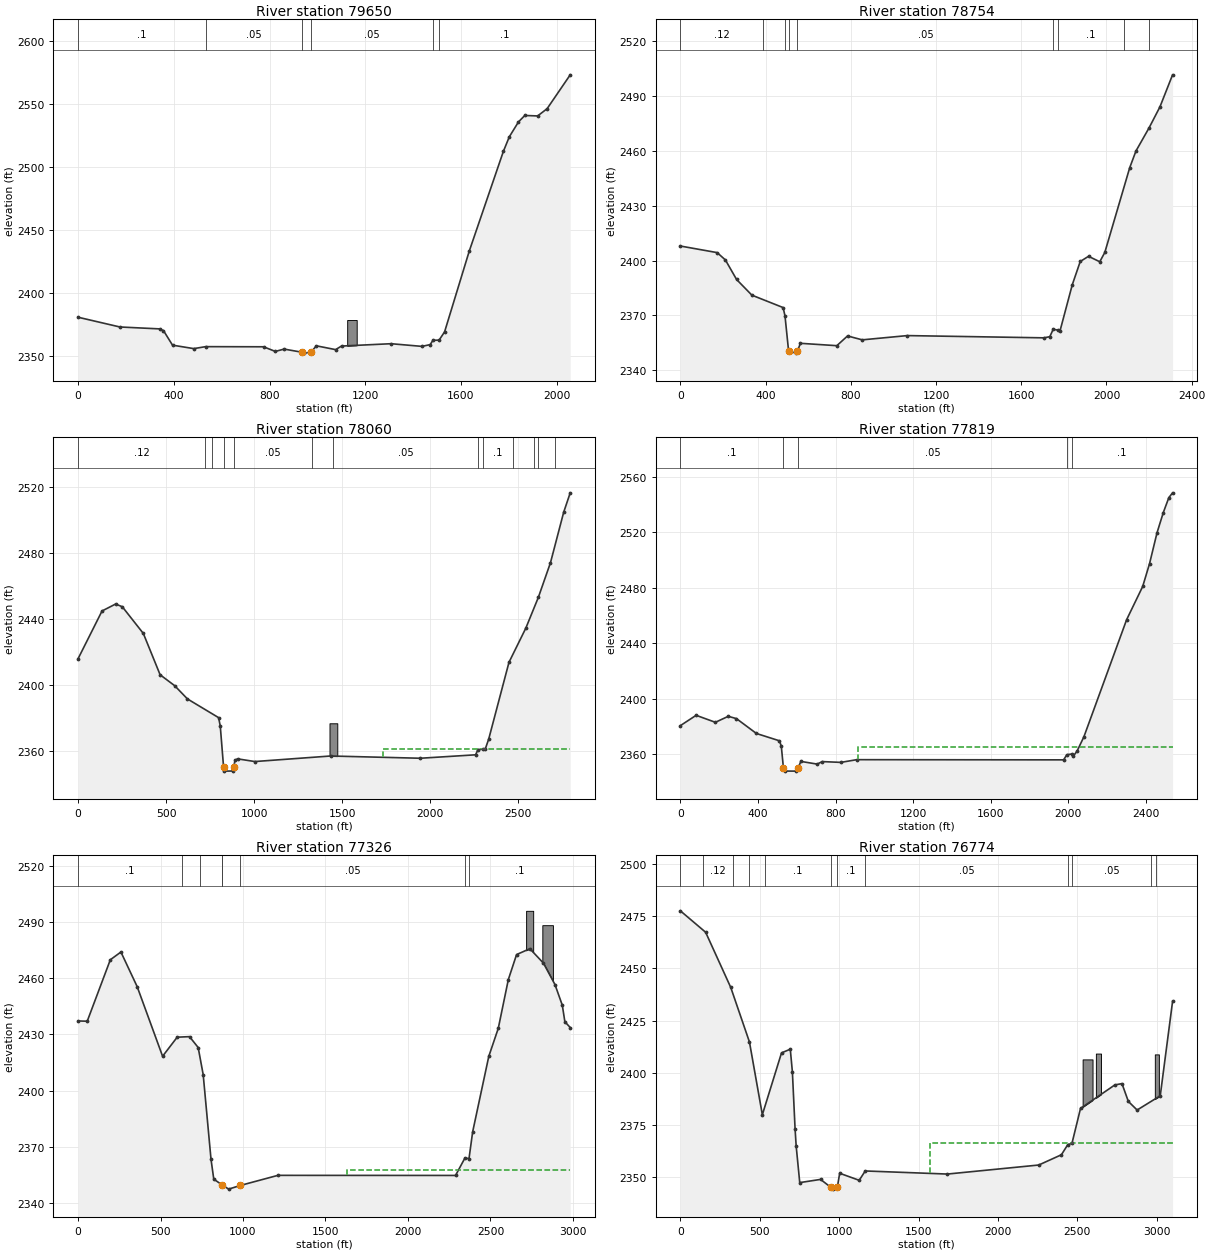
Type RM Length L Ch R = 1 ,79650   ,529.2,895.3,672.5
XS GIS Cut Line= 2
2273024.09602203437510.6700081182271357.90327606438715.882761036
#Sta/Elev= 30
       0 2381.04   174.9  2373.3   340.5 2371.79     357 2370.43   394.8 2358.88
   483.7 2356.14   533.1  2357.7     775 2357.59   824.3 2353.92   861.1 2355.76
  936.98 2353.23   942.8 2352.56   972.8 2353.22   995.8 2358.36  1076.1 2355.34
  1100.8 2358.17    1308 2360.03  1436.9 2357.91  1471.3 2359.32  1482.8 2362.74
  1508.5 2362.87  1531.5 2369.43  1634.6 2433.51  1777.1 2512.59  1801.8 2524.12
  1840.2 2535.97  1866.6 2541.08  1920.3 2540.71  1959.8 2546.45  2056.4 2573.32
#Mann= 6 ,-1,0
       0      .1       0   533.1     .05       0  936.98    .045       0
   972.8     .05       0  1482.8    .016       0  1508.5      .1       0
#Block Obstruct= 1 ,-1
 1124.56 1164.33 2378.83
Bank Sta=936.98,972.8
XS Rating Curve= 0 ,0
Exp/Cntr(USF)=0,0
Exp/Cntr=0.3,0.1

Type RM Length L Ch R = 1 ,78754   ,696.4,694.5,703.2
Node Name=AC
XS GIS Cut Line= 2
2273041.25447171437140.2598475012271035.99688547438287.267186829
#Sta/Elev= 30
       0 2407.94   172.7 2404.34   211.3 2400.33   263.9 2389.64   335.6 2381.08
   482.2 2374.29     491 2369.79   507.9  2350.6   541.6 2349.38   549.5 2350.45
   563.4 2354.75   734.3 2353.45   784.6 2358.77   853.7 2356.64  1065.3 2358.97
  1706.3 2357.74  1733.9 2358.37    1750 2362.45  1770.8 2361.98  1782.3 2361.75
  1839.4 2386.76  1876.8 2399.49  1915.7 2402.32  1968.4 2399.34    1992 2404.41
  2109.1 2450.81  2138.4 2459.93    2200 2472.59  2250.7    2484  2310.1 2501.55
#Mann= 9 ,-1,0
       0     .12       0     390      .1       0     490     .05       0
   507.9    .045       0   549.5     .05       0    1750    .016       0
  1770.8      .1       0    2080     .12       0    2200      .1       0
Bank Sta=507.9,549.5
XS Rating Curve= 0 ,0
Exp/Cntr(USF)=0,0
Exp/Cntr=0.3,0.1

Type RM Length L Ch R = 1 ,78060   ,242.2,241.1,239.8
XS GIS Cut Line= 2
2272958.92832968436366.490952631 2270568.3569914437814.874205502
#Sta/Elev= 30
       0 2415.85   136.4 2444.82   213.6 2449.03   251.5 2447.37   370.9  2431.2
   466.2 2406.18   548.6  2399.6   621.4 2391.56   798.3 2380.23   807.8 2375.13
   826.4  2350.5   831.1 2347.84   877.7 2347.91  884.15 2350.48   891.8 2354.46
   905.9 2355.28  1004.1 2353.64  1434.3    2357  1944.1 2355.64  2257.5 2357.72
  2271.5 2360.86  2297.8 2361.12  2313.5  2361.5  2332.3 2367.28  2447.4 2413.76
  2542.8 2434.38  2614.3 2453.11  2683.1 2474.09  2757.9 2504.58  2795.1 2516.36
#Mann= 13 ,-1,0
       0     .12       0     720      .1       0     760     .12       0
   826.4    .045       0  884.15     .05       0    1330     .04       0
    1450     .05       0  2271.5    .016       0  2297.8      .1       0
    2470     .12       0    2590      .1       0    2610     .12       0
    2710      .1       0
#XS Ineff= 2 , 0
                         1730.21         2361.21
Permanent Ineff=
       F       F
#Block Obstruct= 1 ,-1
 1428.02 1472.32 2376.81
Bank Sta=826.4,884.15
XS Rating Curve= 0 ,0
Exp/Cntr(USF)=0,0
Exp/Cntr=0.3,0.1

Type RM Length L Ch R = 1 ,77819   ,492.2,492.6,490
XS GIS Cut Line= 2
2272577.00096853436305.4572551992270427.61232623437655.073379435
#Sta/Elev= 30
       0 2380.63    81.3 2388.07   180.5 2383.03     247 2387.34   289.1 2385.69
   392.1 2374.98   511.1 2369.69   520.5 2365.78   531.3 2350.29   541.1 2347.91
   593.7 2347.86   606.8 2350.06   621.3 2354.86   705.4 2352.92   731.5 2354.73
   827.5 2354.16   909.6 2356.11  1976.2 2355.98  1992.8 2359.68  2017.8 2360.18
  2025.6 2358.52  2045.9 2362.39  2080.7 2372.56  2301.2 2456.99    2384  2480.9
  2419.2 2497.29  2457.9 2519.59  2490.1 2534.08  2518.8 2544.88    2538 2548.34
#Mann= 5 ,-1,0
       0      .1       0   531.3    .045       0   606.8     .05       0
  1992.8    .016       0  2017.8      .1       0
#XS Ineff= 2 , 0
                          914.64          2365.3
Permanent Ineff=
       F       F
Bank Sta=531.3,606.8
XS Rating Curve= 0 ,0
Exp/Cntr(USF)=0,0
Exp/Cntr=0.3,0.1

Type RM Length L Ch R = 1 ,77326   ,550.1,552.1,525.5
XS GIS Cut Line= 3
2272656.05888717435704.4954157552270634.86438566436913.329527695
2270181.53455779437348.341316521
#Sta/Elev= 30
       0 2437.23    55.8 2437.09   195.8 2469.93     260 2474.06   358.7 2455.52
   512.6 2418.37   601.1 2428.56   675.7 2428.85   728.3 2423.04   758.7 2408.55
   806.2 2363.22   822.9 2352.69   871.22349.782   913.1 2347.38   983.2 2349.33
  1211.7 2354.74  2288.3 2354.69  2345.3 2364.02  2369.9 2363.67  2392.1 2378.02
  2489.9 2418.35  2547.3 2433.27  2608.3 2459.35  2658.2 2472.69  2738.8 2475.84
  2820.9 2468.13    2891 2456.67  2935.4 2445.65    2951  2436.8  2983.4 2433.73
#Mann= 8 ,-1,0
       0      .1       0     630     .12       0     740      .1       0
     870     .05       0   871.2    .045       0   983.2     .05       0
  2345.3    .016       0  2369.9      .1       0
#XS Ineff= 2 , 0
                         1628.22          2357.4
Permanent Ineff=
       F       F
#Block Obstruct= 2 ,-1
 2716.07 2758.96 2496.07 2814.34 2878.54  2488.4
Bank Sta=871.2,983.2
XS Rating Curve= 0 ,0
Exp/Cntr(USF)=0,0
Exp/Cntr=0.3,0.1

Type RM Length L Ch R = 1 ,76774   ,379.6,346.6,254.1
XS GIS Cut Line= 3
2271983.48654714434936.5819759432271887.42031098435490.810261481
2269866.33449638437024.175184802
#Sta/Elev= 30
       0 2477.51   159.1 2467.26   317.3 2440.85     435 2414.77   516.2 2379.97
   636.9 2409.55   692.1 2411.32   705.4 2400.48   722.2 2373.35   729.2 2364.97
   751.7  2347.5   882.9 2349.03   948.62345.178   958.2 2344.38   988.3 2345.26
  1003.2 2351.97  1126.1  2348.6  1164.1 2353.07  1681.2 2351.59  2256.6 2355.91
  2399.4 2360.82  2439.6 2365.67  2465.8 2366.24  2519.7 2382.97  2736.2 2394.24
  2780.8 2394.85    2821 2386.33  2876.2 2382.22  3021.8 2389.04  3099.4 2434.15
#Mann= 12 ,-1,0
       0      .1       0     140     .12       0     330      .1       0
     430     .12       0     530      .1       0   948.6    .045       0
   988.3      .1       0 1162.49     .05       0  2439.6    .016       0
  2465.8     .05       0 2962.49     .03       0 2992.49     .05       0
#XS Ineff= 2 , 0
                         1572.29         2366.63
Permanent Ineff=
       F       F
#Block Obstruct= 3 ,-1
 2533.03 2595.41 2406.44 2616.46 2648.76 2409.23 2987.63  3013.1 2408.83
Bank Sta=948.6,988.3
XS Rating Curve= 0 ,0
Exp/Cntr(USF)=0,0
Exp/Cntr=0.3,0.1

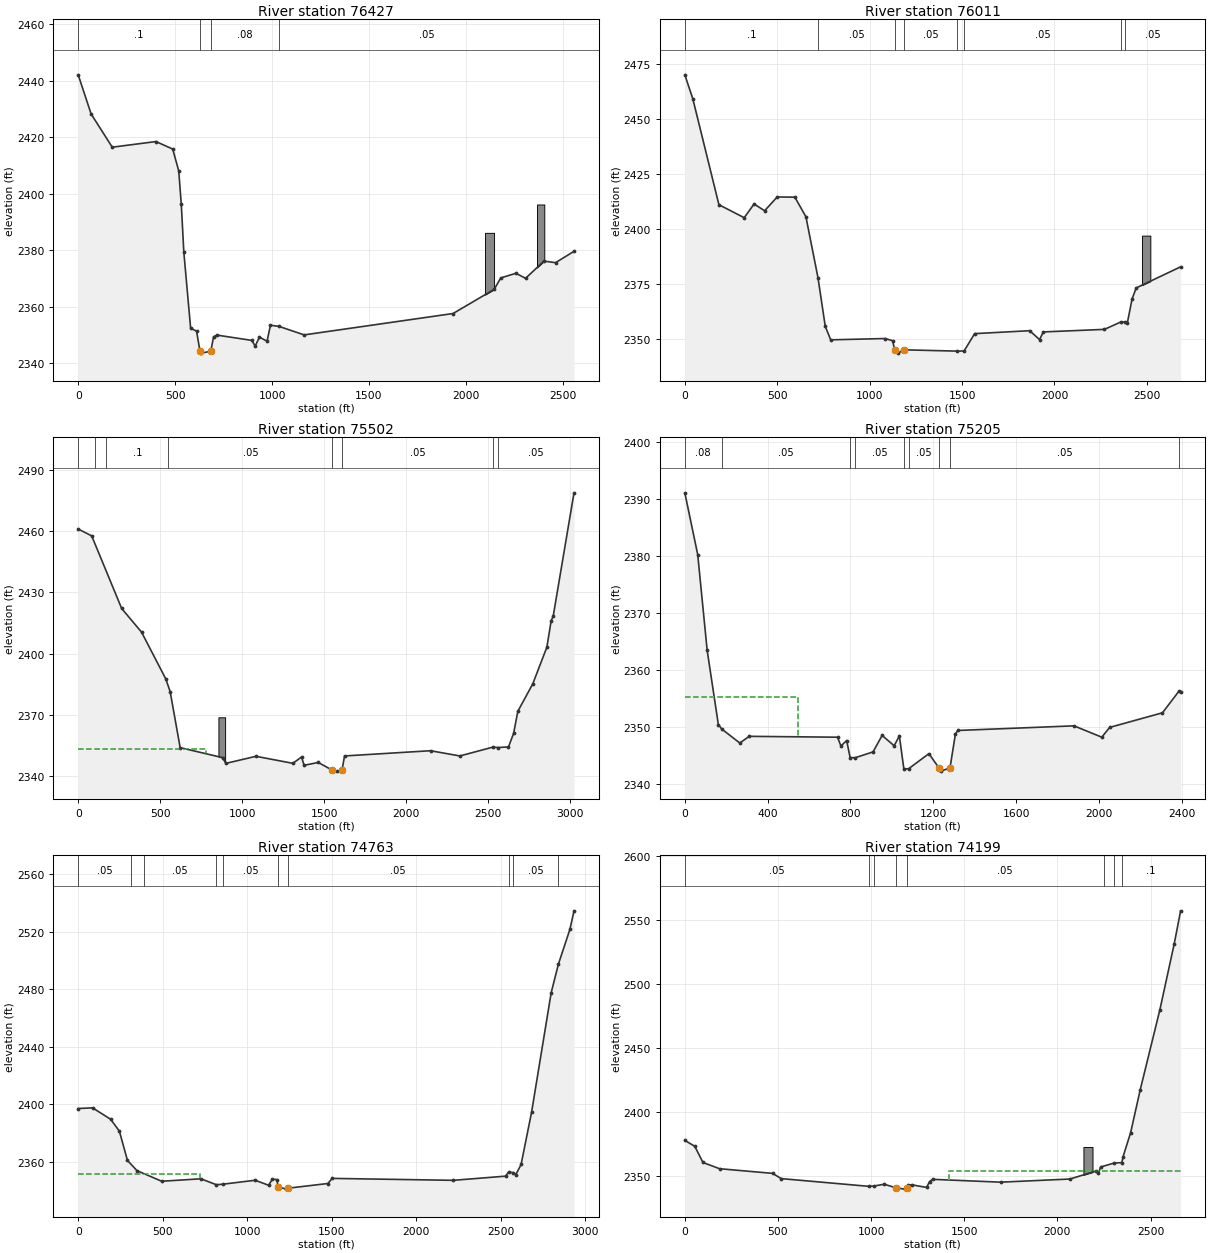
Type RM Length L Ch R = 1 ,76427   ,290.3,416.6,549.6
Node Name=AB
XS GIS Cut Line= 4
2271818.88326911435072.4746231812271402.33508262435347.396426266
2271182.95303774435838.9232863282269963.85534527436746.998332881
#Sta/Elev= 30
       0 2442.03    66.6 2428.18   175.7 2416.43     401 2418.43   487.5 2415.77
   518.6 2408.02   531.7 2396.27   544.8 2379.29   579.9 2352.41   610.6 2351.36
   628.1 2344.27   632.5 2343.59   683.8 2344.23   698.2 2349.35   715.7 2349.97
   895.8 2348.09   912.8 2346.06   934.7 2349.25   974.1 2347.81   991.6 2353.44
  1035.1 2353.06  1165.5 2350.04  1933.6  2357.6    2146 2366.16  2179.5 2370.19
  2257.8 2371.83  2307.7 2370.06  2402.5 2376.15  2462.3 2375.58  2557.5  2379.6
#Mann= 4 ,-1,0
       0      .1       0   628.1    .045       0   683.8     .08       0
  1035.1     .05       0
#Block Obstruct= 2 ,-1
 2098.41 2145.14 2386.14 2366.59 2404.22 2396.17
Bank Sta=628.1,683.8
XS Rating Curve= 0 ,0
Exp/Cntr(USF)=0,0
Exp/Cntr=0.3,0.1

Type RM Length L Ch R = 1 ,76011   ,305.4,509,314.7
XS GIS Cut Line= 5
2271838.32218448434739.2360739872270934.53054223435409.852078991
2270919.28368397435472.7453692962270615.37420307435691.003553081
2269735.87436211436381.557136648
#Sta/Elev= 30
       0 2469.88      43 2459.08   184.5 2410.82   321.4 2404.92   374.6 2411.16
   431.8 2408.08     500 2414.36   595.4 2414.25   655.2 2405.35   720.6 2377.58
   759.8 2355.56   789.2 2349.39  1083.7 2349.99  1124.3 2348.99  1135.4 2344.91
  1153.3 2343.35  1186.5 2344.85  1470.7 2344.27  1510.8 2344.31  1568.1 2352.21
  1865.8 2353.55  1919.3 2349.49  1939.6 2352.99  2270.2 2354.15  2360.1 2357.54
    2380 2357.49  2394.3 2357.07  2419.9 2368.02  2442.2 2372.99  2682.5 2382.59
#Mann= 8 ,-1,0
       0      .1       0   720.6     .05       0  1135.4    .045       0
  1186.5     .05       0  1470.7    .045       0  1510.8     .05       0
  2360.1    .016       0    2380     .05       0
#Block Obstruct= 1 ,-1
 2473.67 2518.66 2396.78
Bank Sta=1135.4,1186.5
XS Rating Curve= 0 ,0
Exp/Cntr(USF)=0,0
Exp/Cntr=0.3,0.1

Type RM Length L Ch R = 1 ,75502   ,271.9,296.3,308.9
XS GIS Cut Line= 2
2271650.94957581434419.3022427752269371.22389463   436403.439505
#Sta/Elev= 30
       0 2461.15    82.1  2457.8   264.8 2422.16   386.1 2410.51   533.5  2387.6
   560.5 2381.33   621.4 2353.81   880.2 2348.89   899.9 2346.07  1083.5 2349.55
  1308.2  2346.1  1361.2 2349.19  1377.1 2345.13  1463.4 2346.53  1549.12342.711
  1574.8 2342.27    1608 2342.67  1623.5 2349.72  2147.5 2352.29  2326.3 2349.72
  2527.8 2354.06  2559.6 2353.85  2622.8 2354.17  2654.2 2360.85  2679.7 2371.64
  2770.5 2385.08  2856.6 2403.09  2883.1 2416.14  2895.2 2418.29  3022.2 2478.93
#Mann= 8 ,-1,0
       0      .1       0     100     .12       0     170      .1       0
     550     .05       0  1549.1    .045       0    1608     .05       0
  2527.8    .016       0  2559.6     .05       0
#XS Ineff= 2 , 0
          781.58 2353.22
Permanent Ineff=
       F       F
#Block Obstruct= 1 ,-1
  854.63  895.56 2368.71
Bank Sta=1549.1,1608
XS Rating Curve= 0 ,0
Exp/Cntr(USF)=0,0
Exp/Cntr=0.3,0.1

Type RM Length L Ch R = 1 ,75205   ,379.2,442.4,339.7
XS GIS Cut Line= 4
2271245.19506105434370.6291115372270376.94202112435200.643027942
2270293.71569346435223.1366300132269468.20049747435960.926777928
#Sta/Elev= 30
       0 2391.01    62.3 2380.18   107.9 2363.41   161.9 2350.38   178.5 2349.59
   265.6 2347.14   310.9 2348.31   737.4 2348.16     754 2346.62   781.7 2347.58
   798.3 2344.59     823 2344.56   908.9 2345.58     953 2348.47  1010.9 2346.66
  1036.2 2348.38  1057.8 2342.62  1080.4 2342.62  1178.8 2345.27  1228.3 2342.73
  1235.1 2342.21  1280.6 2342.75  1306.9 2348.73  1318.2 2349.34  1879.6 2350.15
  2013.7 2348.16    2052 2349.88  2306.9 2352.44  2386.2 2356.22  2394.5 2356.17
#Mann= 9 ,-1,0
       0     .08       0   178.5     .05       0   798.3    .045       0
     823     .05       0  1057.8    .045       0  1080.4     .05       0
  1228.3    .045       0  1280.6     .05       0  2386.2    .016       0
#XS Ineff= 2 , 0
          547.89 2355.15
Permanent Ineff=
       F       F
Bank Sta=1228.3,1280.6
XS Rating Curve= 0 ,0
Exp/Cntr(USF)=0,0
Exp/Cntr=0.3,0.1

Type RM Length L Ch R = 1 ,74763   ,562,564.4,529.1
XS GIS Cut Line= 2
2271124.04209129 433968.889325882268998.46904988435990.188972808
#Sta/Elev= 30
       0 2396.91      85 2397.39     192 2389.42   243.4 2381.24   291.5 2360.79
   347.6 2353.72   493.8 2346.33     726 2348.03   816.8 2343.93   854.6 2344.26
    1047 2347.02  1125.9 2343.57  1148.8 2347.73  1175.5 2347.49  1182.8 2342.47
    1231 2340.85  1239.52341.479    1477 2344.76  1502.5 2348.32  2218.8 2346.97
  2527.9 2349.87  2546.5 2352.76  2574.8 2352.29  2588.9 2350.89  2620.1 2357.98
  2682.3 2394.42  2798.3 2477.52  2840.7 2497.27  2908.7 2521.45  2933.2 2534.41
#Mann= 10 ,-1,0
       0     .05       0     310      .1       0     390     .05       0
   816.8    .045       0   854.6     .05       0  1182.8    .045       0
  1239.5     .05       0  2546.5    .016       0  2574.8     .05       0
    2840      .1       0
#XS Ineff= 2 , 0
          719.54 2351.19
Permanent Ineff=
       F       F
Bank Sta=1182.8,1239.5
XS Rating Curve= 0 ,0
Exp/Cntr(USF)=0,0
Exp/Cntr=0.3,0.1

Type RM Length L Ch R = 1 ,74199   ,294.7,537,520.9
XS GIS Cut Line= 4
2270731.94663636433932.5164593982270100.27071566434156.939891866
2269586.20973083434722.2347567052268792.05120467435657.733253063
#Sta/Elev= 30
       0 2377.54    53.6  2372.9    97.4 2360.25   186.5 2355.39   470.9 2351.75
   517.6 2347.65   987.7 2341.61  1016.7 2341.88  1069.9 2343.26  1135.12340.397
  1180.3 2339.43 1192.41 2340.41  1199.6 2342.48  1217.1 2342.83  1297.8 2340.77
  1314.1 2345.35  1330.3 2347.09  1695.4 2344.87  2067.4 2347.33  2209.9 2353.67
  2220.1 2352.05  2232.6 2356.75  2303.5 2359.76  2346.1 2360.19  2352.3 2364.59
  2393.2  2383.6    2445 2417.26  2550.1 2479.55    2627 2531.03  2661.6 2556.98
#Mann= 8 ,-1,0
       0     .05       0   987.7    .045       0  1016.7     .05       0
  1135.1    .045       0 1192.41     .05       0  2248.5     .03       0
  2303.5    .016       0  2346.1      .1       0
#XS Ineff= 2 , 0
                         1417.77         2353.31
Permanent Ineff=
       F       F
#Block Obstruct= 1 ,-1
  2139.8  2188.6 2372.41
Bank Sta=1135.1,1192.41
XS Rating Curve= 0 ,0
Exp/Cntr(USF)=0,0
Exp/Cntr=0.3,0.1

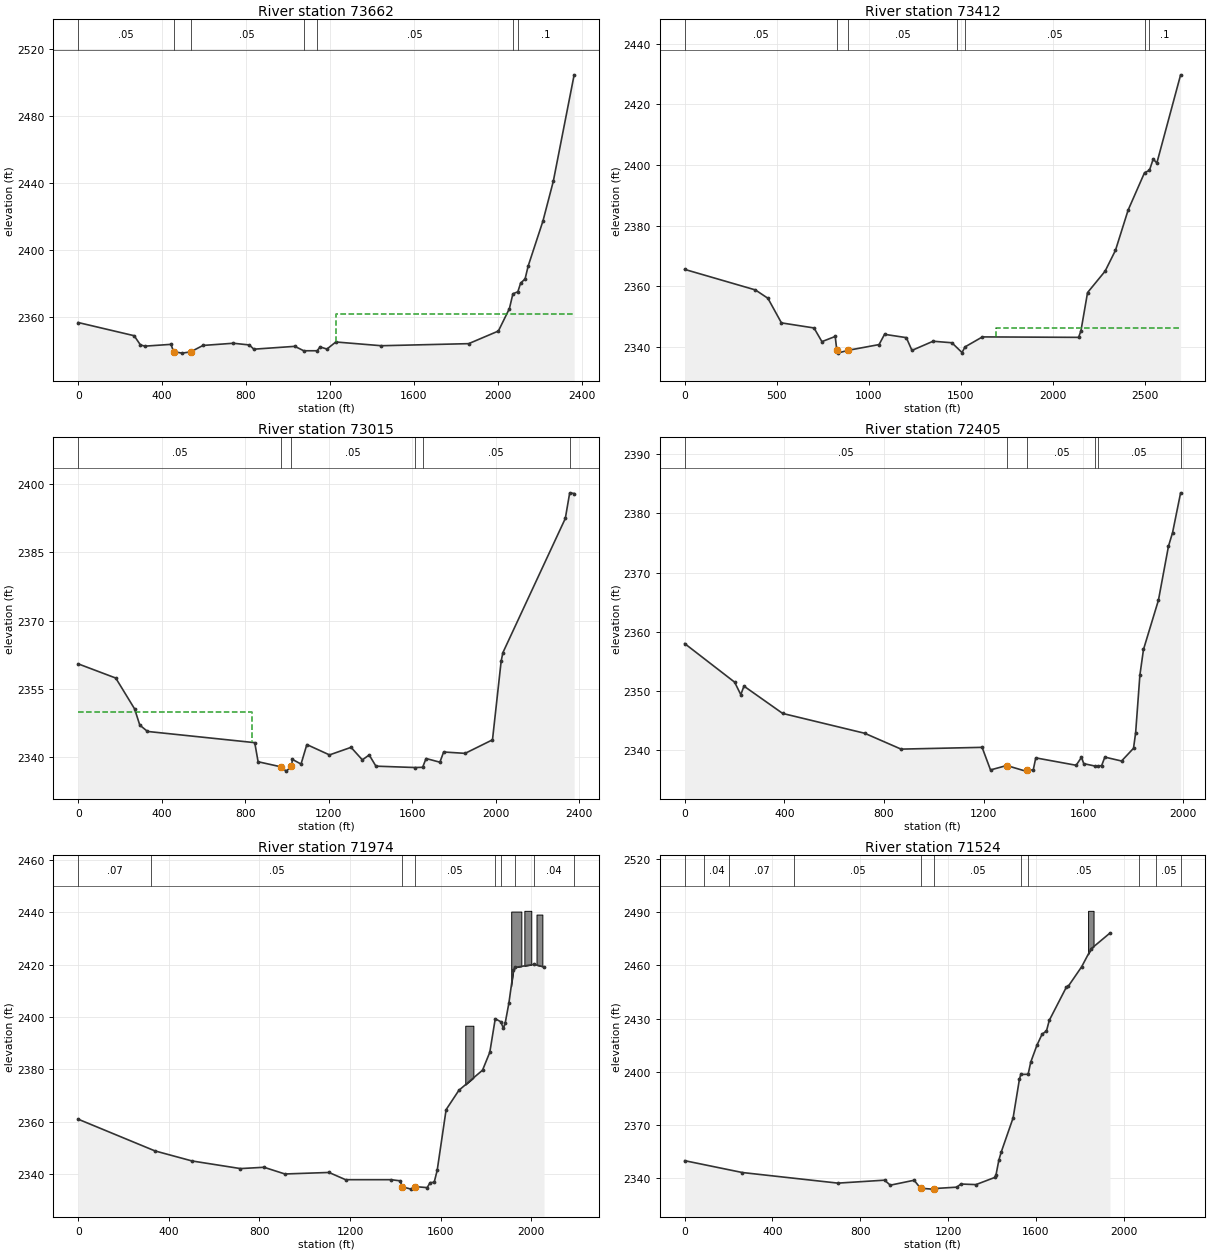
Type RM Length L Ch R = 1 ,73662   ,249.4,249.5,229.2
XS GIS Cut Line= 5
2270289.21697305433844.2788230852269866.33725412434006.232757993
2269780.86156625434017.4795590292268422.24800119434505.590723961
 2268107.3375722434721.529303838
#Sta/Elev= 30
       0 2356.47   266.7  2348.6   296.7 2343.08   318.1 2342.37   442.3 2343.44
     455 2339.02   495.4  2338.2   535.8 2338.95     595 2342.79   739.7  2344.1
     816 2343.08   837.3 2340.56  1032.8 2342.25  1075.3 2339.61  1139.1 2339.62
  1153.3 2341.91  1185.8 2340.63  1228.3 2344.86  1445.1 2342.62  1861.6 2343.86
  2003.2 2351.39  2055.8 2364.81  2072.5 2373.63  2096.1 2374.85  2109.3 2380.04
  2130.5 2382.48  2145.2 2390.19  2215.4 2416.97  2264.9 2440.71  2364.5 2504.41
#Mann= 7 ,-1,0
       0     .05       0     455    .045       0   535.8     .05       0
  1075.3    .045       0  1139.1     .05       0  2072.5    .016       0
  2096.1      .1       0
#XS Ineff= 2 , 0
                         1230.99         2361.46
Permanent Ineff=
       F       F
Bank Sta=455,535.8
XS Rating Curve= 0 ,0
Exp/Cntr(USF)=0,0
Exp/Cntr=0.3,0.1

Type RM Length L Ch R = 1 ,73412   ,383,397.7,374.4
XS GIS Cut Line= 3
2270613.37948669433473.3736866272268987.64318245434064.550524534
2268023.28596561434001.737985507
#Sta/Elev= 30
       0 2365.55   384.3 2358.78   452.4 2356.03   526.1 2347.91   703.1 2346.24
   746.1 2341.73   818.5 2343.44     827 2338.88   831.3 2337.94   887.12338.851
  1056.8 2340.76  1086.6 2344.14    1205 2343.05  1235.6 2338.84  1350.5 2341.86
  1452.7 2341.36    1508 2338.12    1524 2339.99  1618.7 2343.29  2141.6 2343.14
  2154.3 2345.27  2190.3  2357.9  2285.8 2364.97  2342.2 2371.85  2410.8 2385.09
  2500.3 2397.46  2526.6 2398.18  2547.1 2401.91  2567.1 2400.63  2696.3  2429.7
#Mann= 7 ,-1,0
       0     .05       0     827    .045       0   887.1     .05       0
    1480    .045       0    1524     .05       0  2500.3    .016       0
  2526.6      .1       0
#XS Ineff= 2 , 0
                         1694.04         2346.22
Permanent Ineff=
       F       F
Bank Sta=827,887.1
XS Rating Curve= 0 ,0
Exp/Cntr(USF)=0,0
Exp/Cntr=0.3,0.1

Type RM Length L Ch R = 1 ,73015   ,570.5,610,415.1
Node Name=AA
XS GIS Cut Line= 5
2270487.16067127433259.4451692492269553.67618534433479.882469541
2269504.19026079433524.8696736822268505.47432885433783.546097494
2268204.06006111433682.324888177
#Sta/Elev= 30
       0 2360.49   179.8 2357.38   270.2  2350.6   294.9 2347.06   331.9 2345.66
   845.6  2343.2   861.7 2339.01   969.6 2337.91   996.8 2336.95  1021.7 2338.03
  1026.1 2339.52  1067.4  2338.5  1095.2 2342.78  1203.7 2340.51    1307 2342.17
  1361.1 2339.42  1393.9  2340.5  1426.1 2338.04  1613.8 2337.74  1649.9 2337.79
  1666.3 2339.72  1732.6 2338.91  1750.5 2341.15  1853.4 2340.85  1984.5 2343.82
    2026 2361.07  2034.3 2362.95  2333.3  2392.4  2354.4 2398.03  2375.7 2397.88
#Mann= 6 ,-1,0
       0     .05       0   969.6    .045       0  1021.7     .05       0
  1613.8    .045       0  1649.9     .05       0  2354.4    .016       0
#XS Ineff= 2 , 0
           833.3    2350
Permanent Ineff=
       F       F
Bank Sta=969.6,1021.7
XS Rating Curve= 0 ,0
Exp/Cntr(USF)=0,0
Exp/Cntr=0.3,0.1

Type RM Length L Ch R = 1 ,72405   ,397.1,430.1,449.4
XS GIS Cut Line= 5
2270246.47912912432735.3442410042269088.05862248433110.987395583
2268959.84509068433248.1983682142268534.71601154433405.653582708
2268404.25311953433385.409340845
#Sta/Elev= 30
       0 2358.01   200.5 2351.49   225.3 2349.37   237.9 2350.82   393.5  2346.2
   722.6 2342.85   868.7 2340.17    1194 2340.47  1227.8 2336.65  1292.9  2337.4
  1368.6 2336.45  1375.8 2336.66  1399.3 2336.64  1409.5 2338.69  1571.6 2337.44
  1592.9 2338.78  1602.2 2337.71  1648.4  2337.3  1658.2  2337.3    1674 2337.39
  1686.8 2338.82  1753.9 2338.16  1801.9 2340.31  1810.5 2342.97  1827.5 2352.68
  1841.9 2357.01    1902 2365.35  1942.2 2374.46  1958.7 2376.77    1991 2383.49
#Mann= 6 ,-1,0
       0     .05       0  1292.9    .045       0  1375.8     .05       0
  1648.4    .045       0  1658.2     .05       0    1991    .016       0
Bank Sta=1292.9,1375.8
XS Rating Curve= 0 ,0
Exp/Cntr(USF)=0,0
Exp/Cntr=0.3,0.1

Type RM Length L Ch R = 1 ,71974   ,400.8,450.1,415.8
XS GIS Cut Line= 4
2270126.69395649432377.5077524972269389.47289023432546.397983611
2268606.89726844432914.9517397952268173.80204972 432955.22710764
#Sta/Elev= 30
       0  2360.9     339 2348.78   502.6 2344.94   716.3 2342.03   820.1 2342.53
   912.5 2339.97    1107 2340.55  1180.2 2337.79  1381.2 2337.79    1421 2337.35
  1430.62335.086  1468.8 2334.18  1486.8 2335.14  1540.3 2334.76  1553.6 2336.66
  1571.3 2336.78  1584.6 2341.31  1624.1 2364.56  1680.3 2371.93  1784.8 2379.63
  1816.9 2386.47    1841  2399.3  1865.1 2398.15  1877.2 2395.61  1885.2  2397.8
  1901.3 2405.32  1921.3 2417.79  1929.4 2418.93  2011.7 2420.06  2056.3  2419.1
#Mann= 9 ,-1,0
       0     .07       0     320     .05       0  1430.6    .045       0
  1486.8     .05       0    1841    .016       0  1865.1     .05       0
  1929.4    .016       0  2011.7     .04       0 2189.28      .1       0
#Block Obstruct= 4 ,-1
 1708.57 1744.43 2396.62 1911.44  1956.2 2440.25 1969.49 2000.03 2440.53
 2023.05 2048.98  2439.1
Bank Sta=1430.6,1486.8
XS Rating Curve= 0 ,0
Exp/Cntr(USF)=0,0
Exp/Cntr=0.3,0.1

Type RM Length L Ch R = 1 ,71524   ,669.1,742.1,573.2
XS GIS Cut Line= 4
2269755.00817867432222.4547374492269151.04070828 432233.73691483
2267990.37084143432721.848079762 2267937.9944474432775.060669741
#Sta/Elev= 30
       0 2350.01   262.9 2343.34   698.3 2337.38   910.9 2339.04     937 2336.22
  1045.5    2339  1074.8  2334.5  1127.9    2334  1135.62334.309  1240.7 2335.11
  1258.1 2336.87  1327.5 2336.55  1414.3 2340.63  1418.4 2341.83  1431.7  2350.3
  1442.8 2354.96  1496.7 2374.11  1525.3 2395.73  1531.6 2398.52    1565 2398.63
  1577.2 2405.53  1605.2 2414.96  1628.9 2421.23  1648.6 2422.96  1661.6    2429
  1739.1 2447.59  1748.4 2448.22  1809.2 2459.15  1852.1 2469.22  1937.9 2478.07
#Mann= 11 ,-1,0
       0     .05       0      90     .04       0     200     .07       0
     500     .05       0  1074.8    .045       0  1135.6     .05       0
  1531.6    .016       0    1565     .05       0    2070     .04       0
    2150     .05       0    2260      .1       0
#Block Obstruct= 1 ,-1
 1838.37  1863.2 2490.59
Bank Sta=1074.8,1135.6
XS Rating Curve= 0 ,0
Exp/Cntr(USF)=0,0
Exp/Cntr=0.3,0.1