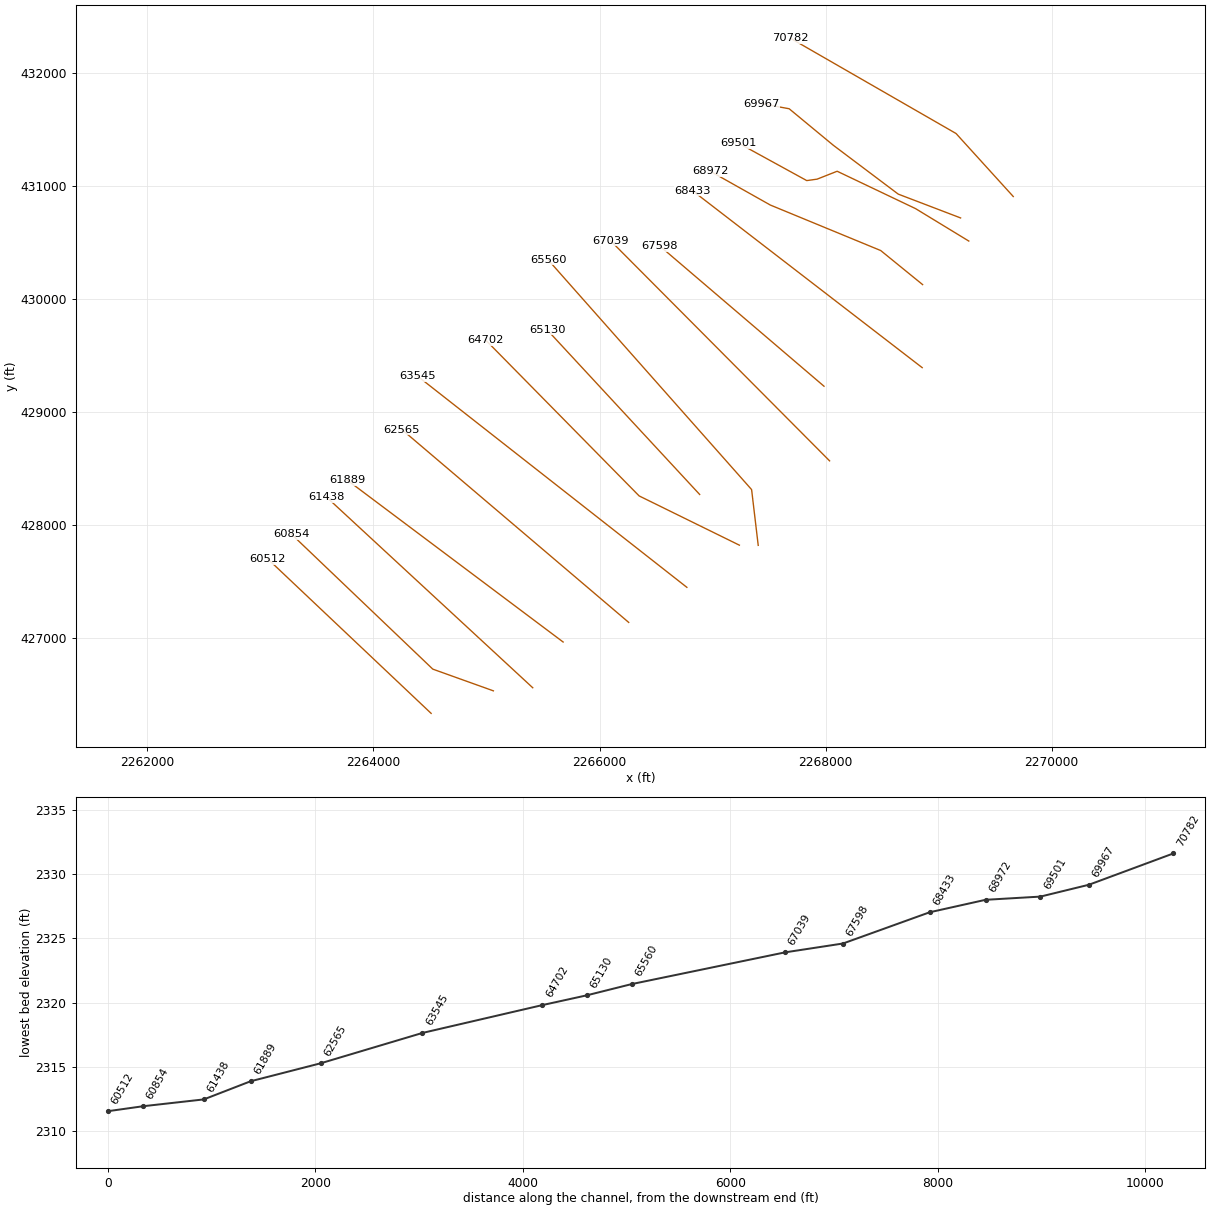
HEC-RAS study KNAPPCK.prj: KNAPPCK

--- KNAPPCK.g01 (geometry) --- (continued)

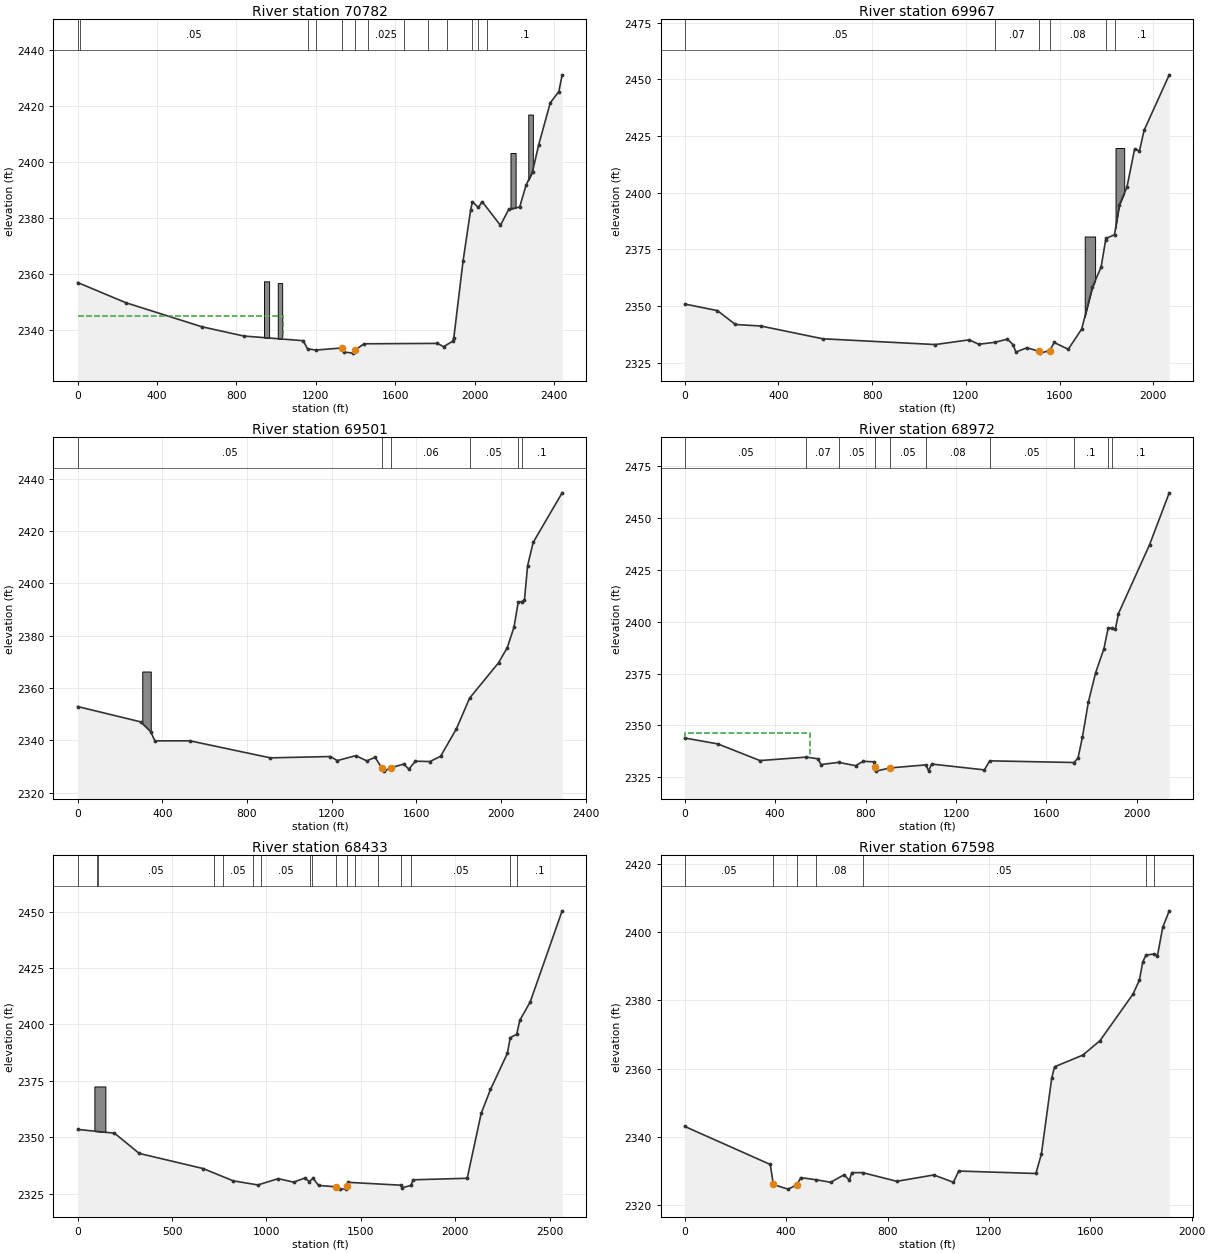
Type RM Length L Ch R = 1 ,70782   ,697.1,815,591.9
Node Name=Z
XS GIS Cut Line= 3
2269660.10683557430909.1441522072269153.91166811431467.067292981
2267690.74899429432309.494286998
#Sta/Elev= 30
       0 2356.87   243.5 2349.63   626.6 2341.03   838.2 2337.72  1136.9 2336.06
  1158.4 2333.14  1201.4 2332.71  1333.12333.467  1341.5    2332  1387.7 2331.61
  1399.52332.742  1443.1 2334.95  1812.3 2335.09  1844.6 2333.93  1889.7 2335.86
  1895.6    2337  1942.5 2364.63  1980.5 2382.82  1989.3 2385.71    2020 2383.71
  2038.5 2385.82  2130.8 2377.33  2172.3 2383.04  2227.7 2383.88    2260 2391.73
  2292.3 2396.49  2323.2 2406.05  2381.8 2421.15    2425 2425.19  2441.7 2431.17
#Mann= 13 ,-1,0
       0      .1       0      10     .05       0  1158.4    .045       0
  1201.4     .05       0  1333.1    .045       0  1399.5     .05       0
 1463.33    .025       0 1643.33     .05       0 1763.33      .1       0
 1863.33     .05       0  1989.3    .016       0    2020     .04       0
 2063.33      .1       0
#XS Ineff= 2 , 0
            1037 2345.06
Permanent Ineff=
       F       F
#Block Obstruct= 4 ,-1
  939.33  964.91  2357.3 1008.48 1030.86 2356.66  2181.3 2207.21 2403.21
 2270.98 2294.03 2416.96
Bank Sta=1333.1,1399.5
XS Rating Curve= 0 ,0
Exp/Cntr(USF)=0,0
Exp/Cntr=0.3,0.1

Type RM Length L Ch R = 1 ,69967   ,94.3,466.6,475.9
XS GIS Cut Line= 5
 2269194.1845593430719.5982710252268642.69867216430930.359696323
2268069.11181936431362.2368560792267677.72314334431686.144725895
2267430.59628581431731.398451459
#Sta/Elev= 30
       0 2350.82   139.2 2347.94   216.3  2341.8     325 2341.13   588.8  2335.5
  1069.2 2332.95  1214.4 2335.04  1254.5 2333.09  1323.4 2333.94  1377.1 2335.33
  1400.8 2332.94  1413.4 2329.66  1460.2 2331.53  1510.12330.045  1517.3 2329.17
  1558.3 2330.31  1576.5 2333.88  1636.7 2330.88  1693.8 2339.75  1739.6 2358.18
  1777.1 2367.22  1796.1 2378.97  1799.8 2379.85  1834.1 2381.39  1854.7 2394.58
  1887.1 2402.34  1919.7 2419.12  1940.7  2418.4  1960.3 2427.43  2067.7 2451.93
#Mann= 6 ,-1,0
       0     .05       0  1323.4     .07       0  1510.1    .045       0
  1558.3     .08       0  1799.8    .016       0  1834.1      .1       0
#Block Obstruct= 2 ,-1
 1706.98 1751.37 2380.62 1838.43  1875.6 2419.64
Bank Sta=1510.1,1558.3
XS Rating Curve= 0 ,0
Exp/Cntr(USF)=0,0
Exp/Cntr=0.3,0.1

Type RM Length L Ch R = 1 ,69501   ,482.7,529,333.2
XS GIS Cut Line= 6
2269266.82251576430514.9010433472268795.65516624430802.146164521
2268102.16118529431132.9225913042267925.15276611 431063.07194854
2267833.41016495431050.1975925072267233.10289667431379.674027001
#Sta/Elev= 30
       0 2352.92   297.5 2347.08   345.1 2343.33   364.5 2339.81   530.4 2339.83
   910.2 2333.32  1193.8 2333.83  1225.8 2332.27  1313.5 2334.16  1365.3 2332.17
  1404.7 2333.52  1435.22329.623    1447 2328.25  1480.52329.556  1539.7 2330.95
    1564 2329.01  1594.5 2332.04  1663.8 2331.92    1714 2333.93  1788.9 2344.46
  1850.7 2356.13  1987.8 2369.68  2028.9 2375.47  2060.8 2383.32  2080.5 2392.91
  2099.8 2393.04    2110 2393.67  2124.7 2406.74  2151.2 2415.66  2287.9 2434.58
#Mann= 6 ,-1,0
       0     .05       0  1435.2    .045       0  1480.5     .06       0
  1850.7     .05       0  2080.5    .016       0  2099.8      .1       0
#Block Obstruct= 1 ,-1
  305.18  345.23 2366.31
Bank Sta=1435.2,1480.5
XS Rating Curve= 0 ,0
Exp/Cntr(USF)=0,0
Exp/Cntr=0.3,0.1

Type RM Length L Ch R = 1 ,68972   ,553.5,538.5,350.3
XS GIS Cut Line= 4
 2268858.2501347430129.3674618932268487.49281788430431.001730356
2267511.27048801 430833.637207422266980.55485796431132.465131112
#Sta/Elev= 30
       0 2343.96   146.4 2341.11   332.7 2333.09   537.8 2334.75   589.4 2333.94
   602.7 2331.16   680.6 2332.23   756.4 2330.61   788.5 2332.74   836.4 2332.49
   840.9  2329.8     845    2328   909.9 2329.57  1065.7    2331  1078.7 2328.21
  1092.1 2331.41  1325.3  2328.6  1349.1 2332.96  1721.9 2332.15  1739.5  2334.3
  1759.1 2344.43  1785.5 2361.39  1817.5 2375.43  1854.3 2387.05  1872.6 2396.88
    1890 2396.96  1904.7 2396.42  1918.5 2403.94  2055.7 2437.03    2143 2462.09
#Mann= 10 ,-1,0
       0     .05       0   537.8     .07       0   680.6     .05       0
   840.9    .045       0   909.9     .05       0  1065.7     .08       0
  1349.1     .05       0  1721.9      .1       0  1872.6    .016       0
    1890      .1       0
#XS Ineff= 2 , 0
          553.52 2346.53
Permanent Ineff=
       F       F
Bank Sta=840.9,909.9
XS Rating Curve= 0 ,0
Exp/Cntr(USF)=0,0
Exp/Cntr=0.3,0.1

Type RM Length L Ch R = 1 ,68433   ,672.4,835.3,603
Node Name=Y
XS GIS Cut Line= 2
2268854.62839392 429394.253505072266822.45801361430960.872125523
#Sta/Elev= 30
       0 2353.47   194.9 2351.82   326.1 2342.85   664.7 2336.14   823.7  2330.7
   954.8 2328.88  1061.9 2331.67  1144.5 2330.12  1204.5 2331.99  1225.3 2330.38
  1247.3  2331.8  1275.8 2328.65  1369.9 2328.07  1387.1 2327.03  1421.3  2327.1
  1425.32328.461  1432.7 2330.04  1710.2 2328.78  1720.3 2327.71  1765.8 2328.66
  1775.9 2331.16    2063 2331.84  2137.1 2360.57  2186.4 2371.17  2275.9  2387.2
  2291.1 2394.12  2325.4 2395.61  2341.5  2401.8  2396.7 2409.94  2565.9  2450.3
#Mann= 17 ,-1,0
       0     .05       0     100     .04       0     110     .05       0
     720     .07       0     770     .05       0     930     .07       0
     970     .05       0    1230      .1       0    1240     .05       0
  1369.9    .045       0  1425.3      .1       0    1470     .05       0
    1590     .07       0  1710.2    .045       0  1765.8     .05       0
  2291.1    .016       0  2325.4      .1       0
#Block Obstruct= 1 ,-1
   88.72  146.95 2372.51
Bank Sta=1369.9,1425.3
XS Rating Curve= 0 ,0
Exp/Cntr(USF)=0,0
Exp/Cntr=0.3,0.1

Type RM Length L Ch R = 1 ,67598   ,446,558.9,337
XS GIS Cut Line= 2
 2267985.8854917429229.8433797862266532.79879794430471.490214083
#Sta/Elev= 30
       0 2343.01   337.6 2331.83   349.5 2325.96   407.4  2324.6   442.3 2325.83
   457.5 2327.97   517.1 2327.37   575.7 2326.61   628.4 2328.81   649.4 2327.21
     659 2329.44     702 2329.44   836.4  2326.9   982.4 2328.76  1059.8 2326.61
  1080.8 2329.91  1385.3 2329.19    1407 2334.91  1447.7  2357.2    1459 2360.52
  1570.2 2363.94  1637.8 2368.16  1768.3 2381.84  1793.8 2386.01  1806.9 2391.33
  1819.3 2393.28  1852.3 2393.66  1864.7 2393.09  1885.8 2401.53  1911.3  2406.3
#Mann= 7 ,-1,0
       0     .05       0   349.5    .045       0   442.3     .05       0
   517.1     .08       0     702     .05       0  1819.3    .016       0
  1852.3     .08       0
Bank Sta=349.5,442.3
XS Rating Curve= 0 ,0
Exp/Cntr(USF)=0,0
Exp/Cntr=0.3,0.1

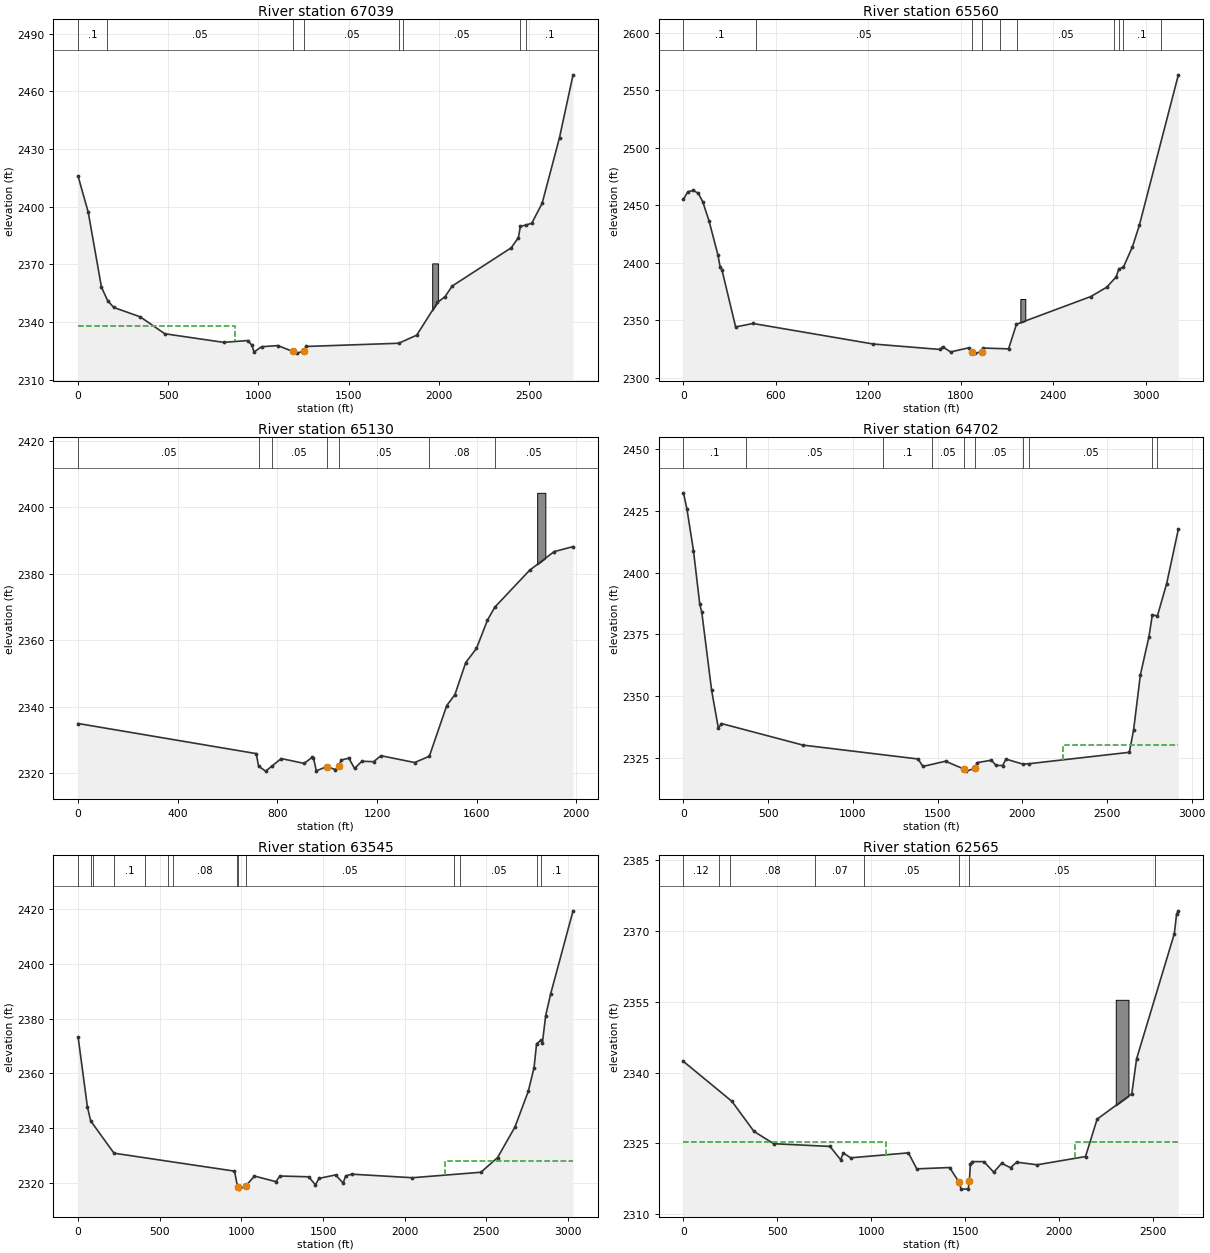
Type RM Length L Ch R = 1 ,67039   ,715.7,1478.6,591.6
XS GIS Cut Line= 2
2268035.28284126428569.1603998192266099.17869711430516.349109675
#Sta/Elev= 30
       0 2415.75      56 2397.09   129.2 2358.21   163.4 2351.21   197.4 2347.65
   344.1 2342.78   480.9 2333.97   806.7 2329.52     942 2330.44   963.9 2328.01
   975.9 2324.48  1017.6 2327.23  1108.1 2327.84  1190.2 2324.81  1212.8 2323.91
  1255.2 2325.02  1263.6 2327.37  1778.5 2329.04  1878.4 2333.24  1993.4 2350.24
  2035.9 2353.27  2075.1 2358.76    2403 2378.66  2442.5 2383.93  2453.8  2389.8
  2483.5 2390.46  2516.7 2391.41  2574.3 2401.75  2670.8 2435.95  2745.9 2468.54
#Mann= 8 ,-1,0
       0      .1       0     160     .05       0  1190.2    .045       0
  1255.2     .05       0  1778.5    .045       0    1800     .05       0
  2453.8    .016       0  2483.5      .1       0
#XS Ineff= 2 , 0
           871.3 2338.21
Permanent Ineff=
       F       F
#Block Obstruct= 1 ,-1
  1964.4 1995.83 2370.55
Bank Sta=1190.2,1255.2
XS Rating Curve= 0 ,0
Exp/Cntr(USF)=0,0
Exp/Cntr=0.3,0.1

Type RM Length L Ch R = 1 ,65560   ,389.4,430.2,400.2
Node Name=X
XS GIS Cut Line= 3
 2267403.8882173427821.0101973862267345.41490609428314.784825422
2265545.73632759430348.356648777
#Sta/Elev= 30
       0 2455.24    28.4 2461.72    64.7 2462.92    96.8 2460.31     125 2453.11
   165.6 2436.58   223.2 2407.11   237.8 2396.72   249.9  2393.8   338.6 2344.21
   451.3 2347.21  1232.2 2329.36    1664 2324.65  1682.1 2326.96  1734.3 2322.48
  1851.1 2326.04  1874.92322.507  1894.5 2321.44  1937.3  2322.6  1942.6 2325.87
  2110.6 2325.16  2161.6 2346.55  2644.9 2370.67  2746.9 2378.69  2809.3  2387.8
  2826.3  2394.7    2856 2396.16  2914.8 2413.95  2959.4 2432.51  3212.8 2563.43
#Mann= 10 ,-1,0
       0      .1       0     470     .05       0  1874.9    .045       0
  1937.3     .05       0 2057.22     .07       0 2167.22     .05       0
 2797.22      .1       0  2826.3    .016       0    2856      .1       0
 3097.22     .05       0
#Block Obstruct= 1 ,-1
 2186.99  2219.2 2368.52
Bank Sta=1874.9,1937.3
XS Rating Curve= 0 ,0
Exp/Cntr(USF)=0,0
Exp/Cntr=0.3,0.1

Type RM Length L Ch R = 1 ,65130   ,423.5,428,428.1
XS GIS Cut Line= 2
2266885.94835045428271.6159315782265536.33222621429729.201345753
#Sta/Elev= 30
       0  2334.9     715 2325.84   724.1 2322.07   752.4 2320.57   776.2 2321.98
   815.1 2324.36   907.1 2322.89   939.8 2324.77   944.6 2324.54   956.1 2320.66
   998.7 2321.96  1032.9    2321  1045.32322.165  1056.5 2323.91  1086.4 2324.49
  1109.5 2321.37  1138.9 2323.55    1186 2323.41  1215.4 2325.21  1350.8 2323.16
  1409.7 2325.05  1479.5 2340.31  1512.2 2343.59  1555.8 2353.25  1598.8  2357.5
    1643 2366.02  1672.4 2369.92    1812 2381.02  1910.2 2386.63  1986.5 2388.15
#Mann= 7 ,-1,0
       0     .05       0   724.1    .045       0   776.2     .05       0
   998.7    .045       0  1045.3     .05       0  1409.7     .08       0
  1672.4     .05       0
#Block Obstruct= 1 ,-1
 1842.45 1875.31 2404.34
Bank Sta=998.7,1045.3
XS Rating Curve= 0 ,0
Exp/Cntr(USF)=0,0
Exp/Cntr=0.3,0.1

Type RM Length L Ch R = 1 ,64702   ,497.5,1157.5,494.6
XS GIS Cut Line= 3
2267237.19411008427822.7996419622266350.42885322428258.792559918
2264994.41698127429636.973563288
#Sta/Elev= 30
       0 2432.18    20.5 2425.63    59.1 2408.81    96.1 2387.27   108.1 2383.98
   166.1 2352.46   206.2 2337.06     224 2339.02   705.4 2330.32  1384.9 2324.71
  1413.4 2321.71    1547 2323.81  1658.6 2320.56  1670.1 2319.81  1723.32321.042
  1732.2 2323.22  1818.3 2324.22  1844.5 2322.14  1883.7 2322.06  1903.9 2324.66
    2004 2322.64  2040.9 2322.81    2632 2327.41  2657.4 2336.43  2697.4 2358.69
    2748 2374.08  2767.7  2382.8  2798.4 2382.58  2852.6 2395.56  2921.6 2417.48
#Mann= 10 ,-1,0
       0      .1       0     370     .05       0 1178.15      .1       0
 1468.15     .05       0  1658.6    .045       0  1723.3     .05       0
    2004    .045       0  2040.9     .05       0  2767.7    .016       0
  2798.4     .05       0
#XS Ineff= 2 , 0
                         2242.86         2330.53
Permanent Ineff=
       F       F
Bank Sta=1658.6,1723.3
XS Rating Curve= 0 ,0
Exp/Cntr(USF)=0,0
Exp/Cntr=0.3,0.1

Type RM Length L Ch R = 1 ,63545   ,799.5,980,503.7
Node Name=W
XS GIS Cut Line= 2
2266772.78318721427449.5382471472264388.37149656429320.684206017
#Sta/Elev= 30
       0 2373.13    56.7 2347.65    77.1 2342.54   219.5 2330.78   957.4 2324.22
   976.32318.558   987.2 2317.64  1027.42318.874  1079.9 2322.41  1210.9 2320.38
  1236.3 2322.43  1411.9 2322.15  1453.1 2319.21  1475.3 2321.56    1577 2322.84
  1622.8 2319.83  1638.3 2322.46  1675.3 2323.11  2046.9 2321.81  2466.8 2323.81
  2568.5 2329.17  2674.9 2340.32  2756.6 2353.38    2792 2362.05  2807.5 2370.78
  2834.9 2372.15  2843.1  2371.1  2863.3 2381.09  2893.9 2389.05  3030.9 2419.38
#Mann= 14 ,-1,0
       0     .12       0      80      .1       0      90     .12       0
     220      .1       0     410     .08       0     550      .1       0
     580     .08       0     970     .05       0   976.3    .045       0
  1027.4     .05       0    2300     .07       0    2340     .05       0
  2807.5    .016       0  2834.9      .1       0
#XS Ineff= 2 , 0
                         2249.12         2327.78
Permanent Ineff=
       F       F
Bank Sta=976.3,1027.4
XS Rating Curve= 0 ,0
Exp/Cntr(USF)=0,0
Exp/Cntr=0.3,0.1

Type RM Length L Ch R = 1 ,62565   ,580.4,675.6,599.3
XS GIS Cut Line= 2
 2266258.0574723427139.2514231322264251.75107865428846.274542588
#Sta/Elev= 30
       0 2342.36   258.1 2333.89   375.4 2327.52   480.4 2324.91   779.8 2324.34
   836.3 2321.53   851.1 2322.94     890 2321.92  1197.3 2322.97  1241.9 2319.58
  1416.5 2319.86    1466 2316.81  1478.2 2315.28  1515.3  2315.3  1521.5  2316.9
  1527.6 2320.71  1537.8 2321.12  1599.1 2321.11  1651.6 2318.87  1693.6 2320.75
  1740.9 2319.83  1773.4    2321  1882.7 2320.44    2140 2322.19  2201.8 2330.12
  2386.3 2335.51  2411.8  2342.9  2612.7 2369.44  2624.6 2373.57  2634.2  2374.3
#Mann= 8 ,-1,0
       0     .12       0     190      .1       0     250     .08       0
     700     .07       0     960     .05       0    1466    .045       0
  1521.5     .05       0    2510     .04       0
#XS Ineff= 2 , 0
         1077.47 2325.28 2084.05         2325.34
Permanent Ineff=
       F       F
#Block Obstruct= 1 ,-1
 2300.95 2368.68 2355.43
Bank Sta=1466,1521.5
XS Rating Curve= 0 ,0
Exp/Cntr(USF)=0,0
Exp/Cntr=0.3,0.1

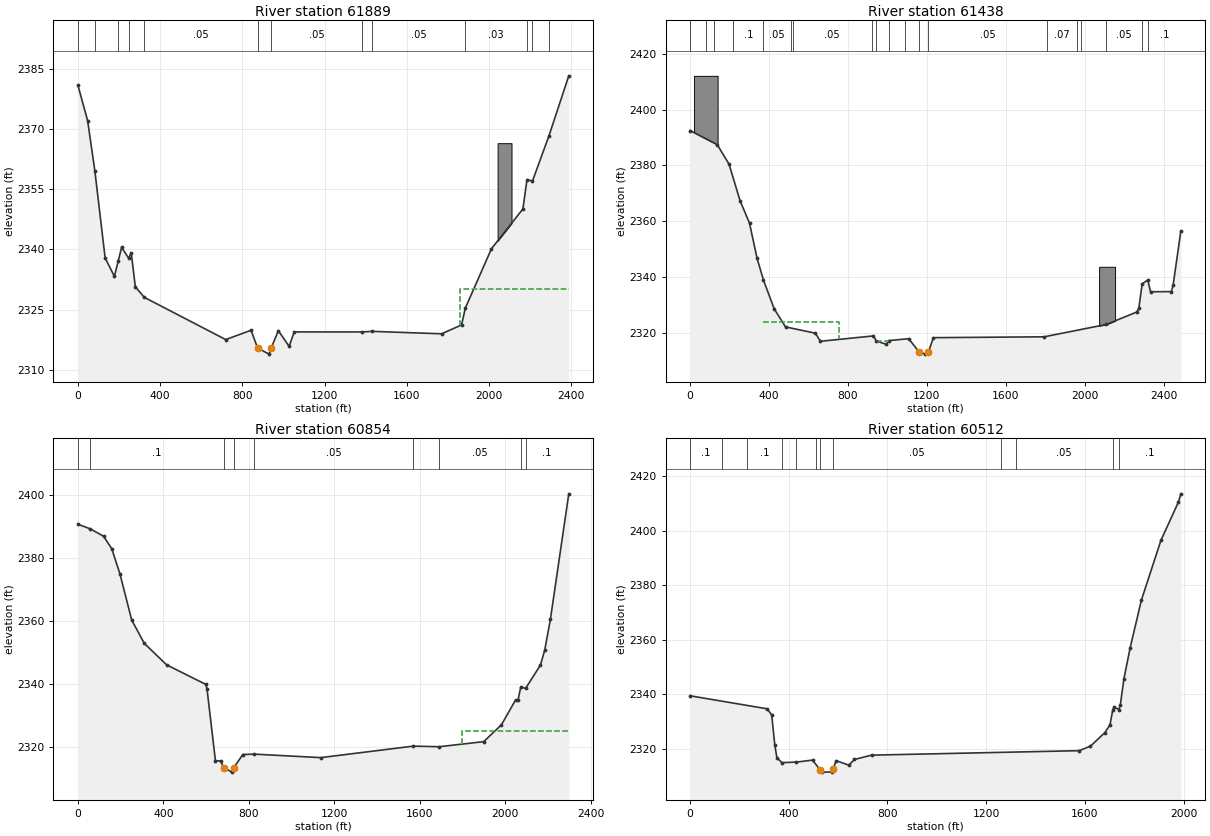
Type RM Length L Ch R = 1 ,61889   ,396.4,450.8,336.8
XS GIS Cut Line= 2
 2265677.9652001426965.5932269972263767.72504262428399.197058921
#Sta/Elev= 30
       0 2380.89    47.2 2372.07    82.3 2359.55   132.3 2337.86   177.3 2333.27
   195.3 2336.99   212.4 2340.49   246.7 2337.81   259.2 2339.16   279.2 2330.69
   322.3 2328.05     719 2317.51   842.4 2319.83   873.82315.435   929.5 2313.88
   940.9 2315.49   975.2 2319.72  1027.5 2315.83  1052.5 2319.42  1382.6 2319.41
  1429.5 2319.56  1769.5 2318.95  1866.6 2321.16  1885.2 2325.39  2012.3 2340.18
  2165.1 2350.08  2185.1 2357.41  2211.7 2357.05  2291.7 2368.29  2388.4 2383.29
#Mann= 13 ,-1,0
       0     .12       0    82.3      .1       0   195.3     .12       0
   246.7      .1       0   322.3     .05       0   873.8    .045       0
   940.9     .05       0  1382.6     .03       0  1429.5     .05       0
  1885.2     .03       0  2185.1    .016       0  2211.7     .03       0
  2291.7      .1       0
#XS Ineff= 2 , 0
                            1857            2330
Permanent Ineff=
       F       F
#Block Obstruct= 1 ,-1
 2042.05 2109.79 2366.49
Bank Sta=873.8,940.9
XS Rating Curve= 0 ,0
Exp/Cntr(USF)=0,0
Exp/Cntr=0.3,0.1

Type RM Length L Ch R = 1 ,61438   ,478.8,584.1,468.6
Node Name=V
XS GIS Cut Line= 2
2265409.29860142426560.5854889812263583.63188461428249.814479627
#Sta/Elev= 30
       0 2392.51   137.8 2387.44   197.7 2380.46   253.1 2367.45   301.3 2359.35
   339.4 2346.84     372 2338.97   426.6 2328.66   483.8 2322.22   635.3 2319.96
   660.5 2317.07   929.6 2318.99   943.8 2317.18   994.7 2315.98  1008.9 2317.33
  1107.8    2318  1159.72313.357  1192.9 2312.47  1208.3 2313.28  1233.1 2318.36
  1794.4 2318.67    2110  2323.1  2263.1 2327.52  2274.2 2328.86  2291.1 2337.61
  2319.4 2339.01  2333.6 2334.79  2439.2 2334.85  2448.4 2337.36  2487.3 2356.57
#Mann= 19 ,-1,0
       0     .05       0      80     .04       0     120     .12       0
     220      .1       0     370     .05       0     510      .1       0
     520     .05       0     920      .1       0   943.8    .045       0
  1008.9      .1       0    1090     .05       0  1159.7     .04       0
  1208.3     .05       0    1810     .07       0    1960     .05       0
    1980     .07       0    2110     .05       0  2291.1    .016       0
  2319.4      .1       0
#XS Ineff= 2 ,-1
  371.52   753.9 2323.99   943.2  1008.9 2317.29
Permanent Ineff=
       F       T
#Block Obstruct= 2 ,-1
   20.38  139.65 2412.08 2073.07 2153.97 2343.74
Bank Sta=1159.7,1208.3
XS Rating Curve= 0 ,0
Exp/Cntr(USF)=0,0
Exp/Cntr=0.3,0.1

Type RM Length L Ch R = 1 ,60854   ,296.1,342.1,299.7
XS GIS Cut Line= 3
2265060.92437554426533.2951642772264525.17036618426725.427636597
2263276.30929611427918.865878122
#Sta/Elev= 30
       0 2390.72      56 2389.31   119.8 2386.93     158 2382.97   196.3 2374.99
   251.5 2360.29   310.1 2352.89   414.4 2346.06     598 2339.83   603.7  2338.5
   643.2  2315.6   667.2 2315.46     6822313.406   719.9 2311.94   728.1 2313.25
   771.4 2317.54   824.3 2317.66  1136.2 2316.55  1568.4  2320.2    1690 2320.01
  1898.4 2321.63  1981.4 2326.97  2047.8  2334.9  2058.9 2334.77    2072 2339.01
  2094.6 2338.57    2164 2345.95  2184.1 2350.74  2210.6 2360.52  2296.6  2400.4
#Mann= 9 ,-1,0
       0     .12       0      56      .1       0     682     .04       0
   728.1      .1       0   824.3     .05       0  1568.4     .07       0
    1690     .05       0    2072    .016       0  2094.6      .1       0
#XS Ineff= 2 , 0
                          1797.5            2325
Permanent Ineff=
       F       F
Bank Sta=682,728.1
XS Rating Curve= 0 ,0
Exp/Cntr(USF)=0,0
Exp/Cntr=0.3,0.1

Type RM Length L Ch R = 1 ,60512   ,336.7,409.4,374.2
XS GIS Cut Line= 2
2264510.39094524426333.772981484 2263065.7025476427700.869419143
#Sta/Elev= 30
       0 2339.52   312.4 2334.75   330.9 2332.54   343.5 2321.41     352 2316.85
     372 2315.02   431.2 2315.23   496.3 2315.96   527.52312.358   535.9 2311.55
   575.3 2311.59   578.4 2312.56   592.5 2315.75   643.4  2314.1   666.1 2316.19
   735.5 2317.77  1576.2 2319.41  1622.1 2321.03    1681 2326.02  1701.7 2328.84
  1712.6 2334.15  1718.7 2335.38  1737.8 2334.49  1743.3 2335.97  1758.3 2345.78
  1783.7 2357.18    1829 2374.56  1908.2 2396.47    1979 2410.47    1989 2413.51
#Mann= 12 ,-1,0
       0      .1       0     130     .05       0     230      .1       0
     372    .045       0   431.2      .1       0     510     .05       0
   527.5     .04       0   578.4     .05       0    1260     .07       0
    1320     .05       0  1712.6    .016       0  1737.8      .1       0
#XS Ineff= 1 ,-1
     372   431.2 2315.02
Permanent Ineff=
       T
Bank Sta=527.5,578.4
XS Rating Curve= 0 ,0
Exp/Cntr(USF)=0,0
Exp/Cntr=0.3,0.1