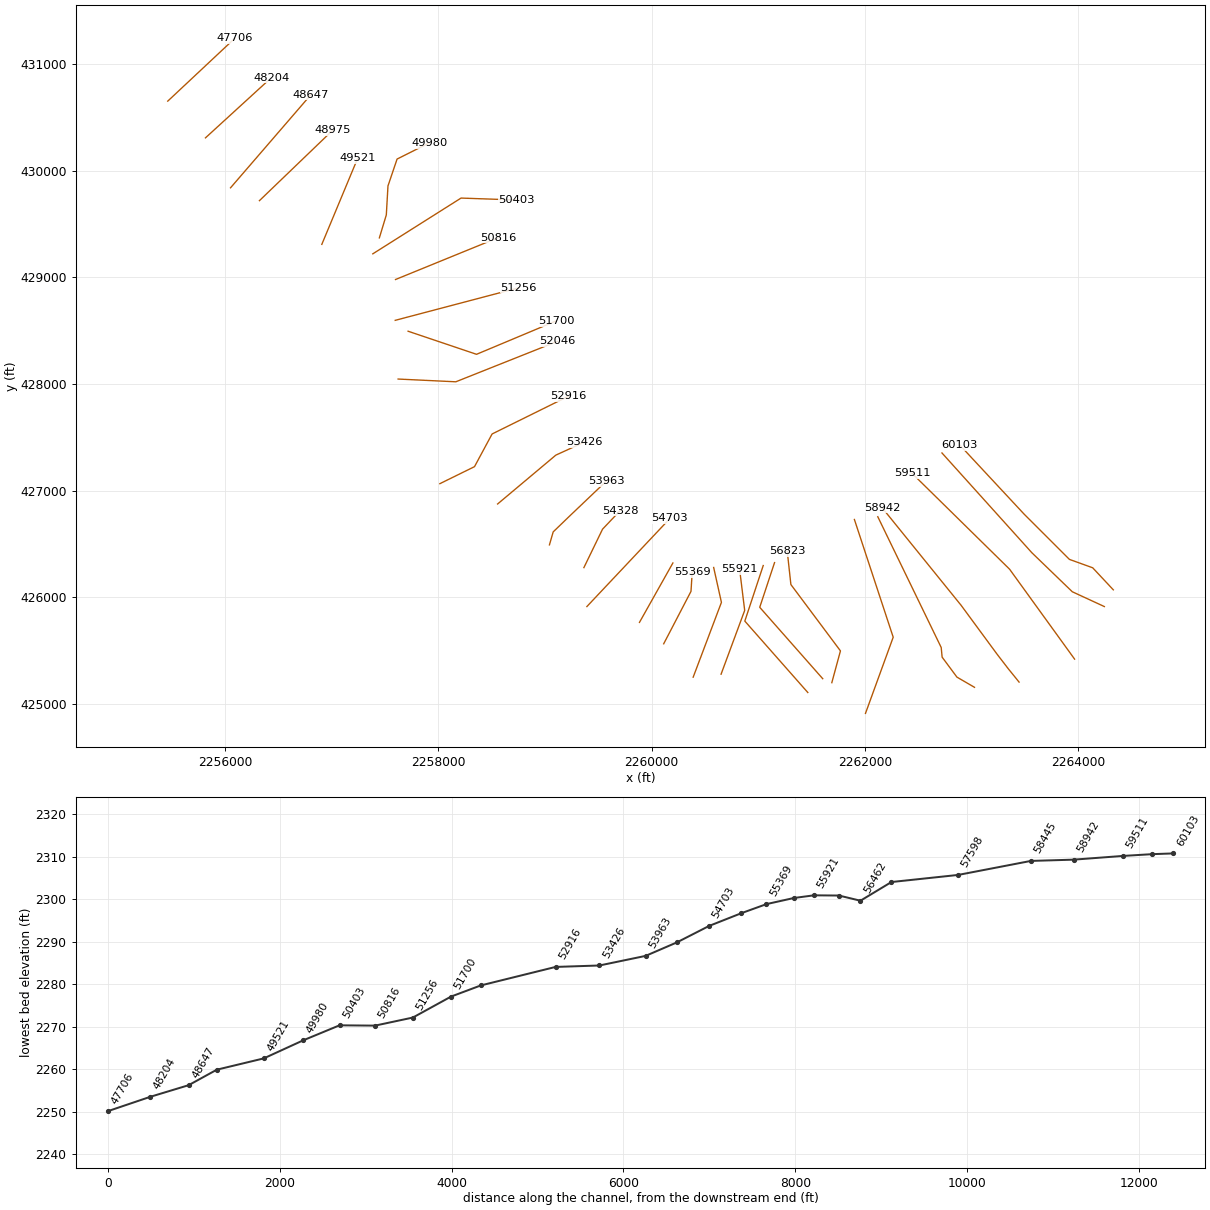
HEC-RAS study KNAPPCK.prj: KNAPPCK

--- KNAPPCK.g01 (geometry) --- (continued)

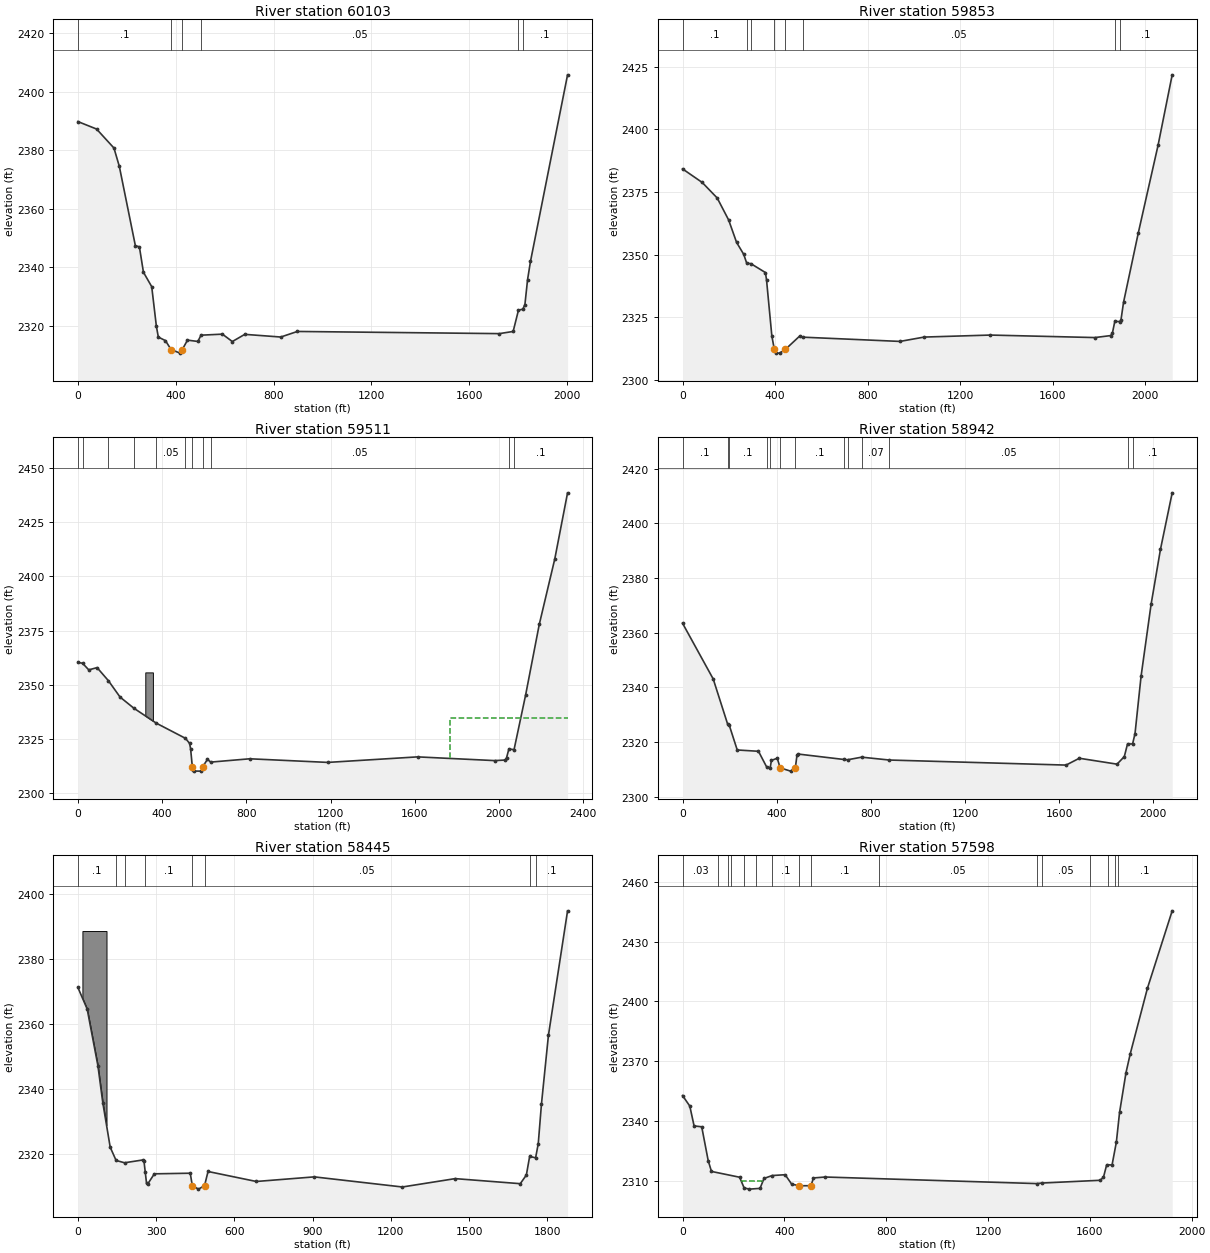
Type RM Length L Ch R = 1 ,60103   ,267.9,249.5,187.4
XS GIS Cut Line= 5
2264328.42579502426069.4922888662264134.98081722426276.433427916
2263916.79287713426355.161035163  2263491.663798426780.290114297
 2262888.8352625427428.105853931
#Sta/Elev= 30
       0 2389.76    76.4 2387.21   147.4 2380.73   169.3 2374.49   234.8 2347.47
   251.4 2347.01   267.9 2338.38   301.7 2333.47   320.8 2319.93   328.8 2316.27
   357.9 2315.06  381.15 2311.97   418.1  2310.8   426.6    2312   447.9 2315.23
   490.4 2314.78   503.1 2316.92   590.6 2317.27   631.2 2314.75   682.1  2317.2
   829.2 2316.29   897.1 2318.19  1722.4 2317.45    1779 2318.19  1800.7 2325.45
  1818.6 2325.79  1827.1 2327.38  1837.9 2335.83  1849.8 2342.06  2001.4  2405.7
#Mann= 6 ,-1,0
       0      .1       0  381.15     .04       0   426.6     .06       0
   503.1     .05       0  1800.7    .016       0  1818.6      .1       0
Bank Sta=381.15,426.6
XS Rating Curve= 0 ,0
Exp/Cntr(USF)=0,0
Exp/Cntr=0.3,0.1

Type RM Length L Ch R = 1 ,59853   ,348.5,342.6,282.5
XS GIS Cut Line= 4
2264244.36136818425912.5594844752263943.78519962 426051.49740721
2263565.14963444426417.1469215792262722.08101057427353.553026873
#Sta/Elev= 30
       0 2384.26      85 2378.84     150 2372.62   199.5 2363.82   233.8 2354.87
   264.6 2350.11   277.8  2346.5   295.5 2346.39   358.4 2342.83   363.2 2339.98
   386.2 2317.51   396.9 2312.16   402.8 2310.63   419.7 2310.62   444.7 2312.11
   506.3 2317.41   519.7    2317   940.4  2315.3  1045.1 2317.04  1331.2 2317.84
  1783.3 2316.84  1851.3 2317.63  1858.7 2318.51  1869.4 2323.29    1892 2323.24
  1896.3 2324.05  1907.1 2330.92  1970.9 2358.66  2056.3 2393.64  2117.5 2421.85
#Mann= 8 ,-1,0
       0      .1       0   277.8    .016       0   295.5      .1       0
   396.9     .04       0   444.7      .1       0   519.7     .05       0
  1869.4    .016       0    1892      .1       0
Bank Sta=396.9,444.7
XS Rating Curve= 0 ,0
Exp/Cntr(USF)=0,0
Exp/Cntr=0.3,0.1

Type RM Length L Ch R = 1 ,59511   ,566.7,568.6,527.8
XS GIS Cut Line= 3
2263965.42954966425419.341333967  2263355.870249426263.067547438
2262440.50707655    427163.40273
#Sta/Elev= 30
       0 2360.31      22 2359.94    51.6 2356.88    91.1 2357.92   144.8 2351.89
   200.2 2344.34   265.8  2339.2   372.4  2332.3   510.5 2325.33   530.3 2322.99
   535.1 2320.51  543.21 2312.26   545.1 2310.53   549.4 2310.23   584.6  2310.2
   591.7 2312.11   615.3 2315.64   630.5 2314.36   815.8 2315.89  1186.5 2314.22
  1612.7 2316.77  1979.4 2315.05  2027.9 2315.31    2035 2316.33  2046.3 2320.42
  2070.7 2320.09  2125.5  2345.2  2190.4 2377.81  2264.1 2408.01  2324.8  2438.5
#Mann= 11 ,-1,0
       0     .04       0      22      .1       0   144.8     .04       0
   265.8     .03       0   372.4     .05       0   510.5      .1       0
  543.21     .04       0   591.7      .1       0   630.5     .05       0
  2046.3    .016       0  2070.7      .1       0
#XS Ineff= 2 , 0
                         1764.95         2334.83
Permanent Ineff=
       F       F
#Block Obstruct= 1 ,-1
  319.97  356.06 2355.72
Bank Sta=543.21,591.7
XS Rating Curve= 0 ,0
Exp/Cntr(USF)=0,0
Exp/Cntr=0.3,0.1

Type RM Length L Ch R = 1 ,58942   ,445.8,497.5,246
XS GIS Cut Line= 5
2263444.94923384425203.8291019942263343.06051867425329.783405541
2263238.80267307425465.4198260282262901.75435266425923.876100199
2262160.78131172426839.957975896
#Sta/Elev= 30
       0 2363.45   130.4 2343.04   191.5 2326.57   197.9 2326.29   232.4 2317.07
   322.7 2316.59   357.8 2310.79   372.5  2310.6   377.7 2313.25   402.3 2314.05
   414.9 2310.52   459.1 2309.33   479.3 2310.52   486.4 2315.25   492.2 2315.57
   683.9 2313.61     701 2313.48   761.1 2314.44   878.4 2313.39  1629.4 2311.54
  1685.8 2314.04    1846 2311.88  1876.9 2314.65  1890.5 2319.26  1912.1 2319.29
  1922.4 2323.08  1948.1 2344.05  1990.6 2370.32  2030.4 2390.44  2080.3 2411.16
#Mann= 13 ,-1,0
       0      .1       0   191.5    .016       0   197.9      .1       0
   357.8    .045       0   372.5      .1       0   414.9     .04       0
   479.3      .1       0   683.9    .045       0     701     .05       0
   761.1     .07       0   878.4     .05       0  1890.5    .016       0
  1912.1      .1       0
#Block Obstruct= 2 , 0
           56.39 2383.45
Bank Sta=414.9,479.3
XS Rating Curve= 0 ,0
Exp/Cntr(USF)=0,0
Exp/Cntr=0.3,0.1

Type RM Length L Ch R = 1 ,58445   ,795.2,846.6,301.3
Node Name=U
XS GIS Cut Line= 5
2263026.82546052425154.8851382942262862.21857238425250.636857542
2262723.43237257425437.8368479812262714.82547646425528.209257159
2262120.18419374426755.383285904
#Sta/Elev= 30
       0 2371.24    35.5 2364.61    76.8 2347.07    95.6 2335.63   123.9 2321.96
   146.5 2317.88   178.9 2317.16   248.4 2318.02   253.3 2317.73   258.3 2314.28
   263.3 2310.78   268.3 2310.68   293.2 2313.75   430.8 2313.94   438.9 2310.08
   462.5 2309.03   485.7 2310.11   499.1 2314.47   684.2 2311.39   906.5 2312.81
  1244.3 2309.69  1446.8 2312.27  1696.6 2310.71  1719.9 2313.38  1732.5 2319.11
  1755.4  2318.7  1765.5 2323.04  1777.7 2335.19  1804.5 2356.46  1877.9 2394.89
#Mann= 8 ,-1,0
       0      .1       0   146.5    .016       0   178.9     .05       0
   258.3      .1       0   438.9     .04       0   485.7     .05       0
  1732.5    .016       0  1755.4      .1       0
#Block Obstruct= 1 ,-1
   17.33  109.74 2388.65
Bank Sta=438.9,485.7
XS Rating Curve= 0 ,0
Exp/Cntr(USF)=0,0
Exp/Cntr=0.3,0.1

Type RM Length L Ch R = 1 ,57598   ,412.2,775.4,659
XS GIS Cut Line= 3
2262004.85248181424910.3387058112262264.73386499425625.012509546
2261900.89992854426729.508388046
#Sta/Elev= 30
       0 2352.71    28.6 2347.41    45.4 2337.45    75.4 2337.02   100.9 2319.99
   113.7 2314.61   224.3  2311.7     242 2306.31   262.7 2305.73   304.4 2306.11
   320.1 2311.09     352 2312.55   403.1 2312.96   428.6 2308.25   458.4 2307.43
   505.3 2307.45   513.8 2311.34   560.6 2311.81  1391.4 2308.51  1410.5 2308.78
  1640.8 2310.17  1653.5 2311.76  1666.1 2317.98  1687.1 2317.84    1704  2329.3
  1716.6 2344.23  1741.9 2364.21  1758.7 2373.72  1826.1 2406.58  1923.3 2445.42
#Mann= 16 ,-1,0
       0     .03       0     140     .04       0     180    .016       0
     190     .04       0     240    .045       0     290     .04       0
     350      .1       0   458.4     .04       0   505.3      .1       0
  770.46     .05       0  1391.4    .045       0  1410.5     .05       0
 1600.46     .04       0 1670.46    .016       0 1700.46     .04       0
 1710.46      .1       0
#XS Ineff= 1 ,-1
   232.7   313.7 2309.68
Permanent Ineff=
       T
Bank Sta=458.4,505.3
XS Rating Curve= 0 ,0
Exp/Cntr(USF)=0,0
Exp/Cntr=0.3,0.1

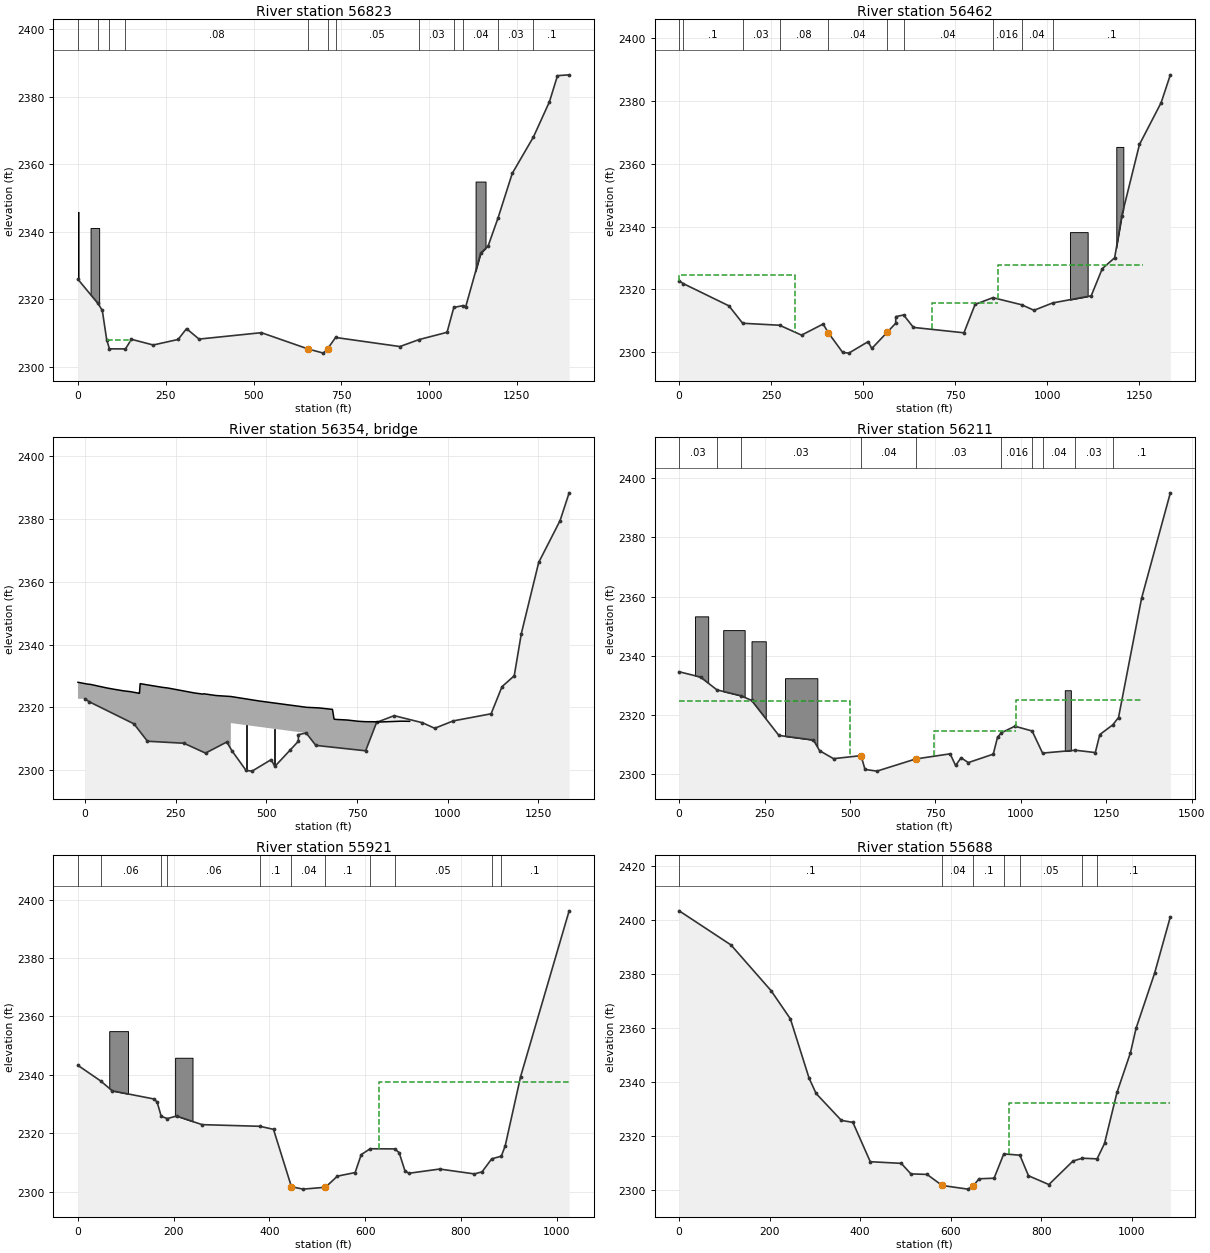
Type RM Length L Ch R = 1 ,56823   ,395.4,360.5,338.7
BEGIN DESCRIPTION:
structure xs 4
END DESCRIPTION:
XS GIS Cut Line= 4
 2261689.1251882425198.2677872672261770.11657157425496.657094395
2261305.48179332426119.0119349782261271.38015822426430.189355269
#Sta/Elev= 30
       0 2325.93    56.9 2318.77    69.3 2316.71    81.8 2308.03    89.6 2305.33
   135.3 2305.31   152.2 2308.16   214.4 2306.47   285.2 2308.11   309.2 2311.32
   344.8 2308.22   522.4 2310.12   656.52305.258   699.2 2304.06   711.1 2305.36
   733.7  2308.7   916.9 2306.01   971.2 2308.07  1051.2 2310.23  1070.4 2317.59
  1095.9 2318.14  1104.1 2317.71    1147 2333.68  1168.2 2335.82  1196.7 2344.21
  1236.9 2357.33  1297.3 2368.14  1342.9 2378.58  1365.7 2386.29  1398.9 2386.54
#Mann= 12 ,-1,0
       0     .03       0    56.9      .1       0    89.6    .045       0
   135.3     .08       0   656.5     .04       0   711.1     .08       0
   733.7     .05       0   971.2     .03       0  1070.4    .016       0
  1095.9     .04       0  1196.7     .03       0  1297.3      .1       0
#XS Ineff= 1 ,-1
    81.8   148.3 2308.03
Permanent Ineff=
       T
#Block Obstruct= 3 ,-1
       0    1.77 2345.93   35.85   60.35 2341.14 1132.43  1160.8 2354.91
Bank Sta=656.5,711.1
XS Rating Curve= 0 ,0
Exp/Cntr(USF)=0,0
Exp/Cntr=0.5,0.3

Type RM Length L Ch R = 1 ,56462   ,233.3,250.8,402.9
BEGIN DESCRIPTION:
Structure XS 3 - channel burned within banks
END DESCRIPTION:
XS GIS Cut Line= 3
2261603.80715989425235.7582723552261013.37997517425905.599639815
2261152.19640877426324.825269286
#Sta/Elev= 30
       0 2322.71    11.5  2321.8   135.2 2314.73   172.5 2309.18   272.8 2308.55
   332.5  2305.4   391.1 2308.94   405.52306.116  444.17 2299.89  460.81 2299.66
  513.48 2303.33  523.38 2301.14  565.06  2306.3  588.28 2309.18   588.4 2311.28
   609.8 2311.83   636.4 2307.86   773.7 2306.14     804  2315.2   852.4 2317.34
   930.4 2315.08   964.1 2313.32  1015.1 2315.67  1119.5 2317.94  1149.5 2326.59
  1183.2 2330.05  1202.8 2343.53  1250.6 2366.18  1309.5 2379.52  1334.5 2388.38
#Mann= 10 ,-1,0
       0     .03       0    11.5      .1       0   172.5     .03       0
   272.8     .08       0   405.5     .04       0  565.06     .03       0
   609.8     .04       0   852.4    .016       0   930.4     .04       0
  1015.1      .1       0
#XS Ineff= 3 ,-1
       0     314  2324.7     686  865.24  2315.6  865.24 1259.61 2327.64
Permanent Ineff=
       F       F       F
#Block Obstruct= 2 ,-1
 1061.68 1109.81 2338.23 1187.67 1206.73  2365.4
Bank Sta=405.5,565.06
XS Rating Curve= 0 ,0
Exp/Cntr(USF)=0,0
Exp/Cntr=0.5,0.3

Type RM Length L Ch R = 3 ,56354   ,,,
BEGIN DESCRIPTION:
Route 39/ Route 32
Bridge data: 54075KNA050
Width: 33' (measured on orthoimagery)
Railing height: 3.1
2 Rectangular Piers, each with width: 3'
Structure bounding sections incorporate channel data from survey.
Deck from Lidar with survey data incorporated.
END DESCRIPTION:
Bridge Culvert--1,0,-1,-1, 0
Deck Dist Width WeirC Skew NumUp NumDn MinLoCord MaxHiCord MaxSubmerge Is_Ogee
91,33,2.6,0, 30, 30, , , 0.98, 0, 0,0,,
     -19    7.79   15.45   58.07   79.38  106.99  126.26   149.5  150.48  152.33
  212.57  228.55  301.88  325.22   327.5  361.27  402.27  480.97  611.31  645.09
  682.33  686.72  692.05  722.58  753.71   773.2  805.58  812.98  872.21  894.92
 2327.98  2327.4 2327.31 2326.23 2325.78 2325.25 2324.98 2324.48 2324.47 2327.54
 2326.39 2326.16 2324.58 2324.21 2324.32 2323.76 2323.45 2322.01    2320 2319.82
 2319.34 2316.25 2316.14 2315.96 2315.55 2315.42 2315.39 2315.32 2315.58 2315.54
                                                                                
                                                 2314.98 2313.77 2311.78
                                                                                
     110  136.79  144.45  187.07  208.38  235.99  255.26   278.5  279.48  281.33
  341.57  357.55  430.88  454.22   456.5  490.27  531.27  609.97  740.31  774.09
  811.33  815.72  821.05  851.58  882.71   902.2  934.58  941.98 1001.21 1023.92
 2327.98  2327.4 2327.31 2326.23 2325.78 2325.25 2324.98 2324.48 2324.47 2327.54
 2326.39 2326.16 2324.58 2324.21 2324.32 2323.76 2323.45 2322.01    2320 2319.82
 2319.34 2316.25 2316.14 2315.96 2315.55 2315.42 2315.39 2315.32 2315.58 2315.54
                                                                                
                                                 2314.98 2313.77 2311.78
                                                                                
Pier Skew, UpSta & Num, DnSta & Num=  ,444.17, 2 ,565.62, 2 , 0 , 0 , 0 ,,
       3       3
 2299.89 2314.98
       3       3
 2301.16 2314.98
Pier Skew, UpSta & Num, DnSta & Num=  ,523.38, 2 ,645.94, 2 , 0 , 0 , 0 ,,
       3       3
 2301.14 2314.98
       3       3
 2301.75 2314.98
BR Coef=-1 ,-1 , 0 ,1.25, 0 ,,,0.8,0,2,0,
WSPro=,,,, 1 ,,,, 0 ,,,, 0 ,,,,-1 ,-1 ,-1 , 0 , 0 , 0 , 0 , 0
BR U #Sta/Elev= 30
       0 2322.71    11.5  2321.8   135.2 2314.73   172.5 2309.18   272.8 2308.55
   332.5  2305.4   391.1 2308.94   405.52306.116  444.17 2299.89  460.81 2299.66
  513.48 2303.33  523.38 2301.14  565.06  2306.3  588.28 2309.18   588.4 2311.28
   609.8 2311.83   636.4 2307.86   773.7 2306.14     804  2315.2   852.4 2317.34
   930.4 2315.08   964.1 2313.32  1015.1 2315.67  1119.5 2317.94  1149.5 2326.59
  1183.2 2330.05  1202.8 2343.53  1250.6 2366.18  1309.5 2379.52  1334.5 2388.38
BR U #Mann= 10
       0     .03    11.5      .1   172.5     .03   272.8     .08   405.5    .035
  565.06     .03   609.8     .04   852.4    .016   930.4     .04  1015.1      .1
BR D #Sta/Elev= 30
       0 2334.52    62.5 2332.73   110.5 2328.39   181.2 2326.39   211.8 2324.84
   291.8 2312.97     393 2311.41     411  2307.8   451.8  2305.1  532.36 2306.13
  543.84 2301.46  578.79 2300.88  692.02 2304.99     793 2306.74     809 2302.79
     825  2305.4   846.3 2303.77   919.3 2306.63   931.9  2312.4   943.3 2313.88
   982.5 2316.09  1033.1 2314.47  1063.6 2306.99  1159.5 2307.96    1218 2307.16
  1231.1 2313.26    1269 2316.54  1285.9 2319.03  1353.3 2359.36  1437.6 2395.12
BR D #Mann= 10
       0     .03   110.5     .04   181.2     .03  532.36    .035  692.02     .03
   943.3    .016  1033.1     .03  1063.6     .04  1159.5     .03    1269      .1
BC Design=,, 0 ,, 0 ,,,,,,
BC Use User HTab Curves=0
BC User HTab FreeFlow(D)= 0

Type RM Length L Ch R = 1 ,56211   ,406.1,290.2,36.3
BEGIN DESCRIPTION:
Structure XS 2 - channel burned within banks
END DESCRIPTION:
XS GIS Cut Line= 3
2261463.96914245425106.2786265832260873.54195773425776.119994043
2261046.18148543426297.491367684
#Sta/Elev= 30
       0 2334.52    62.5 2332.73   110.5 2328.39   181.2 2326.39   211.8 2324.84
   291.8 2312.97     393 2311.41     411  2307.8   451.8  2305.1  532.36 2306.13
  543.84 2301.46  578.79 2300.88  692.02 2304.99     793 2306.74     809 2302.79
     825  2305.4   846.3 2303.77   919.3 2306.63   931.9  2312.4   943.3 2313.88
   982.5 2316.09  1033.1 2314.47  1063.6 2306.99  1159.5 2307.96    1218 2307.16
  1231.1 2313.26    1269 2316.54  1285.9 2319.03  1353.3 2359.36  1437.6 2395.12
#Mann= 10 ,-1,0
       0     .03       0   110.5     .04       0   181.2     .03       0
  532.36     .04       0  692.02     .03       0   943.3    .016       0
  1033.1     .03       0  1063.6     .04       0  1159.5     .03       0
    1269      .1       0
#XS Ineff= 3 ,-1
       0     500  2324.7     745  987.04  2314.5  987.04 1353.01    2325
Permanent Ineff=
       F       F       F
#Block Obstruct= 5 ,-1
   46.29   84.89 2353.29  128.89  191.58 2348.63  211.66  253.36 2344.85
  309.73   404.4 2332.34 1128.67 1146.37 2328.27
Bank Sta=532.36,692.02
XS Rating Curve= 0 ,0
Exp/Cntr(USF)=0,0
Exp/Cntr=0.5,0.3

Type RM Length L Ch R = 1 ,55921   ,241.6,233.2,231.7
BEGIN DESCRIPTION:
xs 1
END DESCRIPTION:
XS GIS Cut Line= 3
2260650.93809625425277.9382704612260872.30888103425876.459281157
2260824.75515689426261.808425029
#Sta/Elev= 30
       0 2343.26    47.1 2337.97    71.7 2334.55   159.2 2331.75   165.4  2330.7
     174 2325.82   186.8 2325.07   205.9 2325.93   259.3 2322.99   380.2 2322.42
   408.6 2321.38  446.07 2301.75   470.4 2300.93   517.2 2301.57   542.1 2305.37
   579.2  2306.6   591.9 2312.74   610.6 2314.74   661.8 2314.69   671.1 2313.44
   683.2 2307.25   691.3 2306.35   755.8  2307.8   828.3 2306.14   844.4 2306.83
   864.6 2311.29   884.7  2312.2   892.8 2315.75     925 2339.43  1026.4 2396.13
#Mann= 11 ,-1,0
       0      .1       0    47.1     .06       0     174    .016       0
   186.8     .06       0   380.2      .1       0  446.07     .04       0
   517.2      .1       0   610.6    .016       0   661.8     .05       0
   864.6    .016       0   884.7      .1       0
#XS Ineff= 2 , 0
                          630.08         2337.69
Permanent Ineff=
       F       F
#Block Obstruct= 2 ,-1
   65.31  104.62 2354.97     203  239.34 2345.87
Bank Sta=446.07,517.2
XS Rating Curve= 0 ,0
Exp/Cntr(USF)=0,0
Exp/Cntr=0.3,0.1

Type RM Length L Ch R = 1 ,55688   ,343.9,319,313.9
Node Name=T
XS GIS Cut Line= 3
2260389.41498273425250.0739377682260654.21766343 425951.88932634
2260581.50243348426279.194746158
#Sta/Elev= 30
       0 2403.52  114.48 2390.86  203.21 2373.88  245.77 2363.44  287.02 2341.48
  302.59 2335.77  358.41 2325.79  383.82 2325.06  422.29 2310.47   490.7 2309.86
  512.07 2305.95  547.76 2305.76 581.0982301.661  637.78  2300.3 649.3982301.403
  662.61 2304.13  695.91 2304.36  717.29 2313.37   752.9 2312.89  771.92 2305.26
  816.99    2302  870.25 2310.72  890.75 2311.76  923.53 2311.53  939.92 2317.24
  967.47 2336.16  997.28  2350.9 1009.58 2359.91 1050.55 2380.35  1085.4 2401.31
#Mann= 7 ,-1,0
       0      .1       0 581.098     .04       0 649.398      .1       0
  717.29    .016       0   752.9     .05       0  890.75    .016       0
  923.53      .1       0
#XS Ineff= 2 , 0
                          728.79         2332.11
Permanent Ineff=
       F       F
Bank Sta=581.098,649.398
XS Rating Curve= 0 ,0
Exp/Cntr(USF)=0,0
Exp/Cntr=0.3,0.1

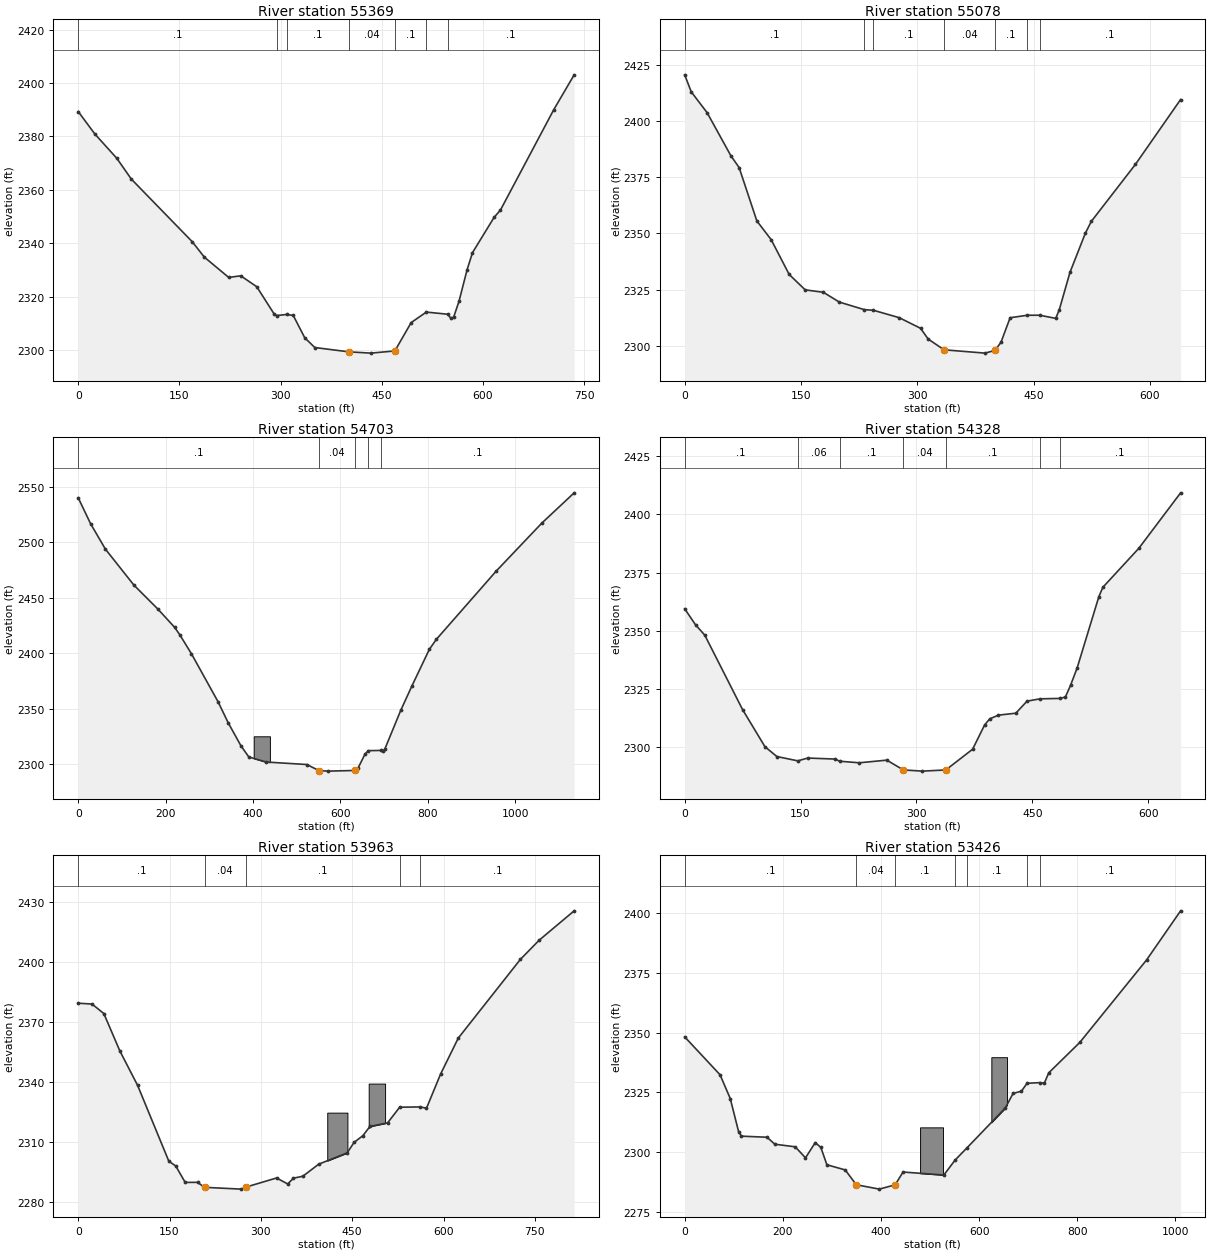
Type RM Length L Ch R = 1 ,55369   ,289.9,291.3,293.8
XS GIS Cut Line= 3
2260113.08907842425563.2606152862260368.89531861 426055.19569257
2260380.37380374426235.571887574
#Sta/Elev= 30
       0 2389.33    24.7 2380.91    57.1 2371.86    78.8 2364.01     169 2340.59
     187  2334.8   223.1 2327.21     241 2327.81   264.7 2323.72   290.7 2313.42
   294.4 2312.95   309.2 2313.33   318.8 2312.96   335.8 2304.62   350.7 2300.96
   401.1 2299.34   433.8 2298.86   469.4 2299.68   493.6  2310.3   516.1 2314.23
   547.7 2313.43   552.2 2311.98   556.5 2312.28   564.5 2318.27   576.5  2330.1
   584.5 2336.49   616.6 2349.73   625.9 2352.42   704.8 2389.95   735.2 2403.08
#Mann= 7 ,-1,0
       0      .1       0   294.4    .016       0   309.2      .1       0
   401.1     .04       0   469.4      .1       0   516.1    .016       0
   547.7      .1       0
Bank Sta=401.1,469.4
XS Rating Curve= 0 ,0
Exp/Cntr(USF)=0,0
Exp/Cntr=0.3,0.1

Type RM Length L Ch R = 1 ,55078   ,388.9,375,364.2
XS GIS Cut Line= 2
2259885.78396952425764.0215492212260199.16483357426321.547970143
#Sta/Elev= 30
       0 2420.54     8.5 2412.96    28.9 2403.72    59.6 2384.53    70.2 2379.29
    93.1 2355.53   111.5 2347.23   134.8 2331.72   155.4 2324.88   178.9 2323.79
   199.4 2319.44   231.7 2316.07   243.5 2315.79   276.6 2312.51   304.2 2307.78
     314    2303   334.5 2298.21   387.4 2296.73   400.5 2297.98     408 2301.63
   419.7 2312.47   441.8 2313.58   457.9 2313.59   478.5 2312.19   483.1    2316
   496.9 2332.65   516.7 2350.05   524.4 2355.32   581.3  2380.7   639.6 2409.56
#Mann= 7 ,-1,0
       0      .1       0   231.7    .016       0   243.5      .1       0
   334.5     .04       0   400.5      .1       0   441.8    .016       0
   457.9      .1       0
Bank Sta=334.5,400.5
XS Rating Curve= 0 ,0
Exp/Cntr(USF)=0,0
Exp/Cntr=0.3,0.1

Type RM Length L Ch R = 1 ,54703   ,329.8,374.3,383.8
XS GIS Cut Line= 2
2259392.87476686425912.6296016822260170.91471032426738.795727212
#Sta/Elev= 30
       0 2540.05    28.2 2516.78    62.1 2493.86   127.3 2461.44   182.1 2439.85
   220.6 2423.33   232.4 2416.64     259 2399.58   319.9 2356.33   343.2 2337.33
   372.4 2316.55   390.4  2306.5     430 2301.93   523.4 2299.68   550.52294.254
   571.5 2293.73   633.7 2294.32   640.8 2296.84   656.4 2309.15   664.1 2312.16
   693.1 2312.38   698.6 2311.81   701.7 2313.67   738.4 2348.79   763.3  2370.2
   803.5 2403.45   819.4 2412.41   956.3 2473.89    1061 2517.27  1134.9 2544.52
#Mann= 5 ,-1,0
       0      .1       0   550.5     .04       0   633.7      .1       0
   664.1    .016       0   693.1      .1       0
#Block Obstruct= 1 ,-1
  401.62  438.64 2325.13
Bank Sta=550.5,633.7
XS Rating Curve= 0 ,0
Exp/Cntr(USF)=0,0
Exp/Cntr=0.3,0.1

Type RM Length L Ch R = 1 ,54328   ,400.4,365,334.7
XS GIS Cut Line= 3
2259364.69718396426277.8204077182259539.60743366426638.572797727
2259705.40777452426813.483047428
#Sta/Elev= 30
       0 2359.54    14.1 2352.63      26 2348.22    74.9 2316.29   103.9 2300.34
   119.3 2296.13   146.4 2294.27   159.3 2295.47   194.9 2295.04   200.5 2294.11
     226 2293.44   261.6 2294.57     283 2290.38   307.5 2289.86     338 2290.36
   372.7 2299.27   388.3 2309.74   394.9  2312.3     406 2313.88   428.6 2314.72
   443.1 2319.89   459.8 2320.88   485.2 2321.06   492.7 2321.63   499.4 2326.66
   507.9 2334.06   536.1 2364.75   541.3 2368.77   587.8 2385.48   641.9 2409.29
#Mann= 7 ,-1,0
       0      .1       0   146.4     .06       0   200.5      .1       0
     283     .04       0     338      .1       0   459.8    .016       0
   485.2      .1       0
Bank Sta=283,338
XS Rating Curve= 0 ,0
Exp/Cntr(USF)=0,0
Exp/Cntr=0.3,0.1

Type RM Length L Ch R = 1 ,53963   ,544.1,537,525
Node Name=S
XS GIS Cut Line= 4
 2259041.7691772426491.4528388392259076.82406466426613.065052979
2259231.69251491426762.4675579322259573.94865106427088.394374448
#Sta/Elev= 30
       0 2379.61    22.7 2379.19    42.1 2374.43    68.4 2355.74    97.5 2338.55
   148.8 2300.64   160.1 2298.25   175.7 2290.03   195.9 2290.06   207.4 2287.57
   267.6 2286.67   275.7 2287.71   325.7 2292.24     344 2289.26   353.5 2292.15
   368.9 2293.11   394.9 2299.14   441.8 2304.81   452.9 2310.01   467.5  2313.4
   479.1 2318.01   508.1 2319.81   527.9 2327.62   561.9 2327.76   571.9  2327.1
   595.1 2344.21   624.1 2362.16     726 2401.48   757.1 2411.15   814.4 2425.79
#Mann= 5 ,-1,0
       0      .1       0   207.4     .04       0   275.7      .1       0
   527.9    .016       0   561.9      .1       0
#Block Obstruct= 2 ,-1
  408.95  442.07 2324.91     477  503.94 2339.43
Bank Sta=207.4,275.7
XS Rating Curve= 0 ,0
Exp/Cntr(USF)=0,0
Exp/Cntr=0.3,0.1

Type RM Length L Ch R = 1 ,53426   ,481.5,510.2,507.4
XS GIS Cut Line= 3
2258555.63920445426874.8130030132259101.88534126427333.453627315
2259372.43177694427457.131997913
#Sta/Elev= 30
       0  2348.2    72.1 2332.32    92.9 2322.34   109.9 2308.48   115.6  2306.6
   167.8 2306.15   183.8 2303.22   225.3 2302.14   246.2 2297.51   266.1  2303.9
   277.5 2301.88   289.8 2294.62   327.2 2292.45   349.72286.246   396.7 2284.41
     429 2286.23     445 2291.57   528.2 2290.32   551.1 2296.58   575.2 2301.68
   653.6 2318.46   669.2  2324.5   686.3 2325.44   697.7 2328.75   723.8 2329.03
   732.9 2328.76   741.9 2333.12   805.3 2345.88   941.2 2380.39  1010.7    2401
#Mann= 7 ,-1,0
       0      .1       0   349.7     .04       0     429      .1       0
   551.1    .016       0   575.2      .1       0   697.7    .016       0
   723.8      .1       0
#Block Obstruct= 2 ,-1
  479.72  526.46 2310.29  624.96  656.99 2339.68
Bank Sta=349.7,429
XS Rating Curve= 0 ,0
Exp/Cntr(USF)=0,0
Exp/Cntr=0.3,0.1

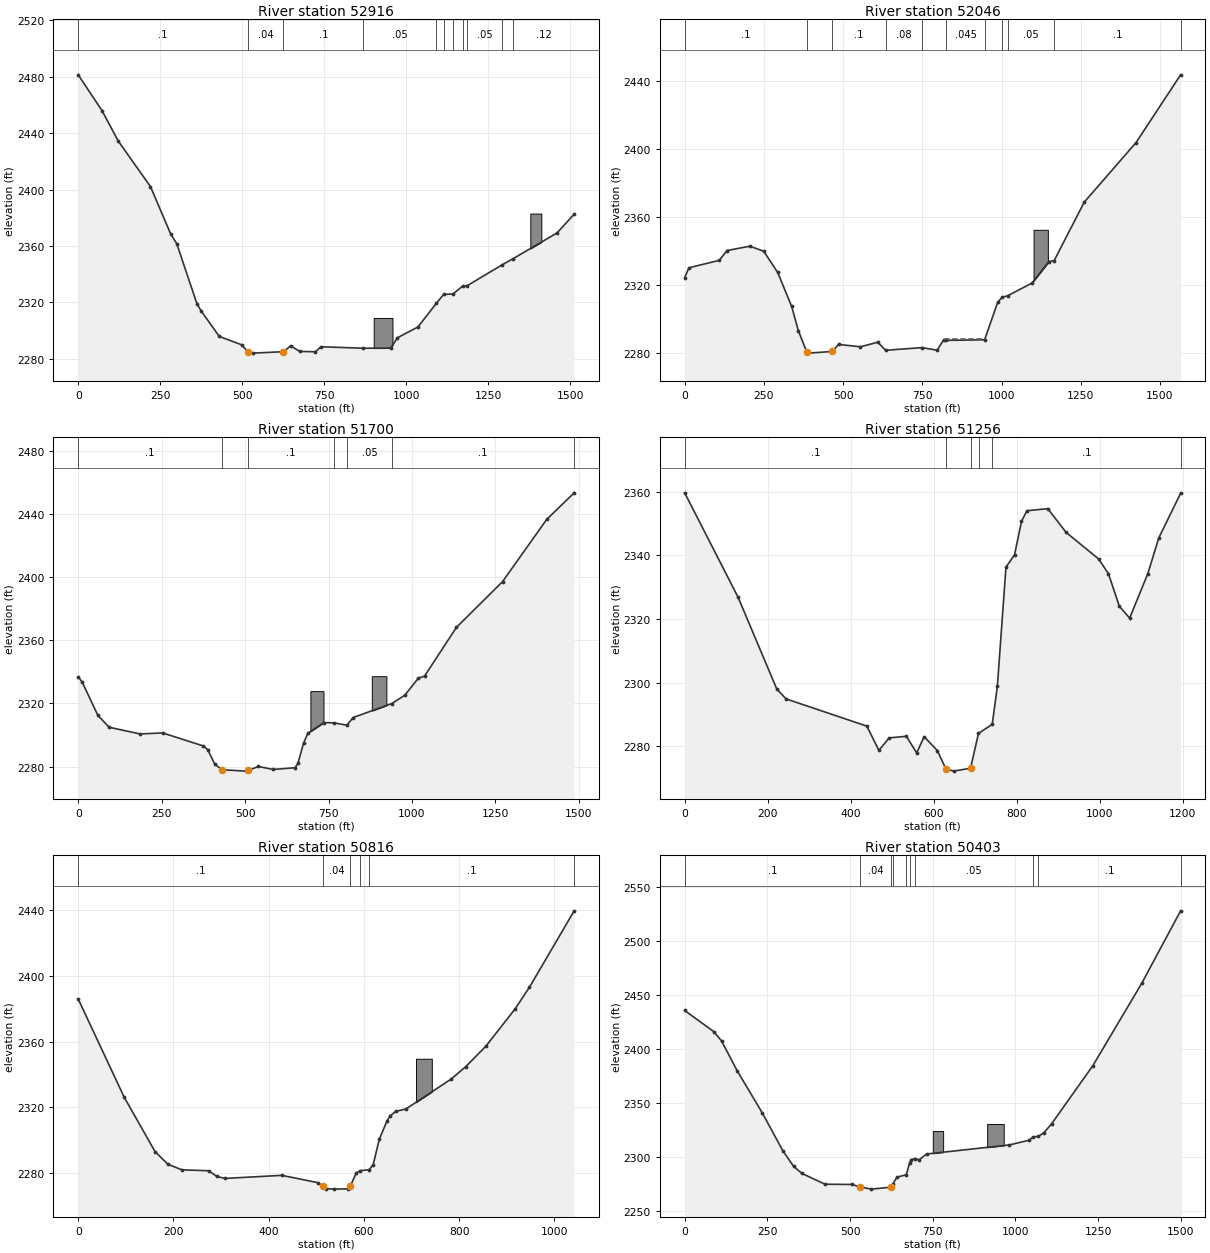
Type RM Length L Ch R = 1 ,52916   ,898.9,870.4,581.4
XS GIS Cut Line= 4
2258014.54633308427065.483824352 2258339.2020559427225.235053041
2258504.10655003427531.8543468162259222.98707914427887.429662287
#Sta/Elev= 30
       0  2481.4    72.7 2455.96   122.2 2434.39   220.3 2402.17   281.8 2368.64
   300.5  2361.6   361.8 2319.18   374.3 2314.17   429.9 2295.93   498.4 2289.96
   517.92284.871   532.8 2284.07   625.7 2285.09   647.9 2289.25   675.2 2285.29
   723.4 2285.03     740 2288.59   869.3 2287.54   952.9 2287.68   973.3 2294.96
  1035.8 2302.64  1091.9 2319.37  1114.1 2325.67  1142.9 2326.07  1173.1 2331.79
  1185.8 2331.88  1293.2 2346.78  1325.3 2350.95  1459.8 2369.28    1512  2382.6
#Mann= 11 ,-1,0
       0      .1       0   517.9     .04       0   625.7      .1       0
   869.3     .05       0  1091.9     .04       0  1114.1    .016       0
  1142.9     .05       0  1173.1    .016       0  1185.8     .05       0
  1293.2      .1       0  1325.3     .12       0
#Block Obstruct= 2 ,-1
  900.86  958.14 2309.02 1378.34 1411.99 2383.03
Bank Sta=517.9,625.7
XS Rating Curve= 0 ,0
Exp/Cntr(USF)=0,0
Exp/Cntr=0.3,0.1

Type RM Length L Ch R = 1 ,52046   ,354,345.5,204.1
XS GIS Cut Line= 3
2257622.89815952428047.1808909762258163.99103089428021.414563768
2259114.76850486428400.179573726
#Sta/Elev= 30
       0 2324.18    13.3 2330.04   109.4 2334.44   133.4  2340.2   205.7 2342.78
   249.6 2339.78   293.6 2327.26   337.7 2307.24   358.6 2293.01   384.92280.587
   389.7 2279.71   465.7 2280.68   485.8 2284.84   554.8 2283.44   609.4 2286.15
     634 2281.38   748.6 2282.96   797.2 2281.42   817.5 2287.69   826.1 2287.22
   946.6 2287.57   988.1  2309.8  1002.6  2312.7  1018.9  2313.5  1095.9    2321
    1149 2333.62  1166.2  2334.3    1261 2368.73  1424.6  2403.9  1565.2 2443.83
#Mann= 11 ,-1,0
       0      .1       0   384.9     .04       0   465.7      .1       0
     634     .08       0   748.6      .1       0   826.1    .045       0
   946.6      .1       0  1002.6    .016       0  1018.9     .05       0
  1166.2      .1       0  1565.2     .12       0
#XS Ineff= 1 ,-1
   821.8   948.1 2287.81
Permanent Ineff=
       T
#Block Obstruct= 1 ,-1
 1101.05 1146.13 2352.45
Bank Sta=384.9,465.7
XS Rating Curve= 0 ,0
Exp/Cntr(USF)=0,0
Exp/Cntr=0.3,0.1

Type RM Length L Ch R = 1 ,51700   ,393.9,444.3,484.6
XS GIS Cut Line= 3
2257716.47942476428495.8965232772258358.16185236428279.328703963
2259104.11767444428592.148887416
#Sta/Elev= 30
       0  2336.8    12.3  2333.3    58.7 2312.47    92.6 2304.87   185.4 2300.62
     253 2301.27   375.4 2292.98   388.1 2290.65   409.1 2281.59   430.12277.992
   502.1 2277.09   510.1  2277.6   540.1 2280.03   583.9 2278.16   649.8 2279.23
   658.3 2281.93   675.1 2294.69   688.1  2301.1   735.8 2307.79   766.2 2307.65
   805.2 2306.17   823.8 2311.02   939.7 2319.87   978.7 2325.14  1019.4 2335.97
  1037.7 2337.19  1133.2 2368.04  1271.6 2397.06  1403.8  2436.4  1486.1 2453.25
#Mann= 7 ,-1,0
       0      .1       0   430.1     .04       0   510.1      .1       0
   766.2    .016       0   805.2     .05       0   939.7      .1       0
  1486.1      .1       0
#Block Obstruct= 2 ,-1
  695.73     735 2327.71  879.72  923.52 2337.18
Bank Sta=430.1,510.1
XS Rating Curve= 0 ,0
Exp/Cntr(USF)=0,0
Exp/Cntr=0.3,0.1

Type RM Length L Ch R = 1 ,51256   ,430.4,439.8,445.2
Node Name=R
XS GIS Cut Line= 2
 2257595.8728374428598.0150879892258750.90120708428902.814241097
#Sta/Elev= 30
       0 2359.67   128.6 2326.84   222.1  2297.9   244.4 2294.86   438.8  2286.3
   467.8 2278.68   492.6  2282.6     534 2283.11   558.8 2277.88   576.8 2282.99
   608.4 2278.63   629.22272.863   647.7 2272.15   688.62273.067   707.7 2284.02
   740.8 2286.85   753.2 2298.83   773.9 2336.28   794.6  2340.2   811.3 2350.68
   824.4 2354.03   874.6  2354.7   918.7 2347.24   997.3 2338.84  1020.8 2334.21
    1047    2324  1071.8 2320.26  1115.7 2334.29  1142.1 2345.52  1194.6 2359.53
#Mann= 6 ,-1,0
       0      .1       0   629.2     .04       0   688.6     .03       0
     710    .016       0     740      .1       0  1194.6      .1       0
Bank Sta=629.2,688.6
XS Rating Curve= 0 ,0
Exp/Cntr(USF)=0,0
Exp/Cntr=0.3,0.1

Type RM Length L Ch R = 1 ,50816   ,389.8,412.9,419.1
XS GIS Cut Line= 2
 2257598.6240029428981.0249784842258563.00715516429374.824876073
#Sta/Elev= 30
       0 2386.01    96.7 2326.15   161.5 2293.04   188.4 2285.39   217.7 2282.01
   273.9 2281.44   291.2 2277.96   308.4 2276.77   427.7 2278.64   502.9 2274.22
   514.12271.974   520.2 2270.57   537.4 2270.25   565.8 2270.44  571.46 2272.01
   584.2 2280.17   592.9  2281.5   610.9 2282.09   619.5 2285.02   632.5 2300.75
   648.6 2311.75   654.8 2314.74   667.1 2317.63   688.2 2319.04   783.4 2337.28
     814 2344.84     857 2357.52   917.7 2380.03   947.9 2393.22  1041.7 2439.72
#Mann= 6 ,-1,0
       0      .1       0   514.1     .04       0  571.46      .1       0
   592.9    .016       0   610.9      .1       0  1041.7     .12       0
#Block Obstruct= 1 ,-1
  709.48   742.7 2349.67
Bank Sta=514.1,571.46
XS Rating Curve= 0 ,0
Exp/Cntr(USF)=0,0
Exp/Cntr=0.3,0.1

Type RM Length L Ch R = 1 ,50403   ,316.1,423.4,483.5
XS GIS Cut Line= 3
2257385.84794921429222.1254116612258212.94705258429745.181853983
2258733.42686218429727.145424938
#Sta/Elev= 30
       0 2435.72      88 2416.16   111.6 2407.47   158.9  2379.8   234.7 2340.88
   296.7  2305.9   329.3 2291.41   354.7 2284.79   424.3 2274.87   505.5 2274.64
   530.82272.309   564.1 2270.32   624.3 2272.14   630.1 2275.51   641.7 2281.44
   670.1  2283.6     680 2294.61   685.2 2297.66   696.8 2298.54   708.4 2297.36
   731.5 2302.84     982 2311.26  1041.9 2315.66  1053.9 2318.75    1069 2319.08
  1085.9 2322.47  1109.4 2330.84    1234  2384.6  1382.1 2461.02  1499.4    2528
#Mann= 10 ,-1,0
       0      .1       0   530.8     .04       0   624.3      .1       0
   630.1    .016       0   670.1      .1       0     680    .016       0
   696.8     .05       0  1053.9    .016       0    1069      .1       0
  1499.4      .1       0
#Block Obstruct= 2 ,-1
   750.2  781.44 2324.08  914.52  964.58 2330.64
Bank Sta=530.8,624.3
XS Rating Curve= 0 ,0
Exp/Cntr(USF)=0,0
Exp/Cntr=0.3,0.1

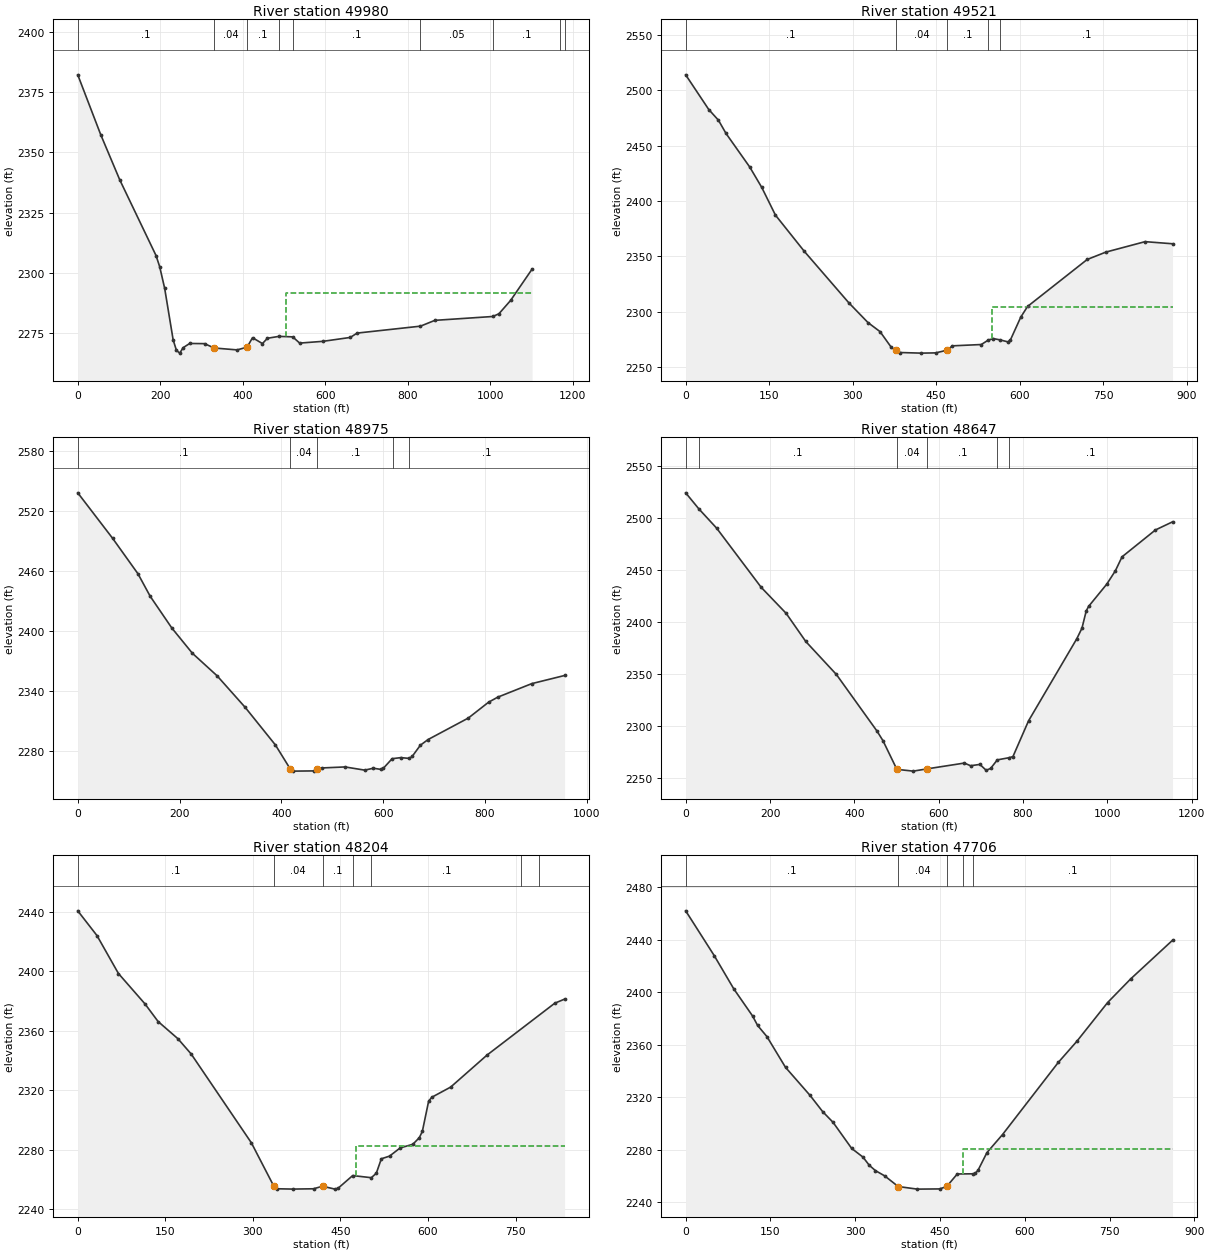
Type RM Length L Ch R = 1 ,49980   ,484.6,458.4,421
XS GIS Cut Line= 5
2257447.05476163 429371.651651162257512.35617772429587.184621193
2257527.85041402429858.9498943212257613.28120738430111.310622535
2257914.80535023430262.448922478
#Sta/Elev= 30
       0 2382.17    55.9 2357.25   101.9 2338.58   189.7 2307.24   198.5 2302.64
   210.6 2293.66   231.2 2272.26   239.2  2267.9   247.2 2266.78   255.3 2269.03
   271.3 2270.79   307.3 2270.71   330.72268.904   386.1 2268.12   410.42269.253
   423.5 2273.17   447.6 2270.74   459.6 2272.94   487.6 2273.73   520.9 2273.52
   537.8 2270.94   594.1 2271.67   660.3 2273.28   677.1 2275.09   830.5 2277.96
   865.5 2280.37  1005.8 2281.97  1020.7  2283.1    1049 2288.63  1101.1 2301.63
#Mann= 9 ,-1,0
       0      .1       0   330.7     .04       0   410.4      .1       0
   487.6    .016       0   520.9      .1       0   830.5     .05       0
  1005.8      .1       0 1169.87     .05       0 1179.87      .1       0
#XS Ineff= 2 , 0
                          504.34         2291.66
Permanent Ineff=
       F       F
Bank Sta=330.7,410.4
XS Rating Curve= 0 ,0
Exp/Cntr(USF)=0,0
Exp/Cntr=0.3,0.1

Type RM Length L Ch R = 1 ,49521   ,567.1,546.3,501.8
XS GIS Cut Line= 2
2256907.63802433429310.9017083062257243.63138493430118.158483777
#Sta/Elev= 30
       0 2514.14    41.5 2482.75    58.8 2473.14    72.5  2461.1   115.1 2430.74
   136.7 2412.29   161.2 2387.32   213.2 2354.48   292.8 2308.15   327.4 2290.16
   349.1 2281.96   369.3 2267.75     3772264.982   384.6 2263.09   422.7 2262.53
   448.8 2262.75   469.8  2265.2   479.1 2269.12     531 2270.31   543.6 2274.38
   552.7 2275.66   565.1 2274.45   578.7 2272.72     583 2274.21   601.8 2295.04
     614 2304.72   721.1 2347.19   754.7 2353.87   825.1 2363.31   874.4  2361.4
#Mann= 5 ,-1,0
       0      .1       0     377     .04       0   469.8      .1       0
   543.6    .016       0   565.1      .1       0
#XS Ineff= 2 , 0
                          550.99         2304.65
Permanent Ineff=
       F       F
Bank Sta=377,469.8
XS Rating Curve= 0 ,0
Exp/Cntr(USF)=0,0
Exp/Cntr=0.3,0.1

Type RM Length L Ch R = 1 ,48975   ,323,327.9,334.4
Node Name=Q
XS GIS Cut Line= 2
2256322.92230588429721.0754212482257012.36322763430384.335042175
#Sta/Elev= 30
       0  2537.8    68.3  2492.5   118.3 2456.97   142.4 2434.43   184.8 2402.83
   225.2  2377.6   273.7 2355.13   329.2 2323.43   388.5 2285.93   417.82261.833
   423.6 2259.87   464.9  2260.1   470.6 2261.68     479 2263.03   525.2 2264.05
   563.9 2260.87   580.9 2262.77     595 2261.64   600.7 2262.84   617.8  2272.3
   634.8 2273.35   651.6 2272.58   657.3 2274.65   673.3 2285.78   688.4 2291.42
   767.5 2312.88   807.2 2328.67   825.2 2333.72   892.1 2347.24   956.7 2355.39
#Mann= 5 ,-1,0
       0      .1       0   417.8     .04       0   470.6      .1       0
     620    .016       0   651.6      .1       0
Bank Sta=417.8,470.6
XS Rating Curve= 0 ,0
Exp/Cntr(USF)=0,0
Exp/Cntr=0.3,0.1

Type RM Length L Ch R = 1 ,48647   ,447.3,443.5,431.3
XS GIS Cut Line= 2
2256051.80611427429841.519005856 2256805.7829667430715.811313456
#Sta/Elev= 30
       0 2524.19    31.2 2508.76    73.5 2490.14   179.1 2433.17   238.3 2408.13
   284.8 2381.05   357.4 2349.28   453.8 2294.72     468 2285.42   500.82257.936
   539.6 2256.22   572.9 2258.43   660.8 2263.98   675.6 2261.42   697.7 2262.68
   712.6 2257.01   723.2 2258.88     739 2267.05   766.2  2269.1     776 2270.17
     813  2304.6   927.4 2383.63   939.7 2393.84   949.9 2410.56   955.6 2414.91
   998.9 2436.44    1019 2449.17  1034.8 2462.58    1114 2488.45  1154.5 2496.25
#Mann= 6 ,-1,0
       0     .12       0    31.2      .1       0   500.8     .04       0
   572.9      .1       0     739    .016       0   766.2      .1       0
Bank Sta=500.8,572.9
XS Rating Curve= 0 ,0
Exp/Cntr(USF)=0,0
Exp/Cntr=0.3,0.1

Type RM Length L Ch R = 1 ,48204   ,497.6,498.1,499.2
XS GIS Cut Line= 2
2255816.75048991430310.1546898352256432.01105932430873.052657596
#Sta/Elev= 30
       0  2440.5    32.9 2423.88    69.7 2398.37     115 2378.04   137.6 2366.13
   171.6 2354.55   194.3 2344.28   297.4  2284.6   335.4 2255.79   340.8 2253.75
   367.9 2253.53   403.8 2253.73   419.3 2255.45   440.6  2253.5   446.2 2254.19
   470.9 2262.61   502.9 2261.18   511.4 2264.21     520 2273.89     534 2275.68
   552.2 2281.18   573.9 2283.63     585 2288.05   590.2 2292.27     601 2312.63
   606.4 2315.23   638.8 2322.09     701 2343.57   817.1 2378.44   833.9 2381.18
#Mann= 7 ,-1,0
       0      .1       0   335.4     .04       0   419.3      .1       0
   470.9    .016       0   502.9      .1       0     760     .12       0
     790      .1       0
#XS Ineff= 2 , 0
                          477.18         2282.66
Permanent Ineff=
       F       F
Bank Sta=335.4,419.3
XS Rating Curve= 0 ,0
Exp/Cntr(USF)=0,0
Exp/Cntr=0.3,0.1

Type RM Length L Ch R = 1 ,47706   ,462.2,493.4,501.2
XS GIS Cut Line= 2
2255463.30292876430654.8751507122256091.65414858431243.954419298
#Sta/Elev= 30
       0 2462.18    50.4 2428.12    85.2 2402.64   118.3 2382.08   127.3  2374.8
   143.7 2366.35   176.6 2342.91   219.8 2321.64   242.4 2309.13   260.7 2301.01
   293.7 2281.09   313.7 2274.48   324.7  2268.3   335.7  2264.2   352.1 2260.18
     3762252.064   409.8 2250.09   449.4 2250.25   461.8  2252.1   480.5 2261.64
   508.8 2261.77   512.2 2262.03   517.3 2264.53     533 2277.95   560.5 2291.65
   659.1 2346.61     692 2362.72   746.5  2392.3   787.1 2410.23   861.3 2439.75
#Mann= 5 ,-1,0
       0      .1       0     376     .04       0   461.8      .1       0
     490    .016       0   508.8      .1       0
#XS Ineff= 2 , 0
                           490.7         2280.46
Permanent Ineff=
       F       F
Bank Sta=376,461.8
XS Rating Curve= 0 ,0
Exp/Cntr(USF)=0,0
Exp/Cntr=0.3,0.1