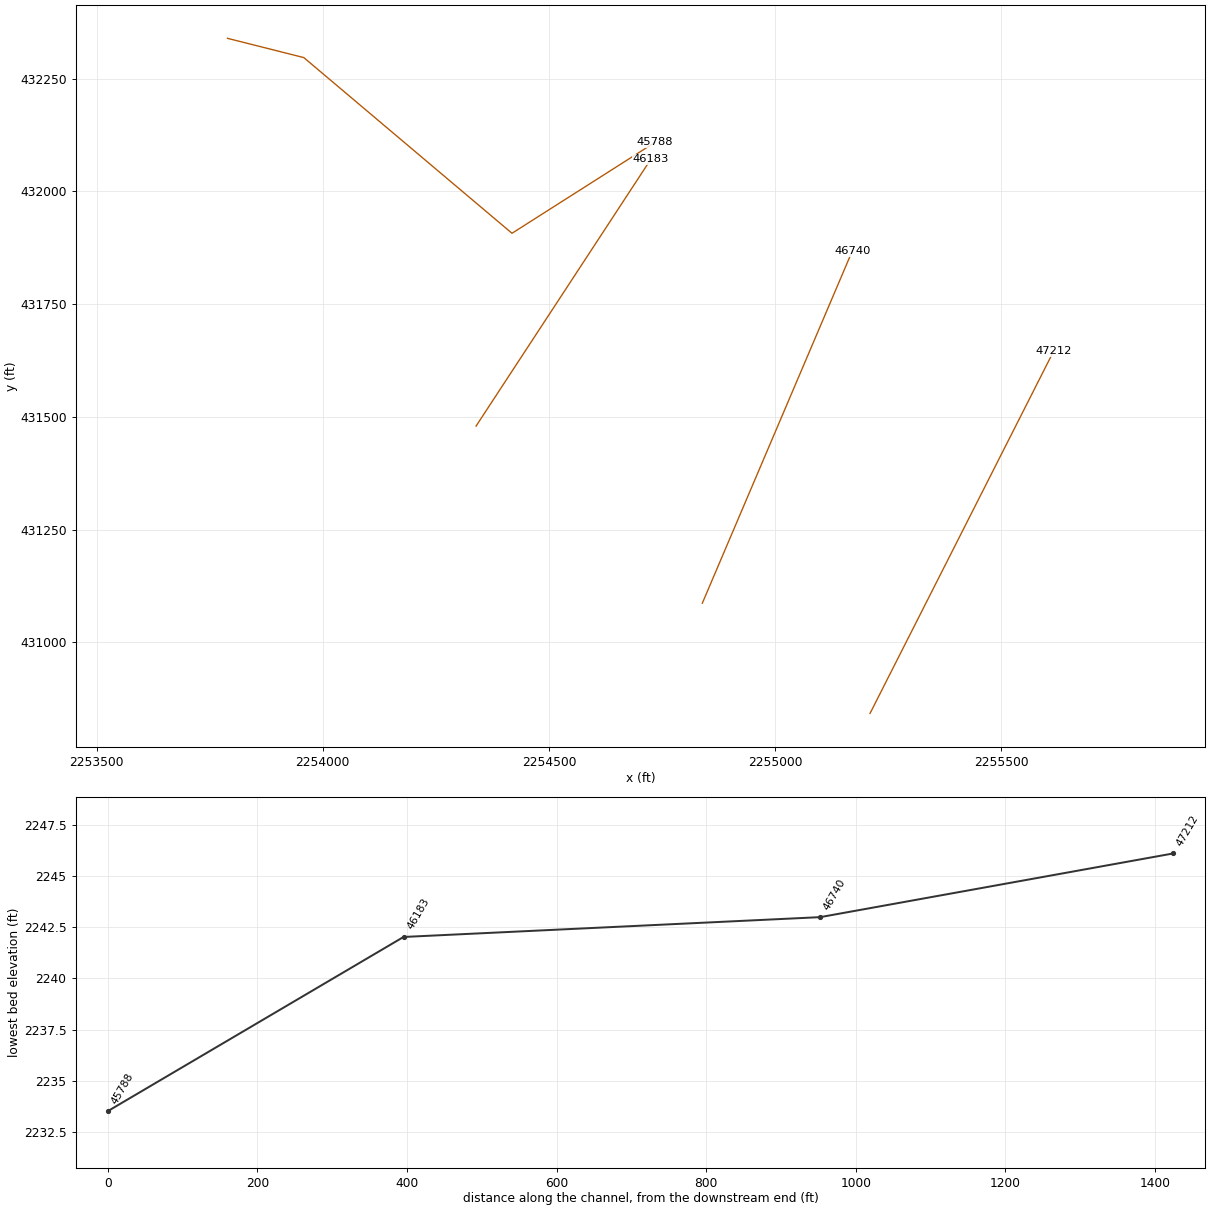
HEC-RAS study KNAPPCK.prj: KNAPPCK

--- KNAPPCK.g01 (geometry) --- (continued)

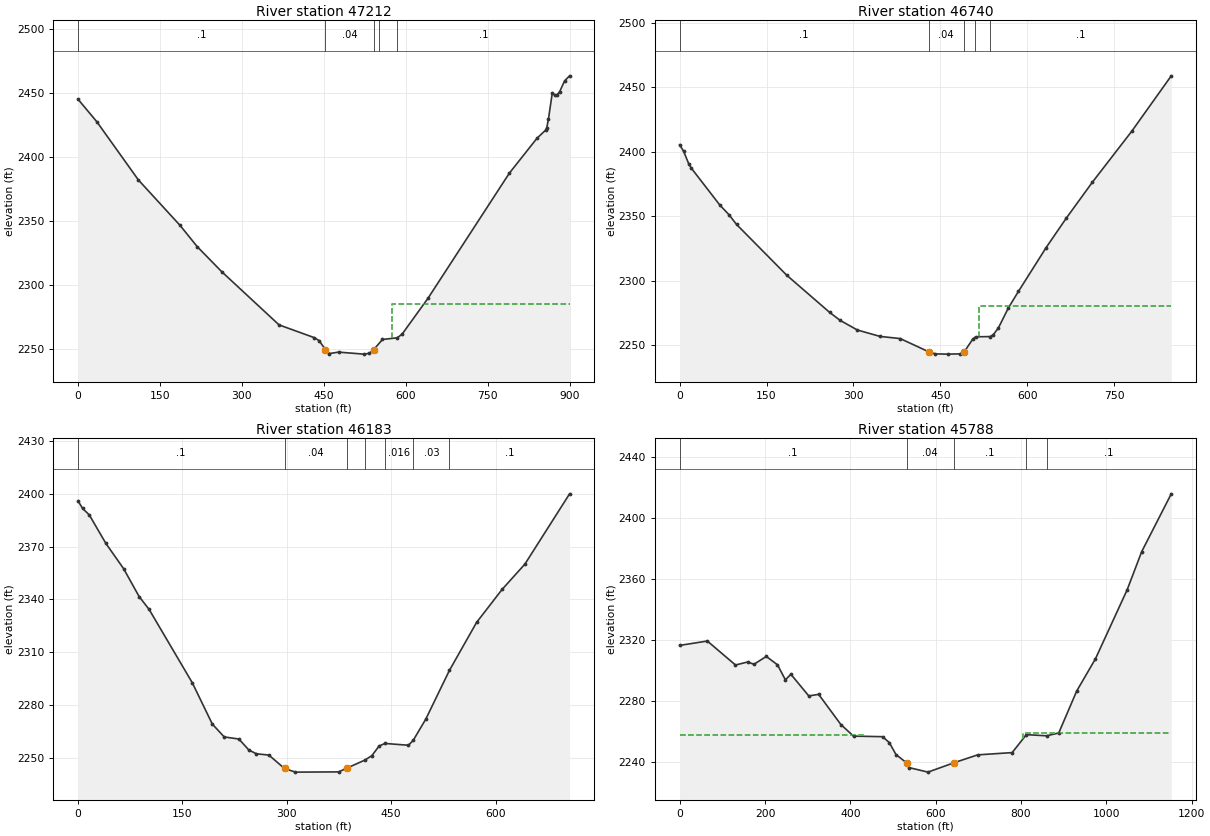
Type RM Length L Ch R = 1 ,47212   ,468.2,472.3,475.9
XS GIS Cut Line= 2
2255210.21702077430842.5078066322255616.02718358431645.401031965
#Sta/Elev= 30
       0 2445.21    34.4 2427.65   110.6 2382.12   186.8 2346.65   218.1  2330.1
   262.9 2310.55   367.9 2268.96   432.2 2259.02   441.1 2256.73   452.82249.708
   460.1 2246.56   476.8  2247.7   522.9 2246.12   533.4 2246.75   540.8 2249.48
   557.2 2257.56     584 2258.88   592.9  2261.6   640.6 2289.82   789.4 2387.48
     840 2414.75   855.6    2421   857.9 2423.02   860.9 2429.64     868 2450.26
   872.5 2448.23     877 2448.79   881.4 2451.08   890.4  2459.5   899.6 2463.48
#Mann= 5 ,-1,0
       0      .1       0   452.8     .04       0   540.8      .1       0
     550    .016       0     584      .1       0
#XS Ineff= 2 , 0
                          575.21         2285.55
Permanent Ineff=
       F       F
Bank Sta=452.8,540.8
XS Rating Curve= 0 ,0
Exp/Cntr(USF)=0,0
Exp/Cntr=0.3,0.1

Type RM Length L Ch R = 1 ,46740   ,566.1,556.8,546.5
Node Name=P
XS GIS Cut Line= 2
2254839.31525907431086.8666143422255170.94506953431867.942088987
#Sta/Elev= 30
       0 2405.44     6.9 2400.27    15.5 2390.81    19.9 2387.39    69.5 2358.56
    85.1 2351.17    98.1 2343.65     185 2304.14   258.9 2275.38     277 2269.19
   306.7 2261.72   345.8 2256.75   380.7 2255.06   429.72244.862   441.4 2243.16
   462.8    2243   484.4 2243.19   490.5 2244.35   505.7 2254.46   510.9 2256.43
   536.2 2256.63   541.4 2258.11   550.1 2263.24   567.4 2278.86   584.8 2291.67
   632.6 2325.67   667.3 2348.42   712.6 2376.49   780.1 2415.73   848.6 2458.91
#Mann= 5 ,-1,0
       0      .1       0   429.7     .04       0   490.5      .1       0
     510    .016       0   536.2      .1       0
#XS Ineff= 2 , 0
                          516.61         2280.49
Permanent Ineff=
       F       F
Bank Sta=429.7,490.5
XS Rating Curve= 0 ,0
Exp/Cntr(USF)=0,0
Exp/Cntr=0.3,0.1

Type RM Length L Ch R = 1 ,46183   ,484.3,395.5,163.9
BEGIN DESCRIPTION:
structure xs 4
c/e of 0.6/0.8 used to fix drawdown
END DESCRIPTION:
XS GIS Cut Line= 2
 2254338.9731992431479.6313695682254725.20297137432070.962469034
#Sta/Elev= 30
       0  2395.9     6.6 2391.63    16.2 2387.93    40.1 2371.74    65.6 2357.39
    87.8 2341.65   102.2 2334.31   164.3 2292.66     193 2269.28   210.1 2261.99
   231.2  2260.8   245.5 2254.56   256.3 2252.44   274.2  2251.7   296.72244.108
   312.4 2242.03   374.5 2242.16   386.4 2244.32   412.4  2248.9   422.3 2251.42
   432.6 2256.83   441.1  2258.3   474.8 2257.27   481.7  2260.1   499.6 2272.03
   533.7 2299.78   572.7 2326.96   609.3 2345.65   642.1 2360.02   706.3 2399.89
#Mann= 7 ,-1,0
       0      .1       0   296.7     .04       0   386.4      .1       0
   412.4     .03       0   441.1    .016       0   481.7     .03       0
   533.7      .1       0
Bank Sta=296.7,386.4
XS Rating Curve= 0 ,0
Exp/Cntr(USF)=0,0
Exp/Cntr=0.7,0.5

Type RM Length L Ch R = 1 ,45788   ,197.5,191.3,266.6
BEGIN DESCRIPTION:
Structure XS 3- channel burned within banks
END DESCRIPTION:
XS GIS Cut Line= 5
2253789.35784802432339.4882170862253958.02798055432296.815850554
 2254418.4359038431907.1802838262254476.88370083431944.455979781
2254734.54353509432108.781243179
#Sta/Elev= 30
       0 2316.59    64.8 2319.47  130.81 2303.73  159.69 2305.75  173.98  2304.2
     203 2309.36   229.2 2303.89  247.73 2294.02  260.64 2297.67  302.56 2283.46
  325.68  2284.5  377.76 2264.71  407.36 2257.12  475.49 2256.74  491.21 2252.89
  506.93 2245.02  531.72  2239.6  538.05 2236.44  581.93  2233.5  642.03 2239.57
  698.36 2244.82   779.2 2246.31  812.41 2258.07  859.85 2257.33  888.32 2259.15
  930.48  2286.7  974.26 2307.74 1048.65 2353.03 1082.83 2378.12 1152.06 2415.99
#Mann= 5 ,-1,0
       0      .1       0  531.72     .04       0  642.03      .1       0
  812.41    .016       0  859.85      .1       0
#XS Ineff= 2 , 0
           432.5 2258.07   805.1         2259.28
Permanent Ineff=
       F       F
Bank Sta=531.72,642.03
XS Rating Curve= 0 ,0
Exp/Cntr(USF)=0,0
Exp/Cntr=0.5,0.3