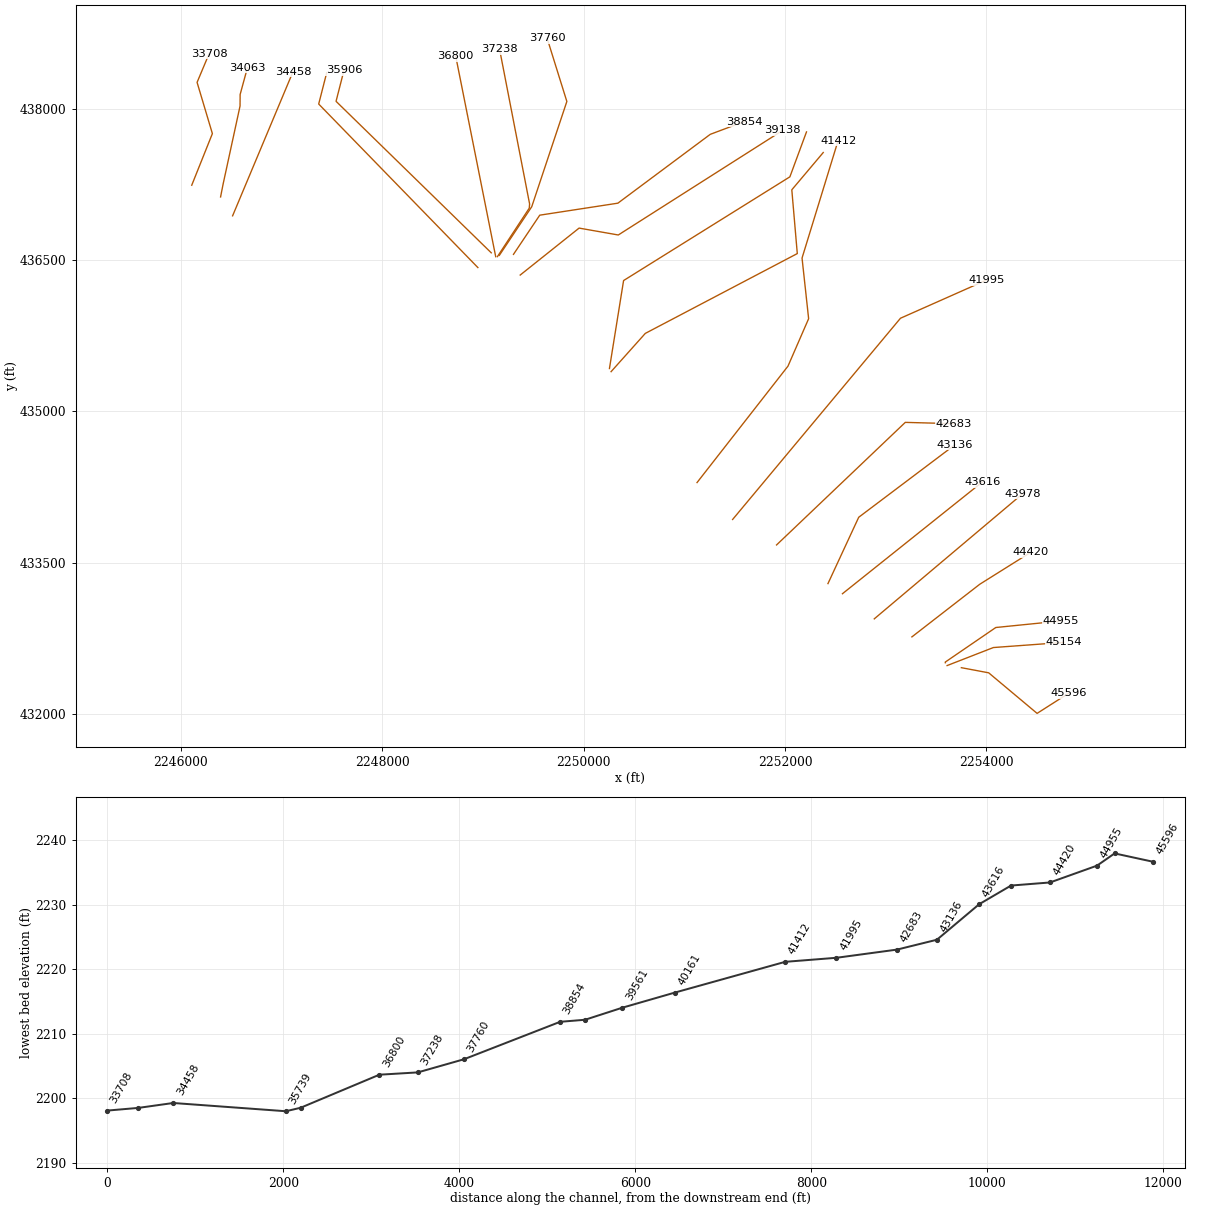
HEC-RAS study KNAPPCK.prj: KNAPPCK

--- KNAPPCK.g01 (geometry) --- (continued)

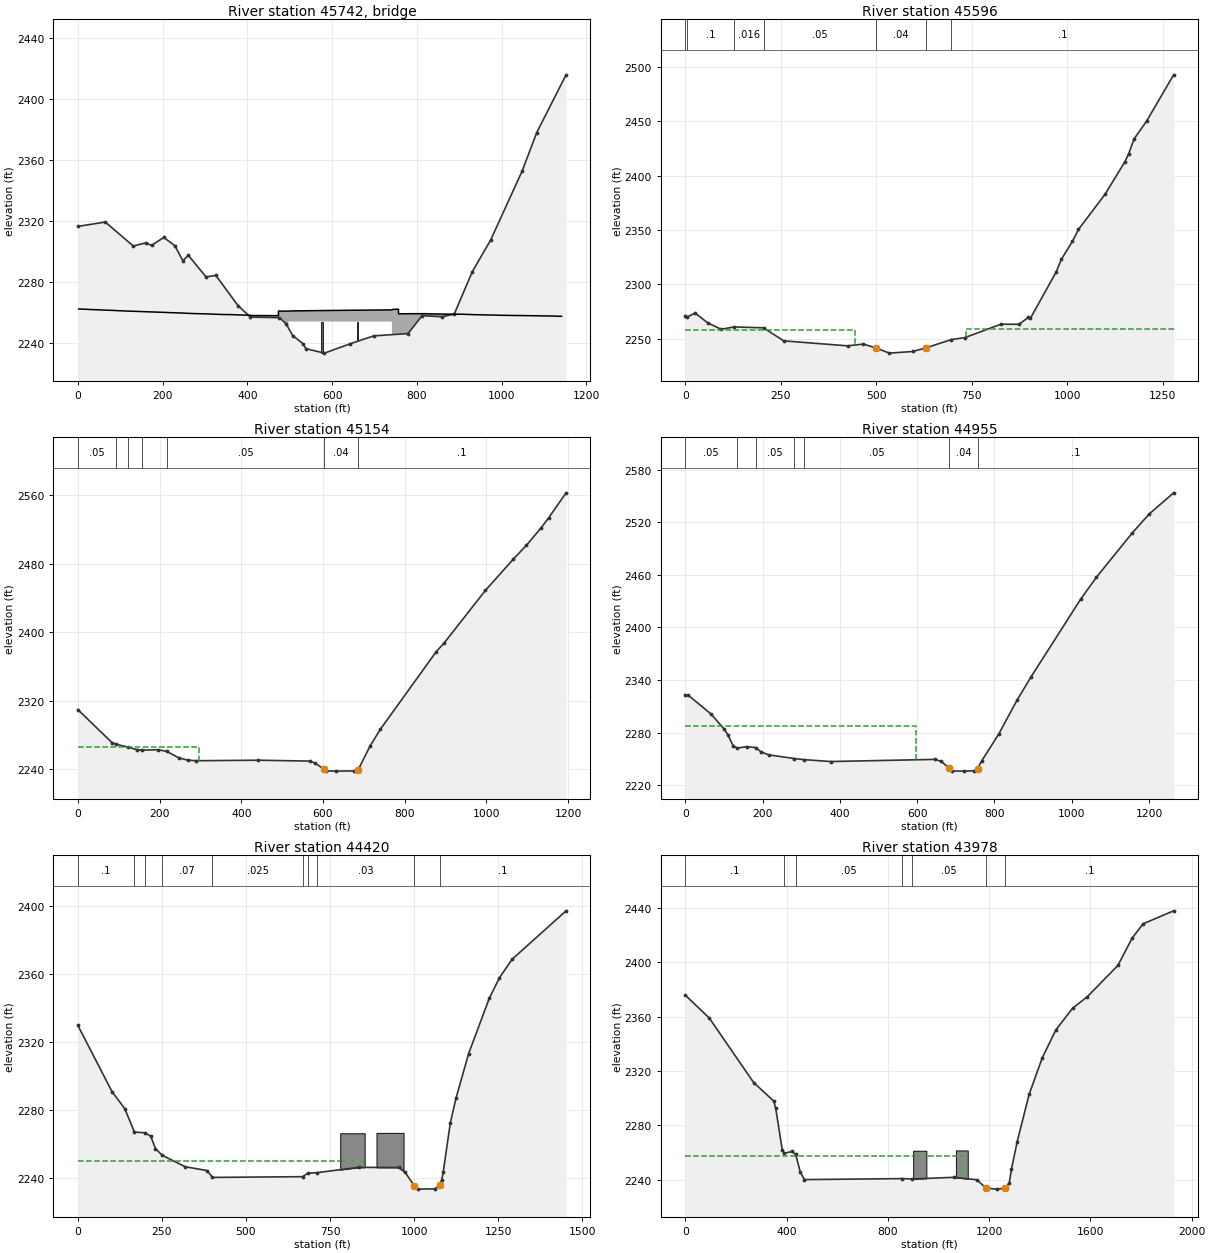
Type RM Length L Ch R = 3 ,45742   ,,,
BEGIN DESCRIPTION:
Huntersville Road
Bridge data: 54075KNA040
Width: 35.5' (measured on orthoimagery)
Railing height: 3'
2 Rectangular Piers, each with width: 4'
Structure bounding sections incorporate channel data from survey.
Deck from Lidar with survey data incorporated.
END DESCRIPTION:
Bridge Culvert--1,0,-1,-1, 0
Deck Dist Width WeirC Skew NumUp NumDn MinLoCord MaxHiCord MaxSubmerge Is_Ogee
64,35.5,2.6,0, 200, 190, , , 0.98, 0, 0,0,,
    2.07     5.6   7.739   10.18  13.408  16.248  19.078  22.316  24.747  28.385
  32.196  34.453  36.085  38.918  42.866  47.419  52.564  61.588  64.635  67.255
   70.67  74.916  80.258  82.741  88.776  92.758  96.283  98.426 101.624 104.093
  109.76 112.308 117.649 121.095 126.762 128.332 131.024  132.43 137.059 143.094
 146.598 152.265 155.165 157.933 161.201   163.6 165.724 169.268 174.935 177.769
 179.307 185.342 189.103 194.771 197.413 200.438 203.116 206.105 208.939 215.519
  217.44 220.274 223.107 225.941 228.775 234.442 240.444  242.95 245.852 248.622
 251.014  257.13 262.802 265.638  266.87 276.451 279.818 282.654  285.49 288.691
 293.296 298.581  307.05 311.014  313.85  319.29 322.358 325.194  328.03 333.702
 337.355 342.189 345.017  347.11 350.674 354.175 358.527 364.235 367.645 369.944
 373.303 376.131  378.96 387.814 393.421 395.931 401.588 404.416 407.245   408.1
  454.31   473.4   473.4   496.5  503.26  600.58   741.1  744.45   756.7   756.7
  781.28  824.29 830.528 838.032 840.885 845.658 849.443 854.372 858.001 863.706
 869.412 870.873 874.076 875.917 880.822 886.003 891.046 896.089 897.939 903.644
 907.412 912.371  915.38 918.195 924.019 930.546 938.578  941.49 944.402 947.314
  952.81 953.679 958.962 962.167 966.846 971.524 973.521 976.433 980.882 984.524
 992.235 996.817 999.9461002.6411007.6571011.3761015.3681025.9361027.6691032.347
1038.5021043.4071053.9241055.7411057.9671061.6361063.7911066.7031069.3471072.527
1074.4561081.2621084.5561088.7491091.5391095.6421101.3871104.2591105.5051108.268
1110.0041113.148 1115.751119.4721124.3671126.4551130.1121132.668 1138.731141.602
2262.4272262.4142262.3872262.3842262.3312262.3122262.2582262.2372262.1752262.107
2262.0822262.0542262.0172262.0112261.9692261.9082261.8812261.7342261.7142261.683
2261.6122261.5852261.5632261.533  2261.42261.3592261.3442261.3062261.2852261.226
2261.1462261.1222261.0942261.0192260.9962261.0212260.9842260.9322260.8982260.827
2260.7622260.7442260.7482260.6852260.6472260.6062260.5942260.547 2260.492260.476
2260.4832260.4482260.3752260.3062260.2542260.2662260.2522260.1982260.1792260.063
2260.053 2260.012260.0232260.0042259.9662259.9062259.8682259.813 2259.842259.751
2259.7142259.6782259.5832259.515  2259.52259.4432259.4062259.4062259.3662259.367
2259.2892259.2622259.169 2259.162259.1282259.0962259.0472259.0272258.9692258.915
2258.8442258.8232258.8352258.8292258.7792258.8052258.7812258.6942258.6692258.688
2258.6192258.6172258.551  2258.52258.4382258.4032258.3642258.4052258.353 2258.16
 2258.122258.0732261.073 2261.02 2261.18 2261.49 2261.86 2262.242262.2772259.277
 2259.35 2259.372259.2532259.2212259.2372259.1882259.1912259.1732259.1732259.135
2259.1482259.1412259.0972259.0892259.0982259.0142259.0732259.0332259.0312259.055
2259.0032258.9642258.9082258.8872258.8252258.7352258.6912258.7012258.6782258.682
2258.6252258.6252258.5722258.5692258.522 2258.522258.5022258.4372258.4692258.444
2258.3482258.355 2258.312258.309 2258.292258.2332258.2392258.2072258.2192258.225
2258.1992258.1592258.1562258.1492258.1182258.109 2258.082258.0622258.0652258.052
2258.0622257.9992257.9872257.925 2257.922257.8872257.9132257.8922257.9062257.894
2257.8532257.8472257.8142257.825 2257.78 2257.792257.7592257.7712257.6732257.644
                                                                                
                                                                                
                                                                                
                                                                                
                                                                                
                                                                                
                                                                                
                                                                                
                                                                                
                                                                                
                                                                                
                         2254.212254.2092254.1932254.175
                                                                                
                                                                                
                                                                                
                                                                                
                                                                                
                                                                                
                                                                                
                                                                                
   2.196   4.453   6.085   8.918  12.866  17.419  22.564  31.588  34.635  37.255
   40.67  44.916  50.258  52.741  58.776  62.758  66.283  68.426  71.624  74.093
   79.76  82.308  87.649  91.095  96.762  98.332 101.024  102.43 107.059 113.094
 116.598 122.265 125.165 127.933 131.201   133.6 135.724 139.268 144.935 147.769
 149.307 155.342 159.103 164.771 167.413 170.438 173.116 176.105 178.939 185.519
  187.44 190.274 193.107 195.941 198.775 204.442 210.444  212.95 215.852 218.622
 221.014  227.13 232.802 235.638  236.87 246.451 249.818 252.654  255.49 258.691
 263.296 268.581  277.05 281.014  283.85  289.29 292.358 295.194  298.03 303.702
 307.355 312.189 315.017  317.11 320.674 324.175 328.527 334.235 337.645 339.944
 343.303 346.131  348.96 357.814 363.421 365.931 371.588 374.416 377.245   378.1
  424.31   443.4   443.4   466.5  473.26  570.58   711.1  714.45   726.7   726.7
  751.28  794.29 800.528 808.032 810.885 815.658 819.443 824.372 828.001 833.706
 839.412 840.873 844.076 845.917 850.822 856.003 861.046 866.089 867.939 873.644
 877.412 882.371  885.38 888.195 894.019 900.546 908.578  911.49 914.402 917.314
  922.81 923.679 928.962 932.167 936.846 941.524 943.521 946.433 950.882 954.524
 962.235 966.817 969.946 972.641 977.657 981.376 985.368 995.936 997.6691002.347
1008.5021013.4071023.9241025.7411027.9671031.6361033.7911036.7031039.3471042.527
1044.4561051.2621054.5561058.7491061.5391065.6421071.3871074.2591075.5051078.268
1080.0041083.148 1085.751089.4721094.3671096.4551100.1121102.668 1108.731111.602
2262.0822262.0542262.0172262.0112261.9692261.9082261.8812261.7342261.7142261.683
2261.6122261.5852261.5632261.533  2261.42261.3592261.3442261.3062261.2852261.226
2261.1462261.1222261.0942261.0192260.9962261.0212260.9842260.9322260.8982260.827
2260.7622260.7442260.7482260.6852260.6472260.6062260.5942260.547 2260.492260.476
2260.4832260.4482260.3752260.3062260.2542260.2662260.2522260.1982260.1792260.063
2260.053 2260.012260.0232260.0042259.9662259.9062259.8682259.813 2259.842259.751
2259.7142259.6782259.5832259.515  2259.52259.4432259.4062259.4062259.3662259.367
2259.2892259.2622259.169 2259.162259.1282259.0962259.0472259.0272258.9692258.915
2258.8442258.8232258.8352258.8292258.7792258.8052258.7812258.6942258.6692258.688
2258.6192258.6172258.551  2258.52258.4382258.4032258.3642258.4052258.353 2258.16
 2258.122258.0732261.073 2261.02 2261.18 2261.49 2261.86 2262.242262.2772259.277
 2259.35 2259.372259.2532259.2212259.2372259.1882259.1912259.1732259.1732259.135
2259.1482259.1412259.0972259.0892259.0982259.0142259.0732259.0332259.0312259.055
2259.0032258.9642258.9082258.8872258.8252258.7352258.6912258.7012258.6782258.682
2258.6252258.6252258.5722258.5692258.522 2258.522258.5022258.4372258.4692258.444
2258.3482258.355 2258.312258.309 2258.292258.2332258.2392258.2072258.2192258.225
2258.1992258.1592258.1562258.1492258.1182258.109 2258.082258.0622258.0652258.052
2258.0622257.9992257.9872257.925 2257.922257.8872257.9132257.8922257.9062257.894
2257.8532257.8472257.8142257.825 2257.78 2257.792257.7592257.7712257.6732257.644
                                                                                
                                                                                
                                                                                
                                                                                
                                                                                
                                                                                
                                                                                
                                                                                
                                                                                
                                                                                
                         2254.212254.2092254.1932254.175
                                                                                
                                                                                
                                                                                
                                                                                
                                                                                
                                                                                
                                                                                
                                                                                
Pier Skew, UpSta & Num, DnSta & Num=  ,576.8, 2 ,543, 2 , 0 , 0 , 0 ,,
       4       4
  2233.5  2254.2
       4       4
 2237.69  2254.2
Pier Skew, UpSta & Num, DnSta & Num=  ,659.8, 2 ,626, 2 , 0 , 0 , 0 ,,
       4       4
 2242.92  2254.2
       4       4
 2243.37  2254.2
BR Coef=-1 ,-1 , 0 ,1.25, 0 ,,,0.8,0,2,0,
WSPro=,,,, 1 ,,,, 0 ,,,, 0 ,,,,-1 ,-1 ,-1 , 0 , 0 , 0 , 0 , 0
BR U #Sta/Elev= 30
       0 2316.59    64.8 2319.47  130.81 2303.73  159.69 2305.75  173.98  2304.2
     203 2309.36   229.2 2303.89  247.73 2294.02  260.64 2297.67  302.56 2283.46
  325.68  2284.5  377.76 2264.71  407.36 2257.12  475.49 2256.74  491.21 2252.89
  506.93 2245.02  531.72  2239.6  538.05 2236.44  581.93  2233.5  642.03 2239.57
  698.36 2244.82   779.2 2246.31  812.41 2258.07  859.85 2257.33  888.32 2259.15
  930.48  2286.7  974.26 2307.74 1048.65 2353.03 1082.83 2378.12 1152.06 2415.99
BR U #Mann= 5
       0      .1  531.72    .035  642.03      .1  812.41    .016  859.85      .1
BR D #Sta/Elev= 30
       0 2271.22     5.1 2269.99    25.4 2273.57      58 2264.61    93.6  2258.6
   127.2 2260.77   204.5 2259.96   257.4 2247.98   424.4 2243.38   466.1 2245.03
   498.2 2241.45  534.23 2236.68  594.63 2238.18     630 2241.51   695.7 2249.12
   732.2 2251.01   826.1  2263.3   873.1  2263.2   897.8 2269.48   903.4 2268.79
   970.7  2311.3   984.4 2323.07  1013.4  2339.5    1029 2350.43  1098.8 2382.83
    1151 2412.98  1160.5 2420.03  1174.7 2433.72  1207.6 2450.19  1278.3 2492.73
BR D #Mann= 7
       0     .05     5.1      .1   127.2    .016   204.5     .05   498.2    .035
     630     .08   695.7      .1
BC Design=,, 0 ,, 0 ,,,,,,
BC Use User HTab Curves=0
BC User HTab FreeFlow(D)= 0

Type RM Length L Ch R = 1 ,45596   ,387.9,441.9,525.9
BEGIN DESCRIPTION:
Structure XS 2- channel burned within banks
END DESCRIPTION:
XS GIS Cut Line= 4
2253751.20759145432455.4403089522254022.57970139432404.402051956
2254503.41207772432001.6151354122254819.48595098 432203.19456522
#Sta/Elev= 30
       0 2271.22     5.1 2269.99    25.4 2273.57      58 2264.61    93.6  2258.6
   127.2 2260.77   204.5 2259.96   257.4 2247.98   424.4 2243.38   466.1 2245.03
   498.2 2241.45  534.23 2236.68  594.63 2238.18     630 2241.51   695.7 2249.12
   732.2 2251.01   826.1  2263.3   873.1  2263.2   897.8 2269.48   903.4 2268.79
   970.7  2311.3   984.4 2323.07  1013.4  2339.5    1029 2350.43  1098.8 2382.83
    1151 2412.98  1160.5 2420.03  1174.7 2433.72  1207.6 2450.19  1278.3 2492.73
#Mann= 7 ,-1,0
       0     .05       0     5.1      .1       0   127.2    .016       0
   204.5     .05       0   498.2     .04       0     630     .08       0
   695.7      .1       0
#XS Ineff= 2 , 0
           442.8 2258.07   734.8         2259.28
Permanent Ineff=
       F       F
Bank Sta=498.2,630
XS Rating Curve= 0 ,0
Exp/Cntr(USF)=0,0
Exp/Cntr=0.5,0.3

Type RM Length L Ch R = 1 ,45154   ,198.2,199.8,201
BEGIN DESCRIPTION:
structure xs 1
END DESCRIPTION:
XS GIS Cut Line= 3
2253609.79926025432476.5814372162254069.20038866432655.436521895
2254769.07104426432706.720679799
#Sta/Elev= 30
       0 2309.71    84.1 2270.99    92.7 2269.49   122.6 2265.96   144.4 2263.03
   156.8 2262.42   195.7 2262.94   217.2  2261.1   247.2 2253.42   268.7 2250.85
   289.6 2250.11   440.4 2250.72   568.2 2249.69   580.9 2247.22   602.72240.108
   608.3  2238.2   632.3 2237.99   676.5  2238.2   684.82239.855   688.5 2241.95
     715  2267.1   740.6 2286.99     877 2377.22     897 2387.72   997.3  2448.6
  1065.6 2485.09  1097.6 2501.15  1133.7 2521.61  1152.2  2533.3  1194.7  2562.4
#Mann= 7 ,-1,0
       0     .05       0    92.7    .016       0   122.6     .05       0
   156.8    .016       0   217.2     .05       0   602.7     .04       0
   684.8      .1       0
#XS Ineff= 2 , 0
           295.4 2265.69
Permanent Ineff=
       F       F
#Block Obstruct= 2 , 0
           21.05 2329.71
Bank Sta=602.7,684.8
XS Rating Curve= 0 ,0
Exp/Cntr(USF)=0,0
Exp/Cntr=0.3,0.1

Type RM Length L Ch R = 1 ,44955   ,506,534.2,551.8
XS GIS Cut Line= 4
2253592.09045221432504.5794973122253591.03949354432510.792851121
2254093.32450814432854.463704713 2254738.9536059432919.557672168
#Sta/Elev= 30
       0 2322.82     6.3 2323.11    66.4 2301.22    99.8 2284.35   109.6  2277.8
   123.9 2264.63   133.7 2262.43   158.5 2263.99   182.2 2263.02   195.9 2257.93
     216 2254.65   282.2 2250.43   308.1 2249.19     376 2247.04   645.9 2249.49
     662 2247.31   683.1 2239.27   690.1 2236.26   721.7 2236.09   746.4 2236.44
   756.12238.829   766.5 2247.51   810.7 2278.13     859 2317.51   895.2 2344.04
  1023.8 2432.79    1064 2457.41  1156.8 2507.94  1200.7 2529.61  1263.8 2553.69
#Mann= 7 ,-1,0
       0     .05       0   133.7    .016       0   182.2     .05       0
   282.2    .016       0   308.1     .05       0   683.1     .04       0
   756.1      .1       0
#XS Ineff= 2 , 0
          597.07 2287.94
Permanent Ineff=
       F       F
Bank Sta=683.1,756.1
XS Rating Curve= 0 ,0
Exp/Cntr(USF)=0,0
Exp/Cntr=0.3,0.1

Type RM Length L Ch R = 1 ,44420   ,434.5,442.8,448.4
Node Name=O
XS GIS Cut Line= 3
2253259.92011504432761.2966537852253934.05466843433284.161990317
2254441.61520034433602.447590372
#Sta/Elev= 30
       0 2329.76   101.6 2290.82   139.8 2280.72   168.3 2267.01   199.7 2266.61
   216.8 2264.58     231 2257.29     251 2253.37   319.4 2246.63   384.9 2244.38
   400.2 2240.36   668.5  2240.8   683.7  2242.8   711.2 2243.16   835.4 2246.28
   954.8  2246.2   973.7 2243.31  1000.5  2235.5  1011.4 2233.48  1063.4 2233.65
  1075.9 2235.97  1082.3 2238.83    1087 2243.75  1107.9 2272.33  1124.8 2286.85
  1162.5 2313.19  1223.9 2345.65  1254.1 2357.68  1291.7 2368.57  1452.2 2397.05
#Mann= 10 ,-1,0
       0      .1       0   168.3    .016       0   199.7     .05       0
     251     .07       0   400.2    .025       0   668.5     .05       0
   683.7    .016       0   711.2     .03       0  1000.5     .04       0
  1075.9      .1       0
#XS Ineff= 2 , 0
             850    2250
Permanent Ineff=
       T       F
#Block Obstruct= 2 ,-1
  780.48  853.14 2266.31  888.34  968.82 2266.55
Bank Sta=1000.5,1075.9
XS Rating Curve= 0 ,0
Exp/Cntr(USF)=0,0
Exp/Cntr=0.3,0.1

Type RM Length L Ch R = 1 ,43978   ,372.1,361.3,358.5
XS GIS Cut Line= 2
2252886.15208312432940.3502431022254360.52528781434183.664960494
#Sta/Elev= 30
       0 2375.67    94.4 2358.88   269.5 2311.45   348.8 2297.79   356.9 2292.38
   382.4 2262.05   389.8 2259.32   421.2 2260.72   435.6 2258.55   454.2 2245.31
   470.4 2240.02   856.5 2240.74   894.8 2240.47  1059.6 2241.67  1151.7 2239.88
  1186.92233.757  1229.8    2233  1263.7 2233.66  1279.4 2237.57  1287.9  2247.7
  1310.7    2268  1357.8 2302.79    1410 2329.79  1463.9  2350.3  1529.2 2366.07
  1588.1 2374.69  1708.4 2397.62  1764.8 2417.74  1807.8 2428.23  1928.6  2437.8
#Mann= 7 ,-1,0
       0      .1       0   389.8    .016       0   435.6     .05       0
   856.5    .016       0   894.8     .05       0  1186.9     .04       0
  1263.7      .1       0
#XS Ineff= 2 , 0
         1096.87 2257.46
Permanent Ineff=
       F       F
#Block Obstruct= 2 ,-1
   899.7  951.84 2261.26 1068.44 1115.27 2261.48
Bank Sta=1186.9,1263.7
XS Rating Curve= 0 ,0
Exp/Cntr(USF)=0,0
Exp/Cntr=0.3,0.1

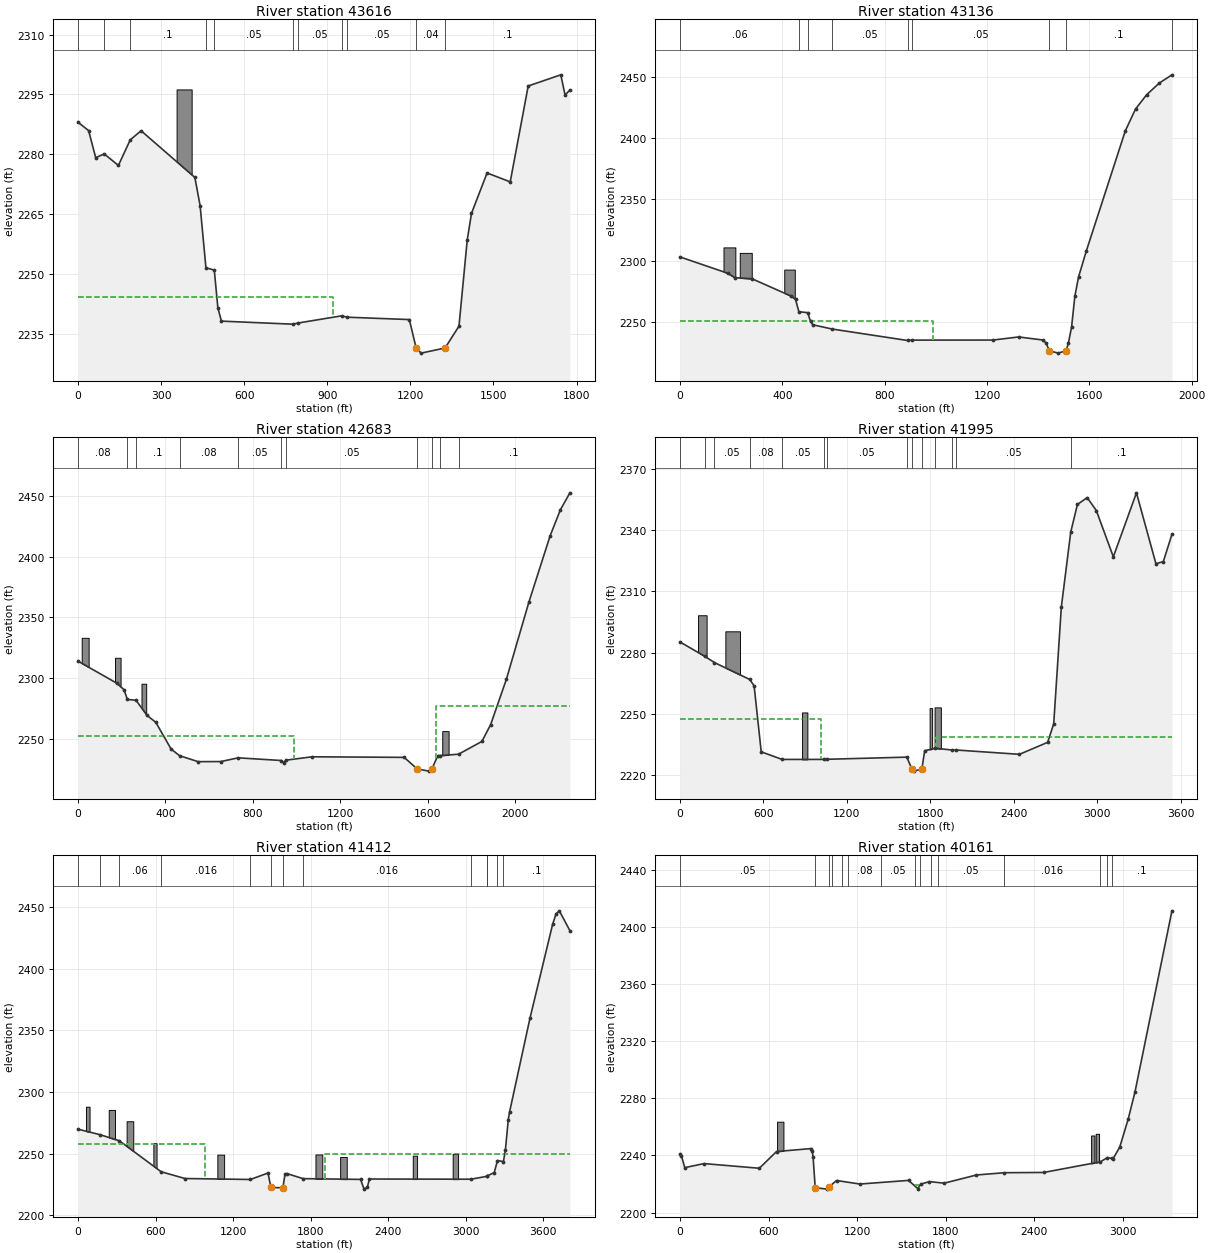
Type RM Length L Ch R = 1 ,43616   ,489.8,480.8,471.3
XS GIS Cut Line= 2
2252570.26918748433190.0977807042253957.87813126434298.439515675
#Sta/Elev= 30
       0 2288.03    38.3 2285.94    63.9 2279.13    94.6 2280.09   145.8  2277.2
   188.5 2283.61   227.7  2285.9   421.9 2274.18   440.8 2267.12   461.8 2251.55
     492 2250.92   504.9 2241.48   517.7 2238.14   775.5 2237.37   795.9 2237.68
   951.3 2239.46   972.7 2239.12  1196.1 2238.53  1220.8 2231.39  1238.7 2230.11
  1325.2  2231.4  1375.4 2236.88  1405.1 2258.44  1420.5 2265.16  1476.8 2275.31
  1560.4 2273.07  1625.3 2297.13    1743 2299.93  1758.4 2294.85  1775.9 2296.13
#Mann= 11 ,-1,0
       0      .1       0    94.6     .04       0   188.5      .1       0
   461.8    .016       0     492     .05       0   775.5    .045       0
   795.9     .05       0   951.3    .016       0   972.7     .05       0
  1220.8     .04       0  1325.2      .1       0
#XS Ineff= 2 , 0
          921.78 2244.12
Permanent Ineff=
       F       F
#Block Obstruct= 1 ,-1
  355.86  410.29 2296.27
Bank Sta=1220.8,1325.2
XS Rating Curve= 0 ,0
Exp/Cntr(USF)=0,0
Exp/Cntr=0.3,0.1

Type RM Length L Ch R = 1 ,43136   ,448.9,453,459
XS GIS Cut Line= 3
2252426.27203293433290.4594338712252731.72054257433949.355504661
2253687.33802272434669.341277378
#Sta/Elev= 30
       0 2303.06   187.2  2289.7   213.8 2286.13   280.8 2285.31   435.1 2271.02
   451.5 2268.36   464.4 2258.37   499.1 2257.59     510 2250.42   518.8 2247.73
   594.2 2244.26   889.3  2234.9   907.1 2235.21  1223.4 2235.26  1323.4 2237.79
  1417.3 2235.32  1430.6 2232.93  1443.4 2226.55  1478.1 2224.59  1509.1 2226.58
  1518.1  2232.9  1530.3 2245.71  1543.3  2271.1  1557.6 2286.71  1588.2 2308.06
  1740.4  2405.9  1780.4 2423.75  1823.6 2435.37  1873.7    2445  1922.7 2451.65
#Mann= 9 ,-1,0
       0     .06       0   464.4    .016       0   499.1      .1       0
   594.2     .05       0   889.3    .045       0   907.1     .05       0
  1443.4     .04       0  1509.1      .1       0  1922.7      .1       0
#XS Ineff= 2 , 0
          987.38 2250.97
Permanent Ineff=
       F       F
#Block Obstruct= 3 ,-1
   169.8  216.24 2310.86  233.34  280.31 2306.39  407.33  448.47 2292.76
Bank Sta=1443.4,1509.1
XS Rating Curve= 0 ,0
Exp/Cntr(USF)=0,0
Exp/Cntr=0.3,0.1

Type RM Length L Ch R = 1 ,42683   ,692.1,688,691.6
XS GIS Cut Line= 3
2251915.73666682433674.4518459872253194.25685716  434891.8823344
2253678.61092245434878.791683987
#Sta/Elev= 30
       0 2313.89   177.7 2295.64   210.5 2290.24   225.8 2282.26   265.4 2281.57
   315.4 2269.13   355.9 2263.34   425.9 2241.27   464.6  2235.8   549.2 2230.88
   653.6 2230.96   732.2 2234.04   930.2 2231.83   941.6 2230.06     950 2232.08
  1071.3 2234.91  1491.9 2234.42  1551.12224.921  1604.9 2223.06  1618.9 2224.98
  1645.5 2235.74  1657.6 2235.94  1740.5 2237.03  1847.4 2247.59  1887.4 2261.46
  1959.4 2298.91  2062.1 2362.48  2159.5 2417.39  2206.3 2438.82    2250 2452.87
#Mann= 11 ,-1,0
       0     .08       0   225.8    .016       0   265.4      .1       0
   464.6     .08       0   732.2     .05       0   930.2    .045       0
     950     .05       0  1551.1     .04       0  1618.9     .08       0
  1657.6     .05       0  1740.5      .1       0
#XS Ineff= 2 , 0
             987 2251.96 1639.41         2276.83
Permanent Ineff=
       F       F
#Block Obstruct= 4 ,-1
   16.84   48.69 2333.17  169.23  194.74 2316.67  290.35  311.97 2295.24
    1666 1695.07 2256.09
Bank Sta=1551.1,1618.9
XS Rating Curve= 0 ,0
Exp/Cntr(USF)=0,0
Exp/Cntr=0.3,0.1

Type RM Length L Ch R = 1 ,41995   ,571.7,583,616.5
Node Name=N
XS GIS Cut Line= 3
2251479.38165306433927.5377539722253146.25780565 435926.04371703
2254001.51363263436305.672579009
#Sta/Elev= 30
       0 2285.18   179.2 2278.11   246.9 2275.11   501.6 2266.78   532.8 2263.67
   583.9 2231.27   734.4 2227.53  1033.5 2227.55  1059.5 2227.61  1631.2 2228.66
  1668.6 2222.64  1681.1 2221.79  1739.42222.825  1759.7 2231.81  1836.4 2233.02
  1955.9 2232.15  1986.7 2232.16  2441.3 2230.04  2643.9 2235.92  2687.7 2244.99
  2742.6 2302.38  2810.2 2339.17  2858.3 2352.71  2928.4 2356.07  2994.2 2349.73
  3116.5 2326.99  3282.8 2358.42  3422.9 2323.59  3476.1 2324.67  3538.1 2338.03
#Mann= 14 ,-1,0
       0     .05       0   179.2    .016       0   246.9     .05       0
   501.6     .08       0   734.4     .05       0  1033.5    .045       0
  1059.5     .05       0  1631.2      .1       0  1668.6     .04       0
  1739.4      .1       0  1836.4     .05       0  1955.9    .016       0
  1986.7     .05       0  2810.2      .1       0
#XS Ineff= 2 , 0
         1012.05 2247.32 1843.01         2238.36
Permanent Ineff=
       F       F
#Block Obstruct= 5 ,-1
  129.75  191.16 2298.32  325.96  430.81 2290.43  877.73  915.81 2250.61
 1795.09 1813.29 2252.72 1830.85 1875.91 2253.09
Bank Sta=1668.6,1739.4
XS Rating Curve= 0 ,0
Exp/Cntr(USF)=0,0
Exp/Cntr=0.3,0.1

Type RM Length L Ch R = 1 ,41412   ,1230,1250.6,856
XS GIS Cut Line= 5
 2251125.9340919434294.075965538 2252029.1889704435450.416752023
2252234.27582687435921.6801668932252168.82257481436523.850085893
 2252526.6336861437688.917972654
#Sta/Elev= 30
       0 2269.82   172.6  2265.3   320.1  2260.4   643.5 2235.26   827.4 2229.78
  1333.8 2228.99  1470.3 2234.26  1492.1 2222.55  1585.1 2222.18  1601.2 2233.14
  1615.1 2233.83  1740.8 2229.68    2186 2229.06  2213.1 2221.16  2238.3 2222.64
  2254.4 2229.37  3040.3 2229.21  3160.5  2231.5  3165.8 2231.92  3220.2 2234.56
  3245.3 2244.34  3291.3 2243.56  3306.9 2253.24    3329 2277.67  3338.8 2283.76
  3496.4 2359.77  3672.1 2436.23  3698.4 2444.59    3724 2447.12  3805.8    2431
#Mann= 13 ,-1,0
       0     .05       0   172.6    .016       0   320.1     .06       0
   643.5    .016       0  1333.8     .06       0  1492.1     .04       0
  1585.1      .1       0  1740.8    .016       0  3040.3     .05       0
  3160.5    .016       0  3165.8     .05       0  3245.3    .016       0
  3291.3      .1       0
#XS Ineff= 2 , 0
          984.51 2257.73 1907.06         2249.39
Permanent Ineff=
       F       F
#Block Obstruct= 9 ,-1
   61.27   89.46 2288.09  237.53   286.1 2285.48  375.97  427.64 2276.27
  582.92  607.68 2258.54 1077.97 1130.47 2249.17 1837.12 1890.07 2249.32
 2028.07 2079.03 2247.26 2589.95 2623.38 2248.33 2898.54 2940.58 2249.77
Bank Sta=1492.1,1585.1
XS Rating Curve= 0 ,0
Exp/Cntr(USF)=0,0
Exp/Cntr=0.3,0.1

Type RM Length L Ch R = 1 ,40161   ,599.2,599.9,634.4
XS GIS Cut Line= 5
 2250272.3507893435395.7621684882250612.03932774435775.635619223
2252121.65726275436568.408335402 2252067.1922082437201.758877442
2252379.39189548437571.985358778
#Sta/Elev= 30
       0 2241.01     9.4  2239.9      32 2231.45   162.4 2234.29   537.5 2231.02
   654.3 2242.75   889.3 2244.81   895.9 2243.25   901.9 2238.92   916.4 2217.37
   997.7  2216.4  1006.7 2217.71    1061 2222.44  1219.1 2219.97  1548.9 2222.51
  1612.1 2216.75  1630.2  2219.8  1689.9 2221.67  1790.6 2220.57  2009.7 2226.31
  2199.5  2227.9  2465.5 2228.08  2849.8 2235.54  2896.7 2238.48  2926.4 2237.94
  2933.4 2237.25  2981.3 2245.95  3037.7 2265.33  3083.5 2284.16  3334.7 2411.36
#Mann= 15 ,-1,0
       0     .05       0   916.4     .04       0  1006.7      .1       0
  1029.6     .08       0  1099.6      .1       0  1139.6     .08       0
  1359.6     .05       0  1589.6    .045       0  1629.6     .05       0
  1699.6      .1       0  1749.6     .05       0  2199.5    .016       0
  2849.8     .05       0  2896.7    .016       0  2926.4      .1       0
#XS Ineff= 1 ,-1
    1585  1630.2 2219.56
Permanent Ineff=
       T
#Block Obstruct= 3 ,-1
  657.87  700.96 2263.64 2786.69 2809.42 2253.99 2817.59 2840.73 2255.18
Bank Sta=916.4,1006.7
XS Rating Curve= 0 ,0
Exp/Cntr(USF)=0,0
Exp/Cntr=0.3,0.1

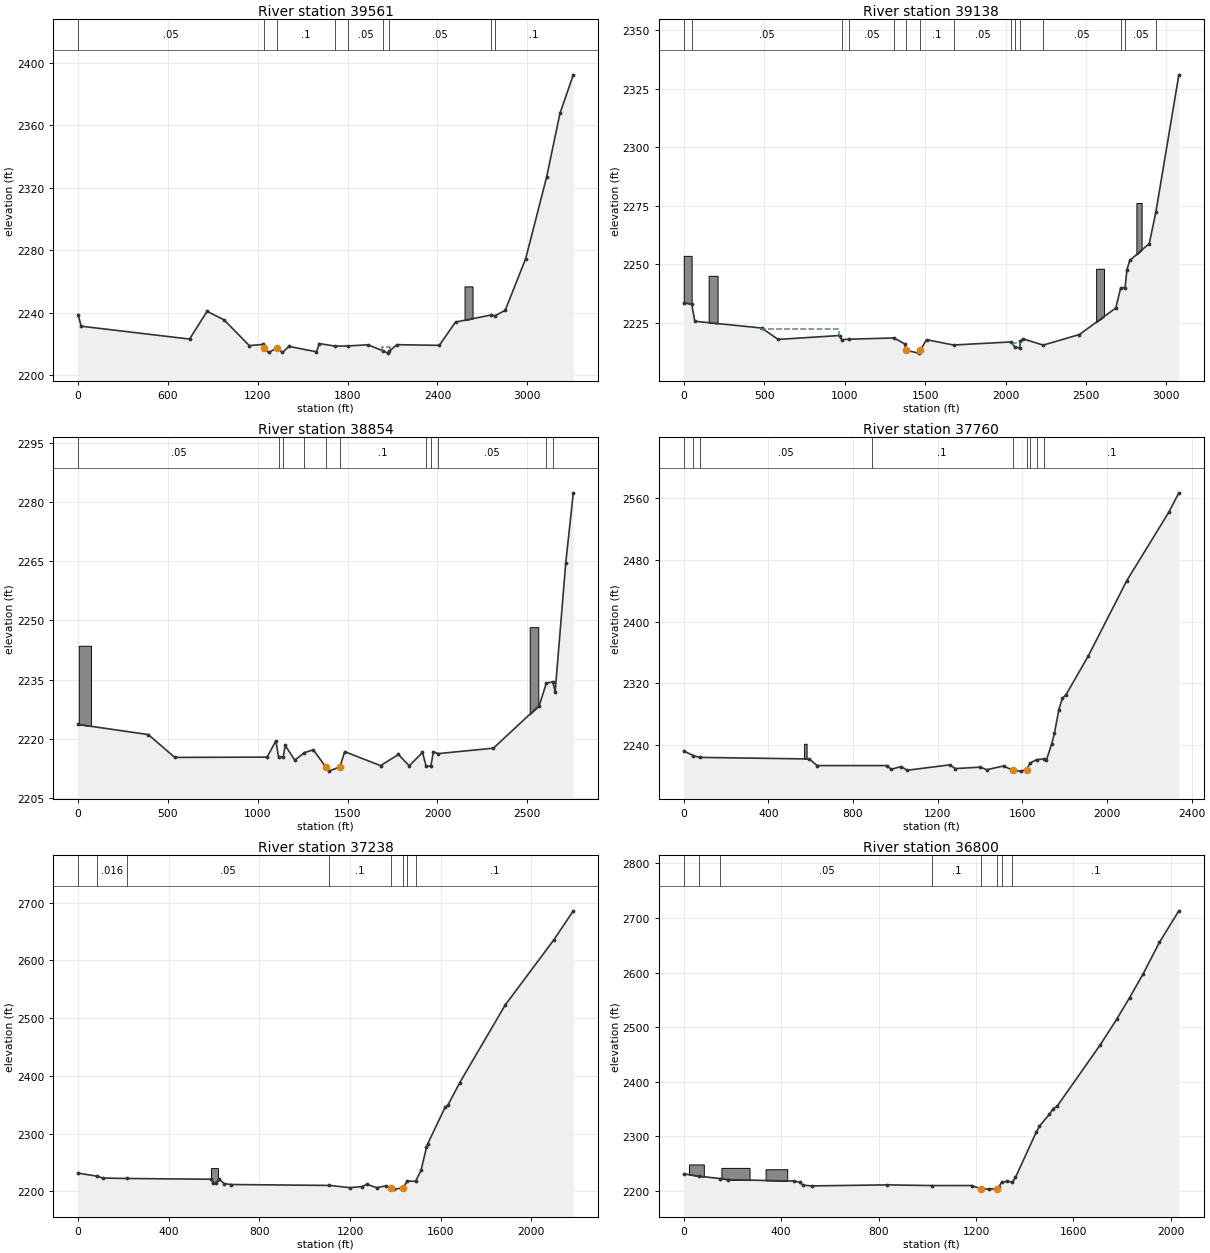
Type RM Length L Ch R = 1 ,39561   ,416.8,423.1,418.8
Node Name=M
XS GIS Cut Line= 4
2250255.96071286435426.7486957132250396.39106513436300.509672877
2252048.09768767 437330.622022462252212.94291509437776.673814312
#Sta/Elev= 30
       0 2238.68    19.8 2231.28   743.9 2223.03   860.9 2240.79   974.3 2235.35
  1143.2 2218.84  1233.9 2219.62 1242.03 2217.08  1271.7 2214.47  1327.9 2217.27
  1364.4 2214.49  1407.8 2218.34  1591.8 2214.89  1610.7 2220.17  1717.7  2218.5
    1804 2218.65    1936  2219.4    2038 2215.38    2068 2214.04  2078.6 2215.35
  2129.3 2219.45  2412.1 2219.02  2520.5 2233.93    2758 2238.44  2783.5 2237.94
  2852.3 2241.44  2989.3 2274.59  3129.4 2326.98  3218.1 2367.58  3307.1 2392.25
#Mann= 9 ,-1,0
       0     .05       0 1242.03     .04       0  1327.9      .1       0
  1717.7      .1       0    1804     .05       0    2038    .045       0
  2078.6     .05       0    2758    .016       0  2783.5      .1       0
#XS Ineff= 1 ,-1
  2030.3  2084.4 2217.82
Permanent Ineff=
       F
#Block Obstruct= 1 ,-1
 2580.66 2634.38 2256.78
Bank Sta=1242.03,1327.9
XS Rating Curve= 0 ,0
Exp/Cntr(USF)=0,0
Exp/Cntr=0.3,0.1

Type RM Length L Ch R = 1 ,39138   ,415,283.6,308.3
XS GIS Cut Line= 4
 2249369.4830166436355.0892076072249954.36574302436821.468088213
2250343.76900297436753.0594074112251975.37185204437791.218981437
#Sta/Elev= 30
       0 2233.68    49.5 2233.06    68.9 2225.76   484.3 2222.88   586.9 2218.03
   969.2 2219.69   981.3 2217.88  1026.2 2218.11  1307.6 2218.64  1372.7 2216.12
  1383.42213.329  1461.6 2212.17  1470.4 2213.42    1509 2217.91  1676.9 2215.63
  2035.2 2216.95  2058.9 2214.63  2087.4 2214.42  2092.1 2217.25  2108.7 2218.27
  2234.4 2215.59  2459.3 2220.11  2685.3  2231.4  2715.9 2240.03  2743.2 2240.11
  2754.8 2247.84  2772.2  2251.7  2893.4 2258.92  2934.4 2272.33  3077.3  2330.9
#Mann= 15 ,-1,0
       0    .016       0    49.5     .05       0   981.3    .045       0
  1026.2     .05       0  1307.6      .1       0  1383.4     .04       0
  1470.4      .1       0  1676.9     .05       0  2035.2     .08       0
  2058.9    .045       0  2087.4     .08       0  2234.4     .05       0
  2715.9    .016       0  2743.2     .05       0  2934.4      .1       0
#XS Ineff= 2 ,-1
  476.67  966.85 2222.51  2047.8    2090 2216.58
Permanent Ineff=
       F       F
#Block Obstruct= 4 ,-1
       0   49.05 2253.68  154.67  210.32 2245.17 2563.19 2611.84 2248.16
 2813.36 2845.88 2276.21
Bank Sta=1383.4,1470.4
XS Rating Curve= 0 ,0
Exp/Cntr(USF)=0,0
Exp/Cntr=0.3,0.1

Type RM Length L Ch R = 1 ,38854   ,557.7,1094.3,1193
XS GIS Cut Line= 5
2249302.72851371436560.6912184292249563.65429773436949.830534251
2250339.68356917437069.0466252262251257.42253365437752.852128174
2251592.57720451437878.816299769
#Sta/Elev= 30
       0 2223.67   390.4  2221.1   537.8 2215.32  1051.8  2215.4  1100.4 2219.49
  1115.4 2215.52  1140.8 2215.38    1153 2218.35  1205.6 2214.63  1259.3 2216.53
  1309.1 2217.25    1379 2212.86  1394.2 2211.85    1457 2212.91  1483.7 2216.78
  1683.3 2213.24  1782.8 2216.06    1843 2213.19  1916.7 2216.59  1937.3 2213.07
  1963.5 2213.17  1977.3 2216.75  2002.5 2216.28  2311.7 2217.66  2566.6 2228.46
  2606.2 2234.12  2641.9 2234.44  2655.2 2231.92  2714.2 2264.52  2756.2 2282.29
#Mann= 11 ,-1,0
       0     .05       0  1115.4    .045       0  1140.8     .08       0
  1259.3      .1       0    1379     .04       0    1457      .1       0
  1937.3    .045       0  1963.5      .1       0  2002.5     .05       0
  2606.2    .016       0  2641.9      .1       0
#XS Ineff= 1 ,-1
  1916.5 1989.42 2214.03
Permanent Ineff=
       F
#Block Obstruct= 2 ,-1
    3.37   71.05 2243.59 2513.52 2561.48 2248.28
Bank Sta=1379,1457
XS Rating Curve= 0 ,0
Exp/Cntr(USF)=0,0
Exp/Cntr=0.3,0.1

Type RM Length L Ch R = 1 ,37760   ,171.3,522.2,536.2
XS GIS Cut Line= 4
2249162.19107828436550.9525806372249484.22107844437033.997580878
 2249832.9127325438079.1295272212249637.12450159438706.227473606
#Sta/Elev= 30
       0 2232.14    45.9 2226.12    74.8 2223.87     593 2221.79   630.3 2213.23
   959.6 2213.22   980.3 2208.34  1026.7 2211.97  1056.2  2207.2  1256.5 2214.13
  1283.9 2209.34    1402 2211.22  1431.5 2207.83  1511.6 2212.79  1553.8 2207.12
  1591.7 2206.03  1620.1 2207.72  1636.1 2216.56  1667.5  2220.9  1700.5 2221.76
  1713.8 2220.58  1738.5  2241.4  1751.6 2255.32  1772.5 2285.95  1789.2 2300.65
  1805.9 2305.04  1910.7 2354.99  2093.3 2453.09  2292.1 2541.99  2339.3    2567
#Mann= 9 ,-1,0
       0     .05       0    45.9    .016       0    74.8     .05       0
   887.2      .1       0  1553.8     .04       0  1620.1      .1       0
  1636.1     .06       0  1667.5    .016       0  1700.5      .1       0
#Block Obstruct= 1 ,-1
  568.68  580.55 2241.55
Bank Sta=1553.8,1620.1
XS Rating Curve= 0 ,0
Exp/Cntr(USF)=0,0
Exp/Cntr=0.3,0.1

Type RM Length L Ch R = 1 ,37238   ,500.7,437.3,437.6
XS GIS Cut Line= 4
2249143.79500844436538.6720491642249459.38119922 437019.22374876
2249462.96740594437061.0628270842249164.11684649438600.740909374
#Sta/Elev= 30
       0 2231.73      83 2226.38     109 2223.22   213.6 2222.43   584.9 2221.13
   596.9 2214.44     609 2214.38   621.1 2221.06   645.5 2213.49     674    2212
    1109  2210.4  1199.7  2206.5  1252.7 2208.51  1274.6 2212.35  1317.9 2206.44
  1358.6 2209.74    1379 2205.59  1392.1    2204  1433.72205.957  1452.3 2218.01
    1489 2217.47  1513.3 2236.38  1537.3 2276.46    1542 2281.96  1619.4 2345.65
  1631.6 2349.36    1684 2388.25  1884.2 2522.51  2100.2  2636.1  2185.3 2685.96
#Mann= 8 ,-1,0
       0     .05       0      83    .016       0   213.6     .05       0
    1109      .1       0    1379    .045       0  1433.7      .1       0
  1452.3    .016       0    1489      .1       0
#Block Obstruct= 1 ,-1
  586.34  616.91 2240.38
Bank Sta=1379,1433.7
XS Rating Curve= 0 ,0
Exp/Cntr(USF)=0,0
Exp/Cntr=0.3,0.1

Type RM Length L Ch R = 1 ,36800   ,874.5,894.7,933.2
BEGIN DESCRIPTION:
structure xs 4
END DESCRIPTION:
Node Name=L
XS GIS Cut Line= 2
2249126.27005537436537.3203859962248728.65153911438531.260298416
#Sta/Elev= 30
       0 2231.61      61 2227.38   150.8 2222.88   183.4 2220.94   452.6 2218.38
   476.1 2216.41   489.3 2210.92     526 2209.53     836 2211.42  1021.2 2210.16
  1182.7 2210.22  1218.72204.473    1252 2203.64  1284.7 2204.16  1293.9 2207.39
  1305.1 2216.07  1325.5 2217.86  1349.9 2216.78  1362.2 2225.05  1447.8 2308.21
  1460.5 2318.81  1501.3 2340.38  1517.2 2350.84  1533.5 2355.51  1708.9 2466.75
  1778.2  2514.8  1831.1 2554.26  1887.3 2598.21  1953.6 2655.55  2033.2 2713.03
#Mann= 8 ,-1,0
       0     .05       0      61    .016       0   150.8     .05       0
  1021.2      .1       0  1218.7     .04       0  1284.7      .1       0
  1305.1    .016       0  1349.9      .1       0
#Block Obstruct= 3 ,-1
   21.62   82.42 2248.85  154.68  270.25 2242.56   336.2  425.07 2240.05
Bank Sta=1218.7,1284.7
XS Rating Curve= 0 ,0
Exp/Cntr(USF)=0,0
Exp/Cntr=0.5,0.3

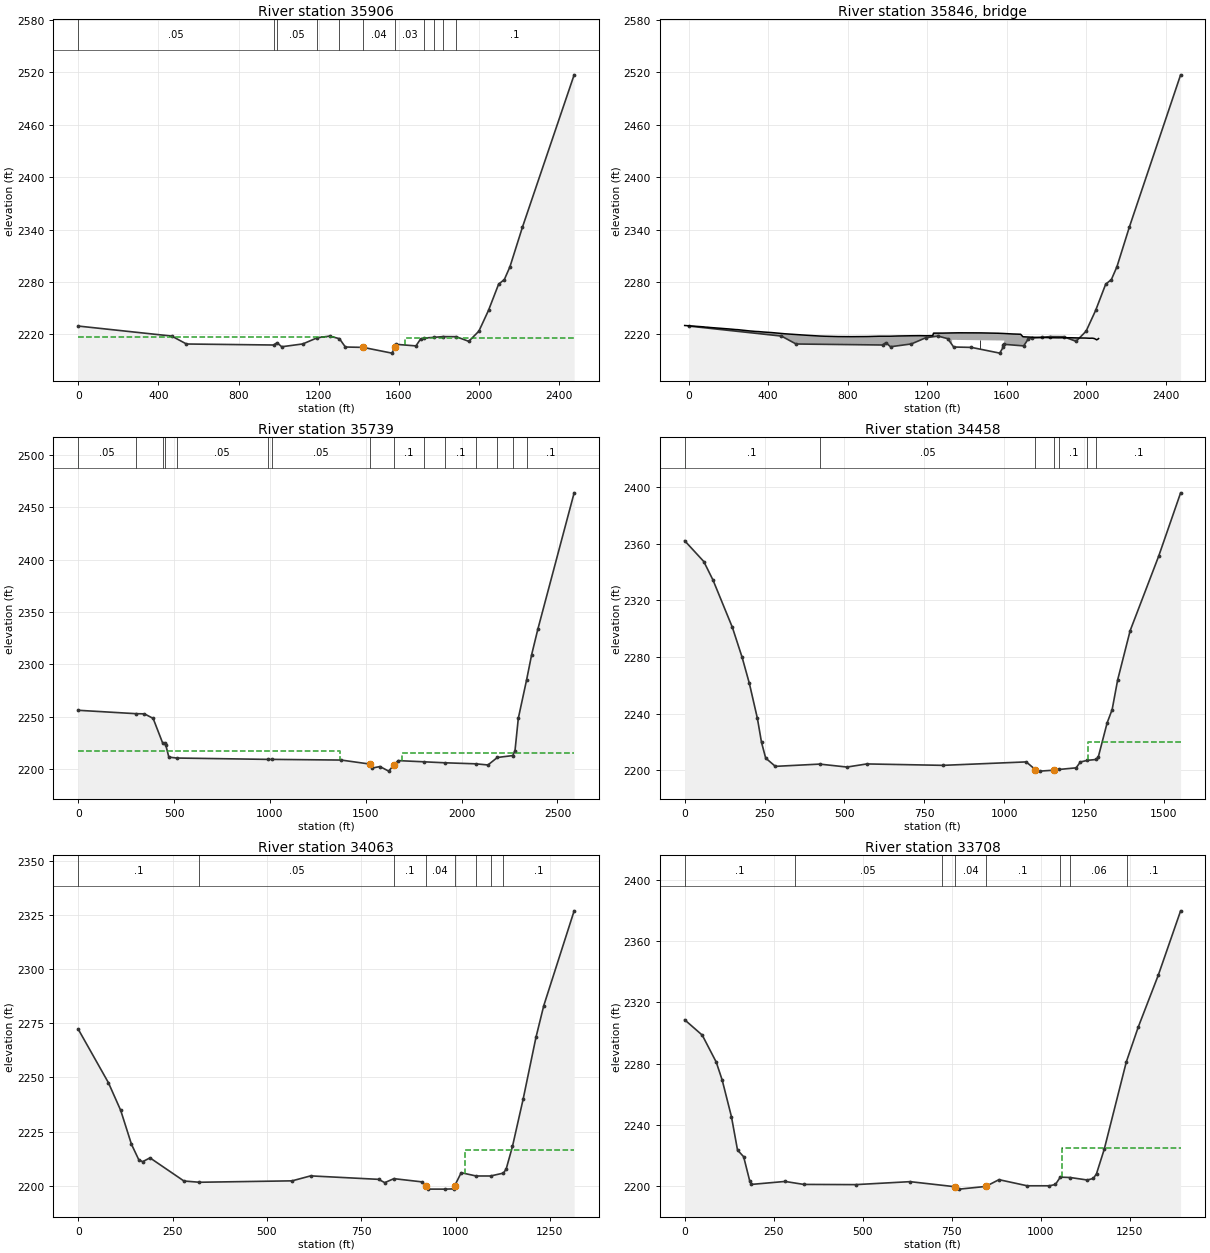
Type RM Length L Ch R = 1 ,35906   ,166.5,167.2,214.2
BEGIN DESCRIPTION:
Structure XS 3 - channel burned within banks
END DESCRIPTION:
XS GIS Cut Line= 3
2249082.04214739436575.9017650562247540.50534235438080.651311642
2247619.91354276438391.065185991
#Sta/Elev= 30
       0  2229.5   466.6 2218.03   540.1 2208.96   975.3  2207.8     992 2210.45
  1015.4  2205.8  1120.6 2209.03  1193.2 2216.14  1254.7 2217.98  1303.4 2215.04
    1333 2205.51 1422.412205.071  1564.7 2198.51 1581.95  2205.2  1582.3 2208.18
    1588 2208.55  1685.3 2206.78  1708.3 2214.67  1727.7 2215.77  1775.8 2216.59
  1819.3 2217.42  1885.8 2217.33  1948.8 2212.01  1999.2 2223.64  2047.3 2247.49
  2097.7 2277.43  2126.3 2282.72  2154.4 2297.47  2216.8 2342.82  2474.6 2517.04
#Mann= 11 ,-1,0
       0     .05       0   975.3    .016       0     992     .05       0
  1193.2    .016       0  1303.4     .05       0 1422.41     .04       0
 1581.95     .03       0  1727.7    .016       0  1775.8     .05       0
  1819.3    .016       0  1885.8      .1       0
#XS Ineff= 2 , 0
         1283.05  2217.5 1629.14         2215.88
Permanent Ineff=
       F       F
Bank Sta=1422.41,1581.95
XS Rating Curve= 0 ,0
Exp/Cntr(USF)=0,0
Exp/Cntr=0.5,0.3

Type RM Length L Ch R = 3 ,35846   ,,,
BEGIN DESCRIPTION:
Huntersville Road
Bridge data: 54075KNA030
Width: 34' (measured on orthoimagery)
Railing height: 2.7'
Circular Pier width: 2'
Structure bounding sections incorporate channel data from survey.
Deck from Lidar with survey data incorporated.
Cd applied for elongated piers with semi-circular ends
END DESCRIPTION:
Bridge Culvert--1,0,-1,-1, 0
Deck Dist Width WeirC Skew NumUp NumDn MinLoCord MaxHiCord MaxSubmerge Is_Ogee
41,34,2.6,0, 60, 60, , , 0.98, 0, 0,0,,
     -20   74.22   84.97   96.37   110.6  201.58  237.91   246.4  305.81  339.51
  351.08  376.54  417.52  484.04  597.21  665.11  687.74  752.81  817.88  899.92
  960.14 1013.09 1051.04 1120.72 1163.03 1191.32 1224.59  1228.1 1231.46    1232
 1276.16 1325.05 1359.14 1469.86 1557.35 1587.14 1630.16    1670 1680.91 1685.49
 1735.32 1776.94 1801.77 1818.38 1862.67 1884.82 1924.55 1973.41 1995.56 2017.11
 2028.68 2034.39 2037.22 2040.25 2048.54 2051.82  2054.2 2057.61 2059.85    2062
 2230.14  2228.6 2228.28 2228.16 2227.81 2226.21 2225.47 2225.39 2223.93 2223.29
 2223.19 2222.68 2222.05 2220.66 2218.92 2218.01 2217.82 2217.45 2217.37  2217.5
 2217.87 2217.86 2218.13 2218.41 2218.49 2218.37 2218.52 2218.56 2221.26  2221.4
 2221.42 2221.64 2221.76 2221.67 2221.27 2220.98 2220.44 2220.13 2217.35 2217.21
 2216.64 2216.35 2216.32 2216.14 2216.01 2216.13 2216.11 2215.81 2215.78 2215.54
 2215.63 2215.53 2215.31 2215.23 2214.25 2213.72 2214.08 2214.16 2214.84  2215.2
                                                                                
                                                                                
                                                                                
          2213.7  2213.6 2213.26    2213 2212.91
                                                                                
                                                                                
      50  144.22  154.97  166.37   180.6  271.58  307.91   316.4  375.81  409.51
  421.08  446.54  470.91  483.31  487.52  554.04  587.99  635.11  667.21  720.07
  735.11  757.74  822.81  887.88  969.92 1030.14 1074.76 1083.09 1121.04 1170.79
 1190.72 1233.03 1261.32 1294.59  1298.1 1301.46    1302 1346.16 1395.05 1429.14
 1539.86 1627.35 1657.14 1700.16    1740 1750.91 1755.49 1805.32 1846.94 1871.77
 1888.38 1932.67 1954.82 1994.55 2043.41 2065.56 2087.11 2098.68 2101.56    2277
 2230.14  2228.6 2228.28 2228.16 2227.81 2226.21 2225.47 2225.39 2223.93 2223.29
 2223.19 2222.68 2222.34 2222.05 2222.05 2220.66 2220.07 2219.45 2218.92 2218.28
 2218.01 2217.82 2217.45 2217.37  2217.5 2217.87 2217.93 2217.86 2218.13 2218.26
 2218.41 2218.49 2218.37 2218.52 2218.56 2221.26  2221.4 2221.42 2221.64 2221.76
 2221.67 2221.27 2220.98 2220.44 2220.13 2217.35 2217.21 2216.64 2216.35 2216.32
 2216.14 2216.01 2216.13 2216.11 2215.81 2215.78 2215.54 2215.63 2215.52 2215.53
                                                                                
                                                                                
                                                                                
                                                                  2213.7  2213.6
 2213.26    2213 2212.91
                                                                                
Pier Skew, UpSta & Num, DnSta & Num=  ,1464.7, 2 ,1521, 2 , 0 , 0 , 0 ,,
       2       2
 2204.15  2213.7
       2       2
  2204.7  2213.7
BR Coef=-1 ,-1 , 0 ,0.9, 0 ,,,0.8,0,1.33,1,
WSPro=,,,, 1 ,,,, 0 ,,,, 0 ,,,,-1 ,-1 ,-1 , 0 , 0 , 0 , 0 , 0
BC Design=,, 0 ,, 0 ,,,,,,
BC Use User HTab Curves=0
BC User HTab FreeFlow(D)= 0

Type RM Length L Ch R = 1 ,35739   ,1429.2,1280.1,877.8
BEGIN DESCRIPTION:
Structure XS 2 - channel burned within banks
END DESCRIPTION:
XS GIS Cut Line= 3
2248949.09420244436429.5418666592247368.14912146438053.800511511
2247447.55732187 438364.21438586
#Sta/Elev= 30
       0 2256.07   300.2 2252.84   345.6 2252.66   390.8 2248.33   440.5 2224.83
   450.2  2224.5   457.2 2222.58   472.8 2211.36     513 2210.48   987.5 2209.19
  1009.8  2209.2    1372 2208.54  1521.6  2204.7 1534.53 2200.95 1574.07 2202.34
 1619.44 2197.97 1646.24 2203.77  1669.3 2208.01  1805.1 2206.86  1912.6 2205.93
  2073.8 2204.95  2137.4 2203.85  2186.3    2211  2266.6 2212.82  2278.4 2217.41
  2295.7  2248.4  2338.5 2284.71  2365.1 2309.03  2397.6 2333.53    2587 2463.75
#Mann= 15 ,-1,0
       0     .05       0   300.2      .1       0   440.5    .016       0
   450.2      .1       0     513     .05       0   987.5    .016       0
  1009.8     .05       0  1521.6     .04       0 1646.24      .1       0
  1805.1     .03       0  1912.6      .1       0  2073.8     .05       0
  2186.3    .016       0  2266.6     .03       0  2338.5      .1       0
#XS Ineff= 2 , 0
         1363.75    2217 1688.44          2215.5
Permanent Ineff=
       F       F
Bank Sta=1521.6,1646.24
XS Rating Curve= 0 ,0
Exp/Cntr(USF)=0,0
Exp/Cntr=0.5,0.3

Type RM Length L Ch R = 1 ,34458   ,252,395.3,408.8
BEGIN DESCRIPTION:
structure xs 1
END DESCRIPTION:
XS GIS Cut Line= 2
2246513.07608896436943.3960047312247113.01226202438374.822663265
#Sta/Elev= 30
       0 2362.28    59.8 2347.57    88.7 2334.43   149.4  2300.9   179.8 2279.75
   202.4 2261.35   227.5 2236.66   240.5 2219.56   253.5 2208.49   283.8 2202.62
   422.4 2204.22     508 2202.14   570.1 2204.34   808.6 2203.34  1068.9 2205.78
  1097.9 2200.25  1112.2 2199.25  1156.92199.949    1173 2200.46    1225 2201.58
  1238.4 2205.71  1260.1 2206.87  1287.3 2207.49  1294.4  2209.2  1322.2 2233.47
  1337.8  2242.8  1355.1 2263.84  1394.1 2298.61  1483.4 2351.36  1552.1 2396.19
#Mann= 7 ,-1,0
       0      .1       0   422.4     .05       0  1097.9     .04       0
  1156.9     .05       0    1173      .1       0  1260.1    .016       0
  1287.3      .1       0
#XS Ineff= 2 , 0
                         1262.87         2220.04
Permanent Ineff=
       F       F
Bank Sta=1097.9,1156.9
XS Rating Curve= 0 ,0
Exp/Cntr(USF)=0,0
Exp/Cntr=0.3,0.1

Type RM Length L Ch R = 1 ,34063   ,247.1,355.3,413.8
XS GIS Cut Line= 5
2246393.54073609437130.7068019762246419.17825479437260.372249833
2246586.93202049438033.8338051212246587.93689472438148.635778094
2246660.44816931438414.865120094
#Sta/Elev= 30
       0 2272.26      80 2247.58   112.6 2234.81   141.2 2219.15   160.6 2212.01
   170.7 2211.15   190.3  2212.9   280.3 2202.23   321.3 2201.66   566.9 2202.31
     616  2204.6   796.1    2203   812.4 2201.48   836.7 2203.32   910.6 2201.84
   920.8 2200.05     927  2198.5   971.8 2198.49     995  2198.6   997.62199.984
    1015 2206.07  1054.6 2204.55  1092.9 2204.55    1127 2205.89  1134.3 2207.79
  1150.9 2218.18  1179.2 2239.98  1213.1 2268.41  1233.8 2283.06  1314.4 2326.82
#Mann= 8 ,-1,0
       0      .1       0   321.3     .05       0   836.7      .1       0
   920.8     .04       0   997.6      .1       0  1054.6    .016       0
  1092.9     .05       0    1127      .1       0
#XS Ineff= 2 , 0
                         1025.35         2216.58
Permanent Ineff=
       F       F
Bank Sta=920.8,997.6
XS Rating Curve= 0 ,0
Exp/Cntr(USF)=0,0
Exp/Cntr=0.3,0.1

Type RM Length L Ch R = 1 ,33708   ,604.8,633.2,161.3
XS GIS Cut Line= 4
2246107.24821155437247.3444971562246312.24779702437759.843460827
2246160.26534573438268.8079488862246280.43751652438555.100473419
#Sta/Elev= 30
       0 2308.67    49.4 2298.65    88.7 2281.03   105.4  2269.3   131.4 2245.41
   148.5 2223.58   165.7 2219.23   182.9  2203.3   187.2 2201.14     282 2203.09
   334.5 2201.15   480.2 2201.01   633.5 2202.95     7602199.621   771.7 2198.07
   845.8 2199.81   883.2 2204.25   962.5 2200.25  1025.1 2200.25  1041.8 2201.12
  1055.5 2205.91  1083.6 2205.65  1131.3 2204.03  1148.6 2205.07  1157.3 2208.19
    1179 2224.14    1241 2281.17  1274.4 2303.84    1331 2337.92  1393.6 2379.85
#Mann= 8 ,-1,0
       0      .1       0     310     .05       0  721.98      .1       0
     760     .04       0   845.8      .1       0  1055.5    .016       0
  1083.6     .06       0 1243.15      .1       0
#XS Ineff= 2 , 0
                         1060.06         2225.06
Permanent Ineff=
       F       F
Bank Sta=760,845.8
XS Rating Curve= 0 ,0
Exp/Cntr(USF)=0,0
Exp/Cntr=0.3,0.1