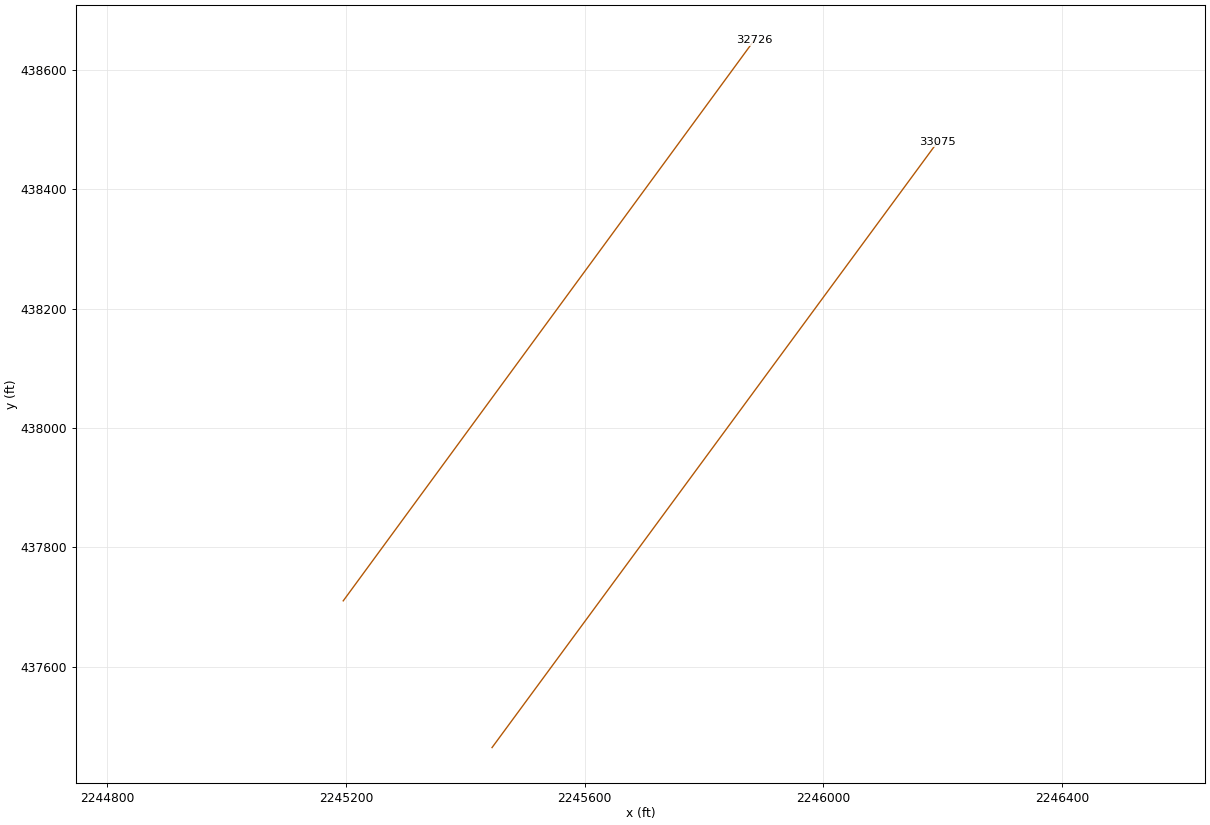
HEC-RAS study KNAPPCK.prj: KNAPPCK

--- KNAPPCK.g01 (geometry) --- (continued)

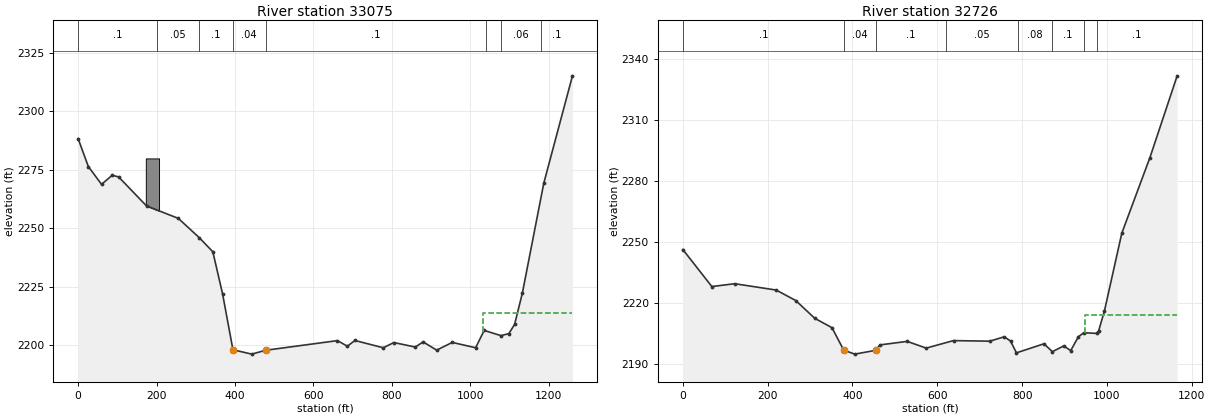
Type RM Length L Ch R = 1 ,33075   ,349.3,348.3,353.2
XS GIS Cut Line= 2
2245444.76869306437464.3932076532246192.05761039438480.074623451
#Sta/Elev= 30
       0 2288.34      26 2276.41    59.7 2268.78    86.7 2272.65   103.1 2271.99
   174.5 2259.55   255.5 2254.23   309.1 2245.95   343.6 2239.94   368.5 2221.91
   394.92198.018     443 2196.15   478.2  2197.8   661.5 2201.93   686.8 2199.54
   706.1 2201.99   778.3 2198.87   805.5  2201.1   860.1 2199.18     880 2201.38
   914.7 2197.85   954.4 2201.16    1014 2198.88  1035.8  2206.3  1078.6 2204.06
  1098.8 2204.93  1113.4 2208.87  1133.1 2222.17  1187.9 2269.32    1261 2315.21
#Mann= 8 ,-1,0
       0      .1       0     200     .05       0   309.1      .1       0
   394.9     .04       0   478.2      .1       0    1040    .016       0
  1078.6     .06       0    1180      .1       0
#XS Ineff= 2 , 0
                         1034.03         2213.59
Permanent Ineff=
       F       F
#Block Obstruct= 1 ,-1
  172.63  206.43 2279.88
Bank Sta=394.9,478.2
XS Rating Curve= 0 ,0
Exp/Cntr(USF)=0,0
Exp/Cntr=0.3,0.1

Type RM Length L Ch R = 1 ,32726   ,417.6,415.7,389.9
Node Name=K
XS GIS Cut Line= 2
2245195.35350378437710.3608022662245884.57624803 438650.53131493
#Sta/Elev= 30
       0 2246.37    68.4 2228.15   122.5 2229.53   220.1 2226.42   266.4 2221.25
     311 2212.52   351.7 2207.89   379.32196.889   405.2 2194.88   454.8 2196.74
   464.7 2199.42   529.1 2201.15   573.9 2197.84   638.3 2201.54   723.8 2201.25
   758.1 2203.42   772.7 2201.33   786.7 2195.51   851.6 2199.97   871.4 2196.09
   898.3 2198.92   914.7  2196.6   932.7 2203.42   945.8 2205.42   975.6 2205.09
   980.6 2206.38   994.1 2216.04  1035.1 2254.36  1101.5 2291.63  1165.7 2331.86
#Mann= 8 ,-1,0
       0      .1       0   379.3     .04       0   454.8      .1       0
     620     .05       0     790     .08       0     870      .1       0
   945.8    .016       0   975.6      .1       0
#XS Ineff= 2 , 0
                          947.83         2213.97
Permanent Ineff=
       F       F
Bank Sta=379.3,454.8
XS Rating Curve= 0 ,0
Exp/Cntr(USF)=0,0
Exp/Cntr=0.3,0.1