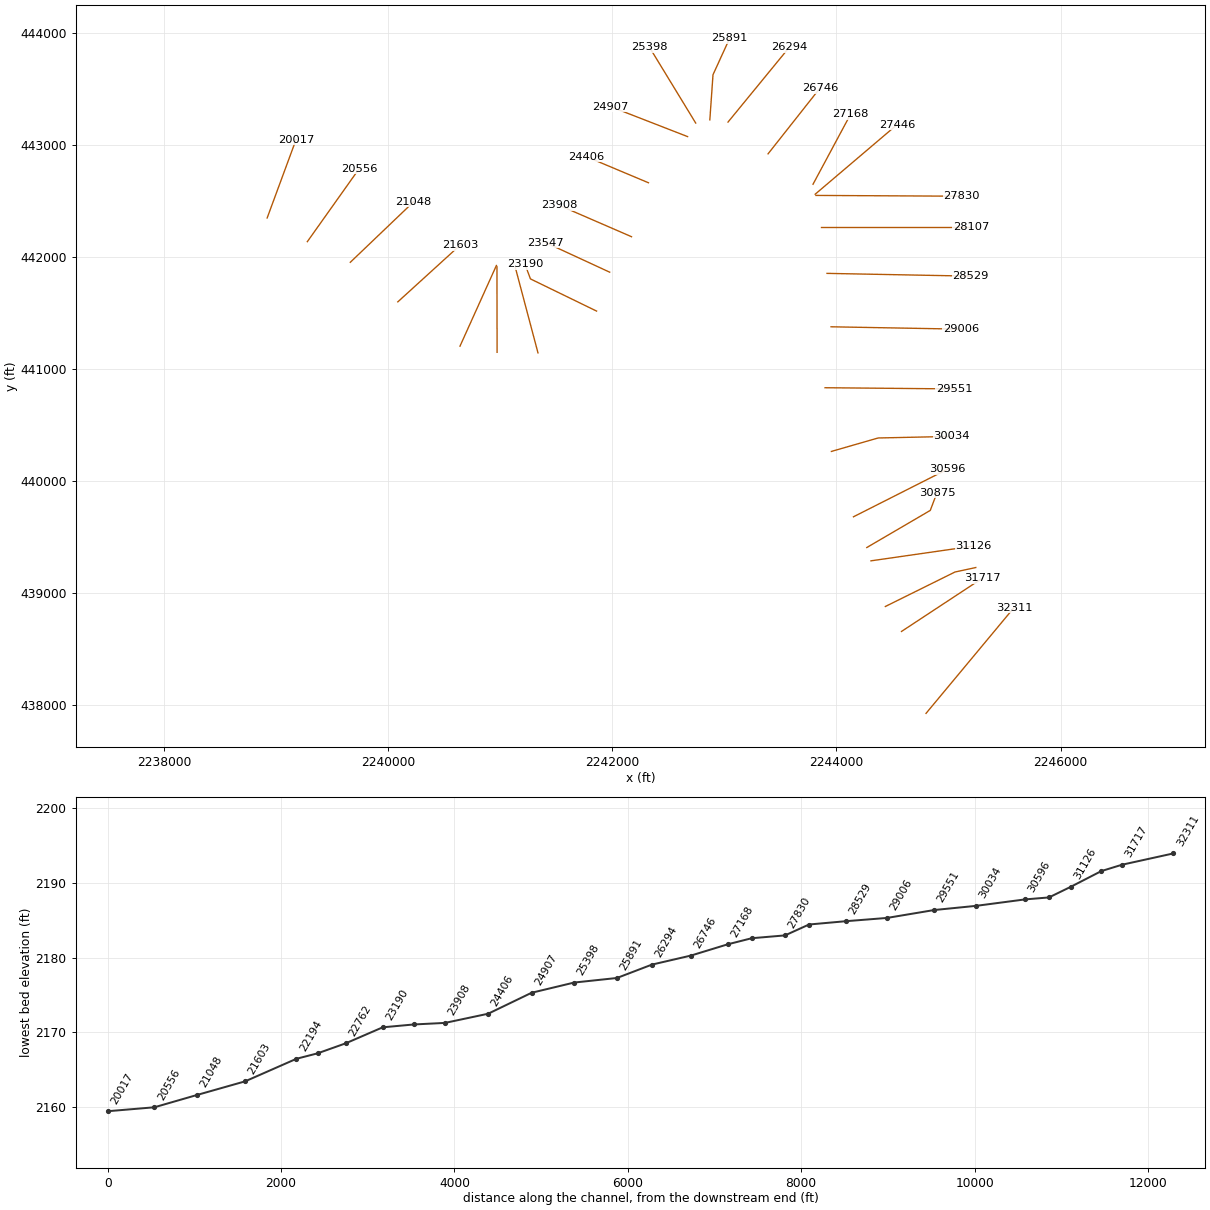
HEC-RAS study KNAPPCK.prj: KNAPPCK

--- KNAPPCK.g01 (geometry) --- (continued)

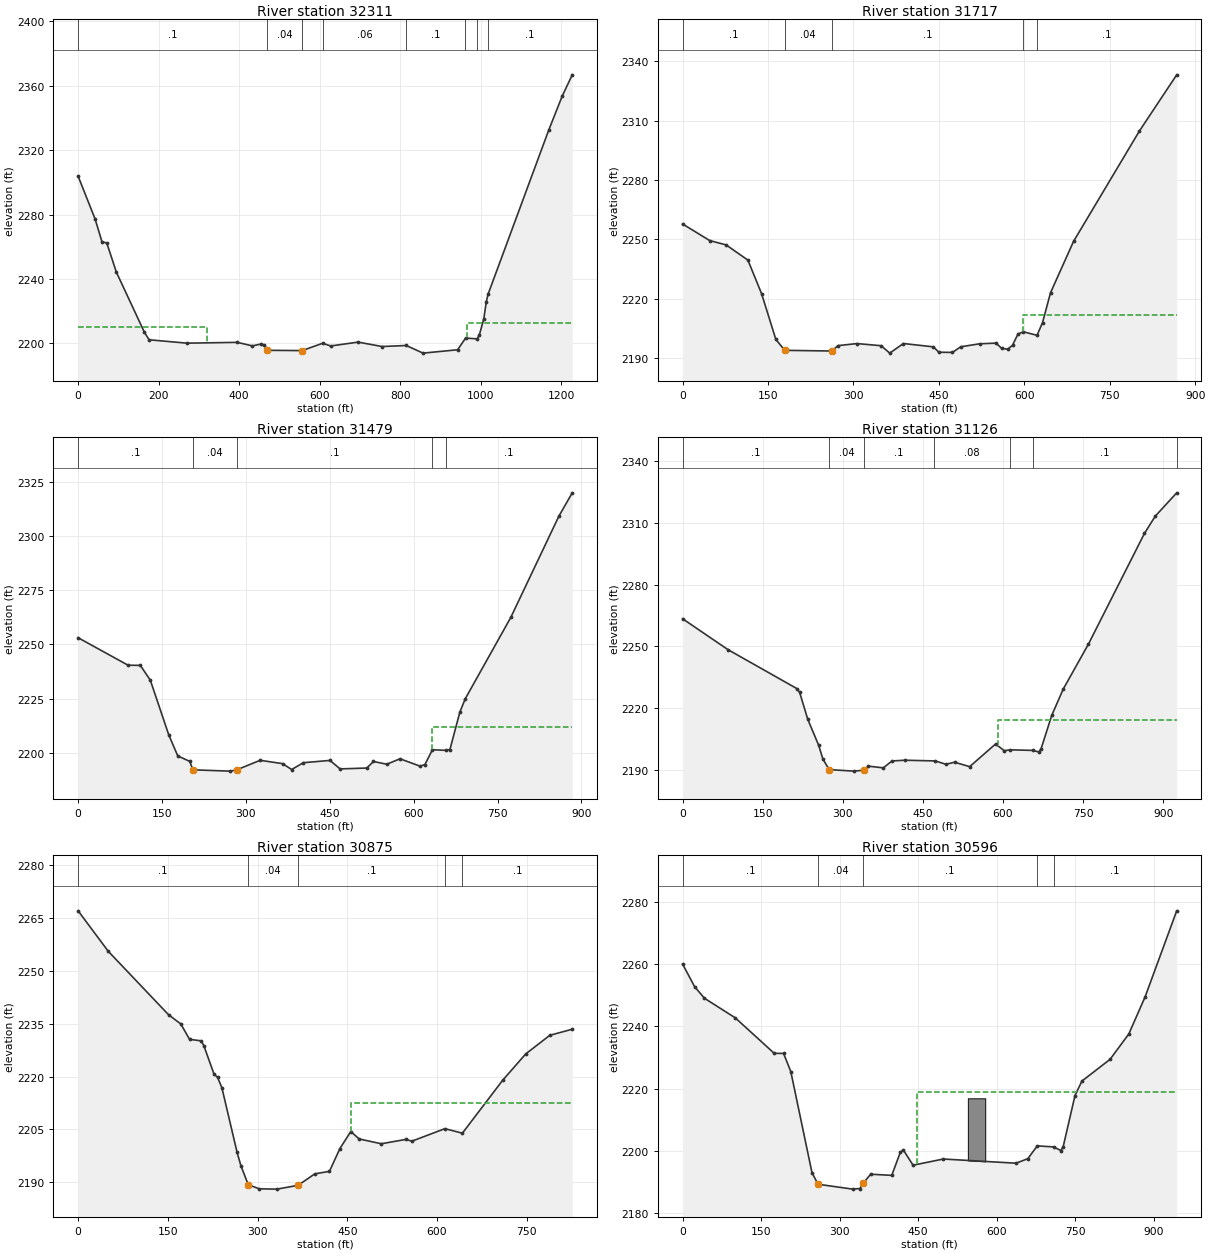
Type RM Length L Ch R = 1 ,32311   ,603.8,594,482.7
XS GIS Cut Line= 2
2244799.49223529437922.4293389572245584.14582105438866.134327233
#Sta/Elev= 30
       0 2303.89    42.2 2277.27    59.2 2263.15    71.2 2262.41    94.9 2244.32
   164.8 2206.84   176.3 2202.26   270.1 2200.16   395.2 2200.66   432.8 2198.48
   454.1 2199.62   462.6 2198.94   470.12195.717   556.3 2195.54   607.4 2200.09
   627.3 2198.42   695.5 2200.81   755.1 2198.07   815.1 2198.71   856.7 2193.97
   942.6 2196.06   962.5 2203.34   990.9 2202.83   996.6 2205.29  1007.6 2215.21
  1013.6 2225.53    1018  2230.4  1168.8 2332.44  1202.3 2353.59  1227.3 2366.86
#Mann= 8 ,-1,0
       0      .1       0   470.1     .04       0   556.3      .1       0
   607.4     .06       0   815.1      .1       0     960    .016       0
   990.9     .06       0    1018      .1       0
#XS Ineff= 2 , 0
          320.08 2210.48   966.2         2212.66
Permanent Ineff=
       F       F
Bank Sta=470.1,556.3
XS Rating Curve= 0 ,0
Exp/Cntr(USF)=0,0
Exp/Cntr=0.3,0.1

Type RM Length L Ch R = 1 ,31717   ,243.6,237.9,199.8
XS GIS Cut Line= 2
2244580.35474738438654.0657905422245304.92224774439131.219998097
#Sta/Elev= 30
       0 2257.75    47.7 2249.35    76.4 2247.18   114.7 2239.47   138.7 2222.51
   163.8 2199.36   179.42193.866     262 2193.52   272.8 2196.24   306.3 2197.28
   348.6  2196.2   363.8 2192.45   387.7 2197.31   440.4 2195.62     450  2192.9
   473.9  2192.8   488.3 2195.66   521.8 2197.18   550.6  2197.5   560.1 2194.89
     571 2194.42   579.3 2196.42   588.9 2202.12   598.5 2203.23   622.4 2201.46
     632 2207.88   646.1 2223.03   686.5 2248.96     802  2304.7   867.6 2333.16
#Mann= 5 ,-1,0
       0      .1       0   179.4     .04       0     262      .1       0
   598.5    .016       0   622.4      .1       0
#XS Ineff= 2 , 0
                          597.18         2211.96
Permanent Ineff=
       F       F
Bank Sta=179.4,262
XS Rating Curve= 0 ,0
Exp/Cntr(USF)=0,0
Exp/Cntr=0.3,0.1

Type RM Length L Ch R = 1 ,31479   ,367.1,353.1,275.7
XS GIS Cut Line= 3
   2244436.53148438877.1837980542245057.82726279439185.098716799
 2245243.6694031439225.182315689
#Sta/Elev= 30
       0 2253.06    89.3  2240.4   111.2 2240.33   129.1 2233.49   162.1 2208.28
   178.2 2198.58   199.7 2196.09     205  2192.2   271.9  2191.6   283.3 2192.16
   325.5 2196.59   365.7 2195.04   381.8 2192.33   402.7 2195.49   450.4 2196.53
   468.4 2192.63   516.1 2193.02   528.1 2196.05   551.9 2194.77   575.5 2197.29
   611.6 2193.86   620.1 2194.64   633.5 2201.46   657.6 2201.17   664.8 2201.56
   682.6 2218.83   692.2 2224.94   773.6 2262.41   859.5 2309.02   883.5 2319.83
#Mann= 5 ,-1,0
       0      .1       0     205     .04       0   283.3      .1       0
   633.5    .016       0   657.6      .1       0
#XS Ineff= 2 , 0
                          633.24         2212.01
Permanent Ineff=
       F       F
Bank Sta=205,283.3
XS Rating Curve= 0 ,0
Exp/Cntr(USF)=0,0
Exp/Cntr=0.3,0.1

Type RM Length L Ch R = 1 ,31126   ,231.2,250.4,300.1
XS GIS Cut Line= 2
2244308.12575386439285.0956572452245223.81780749439416.660607478
#Sta/Elev= 30
       0 2263.46    84.9 2248.47   214.2 2229.52   219.2 2227.69   234.4 2214.62
   254.8 2202.02   262.7 2195.37   274.42190.222   320.9 2189.49   339.5 2189.97
   347.6 2191.91   375.9 2191.08     392 2194.42   416.3 2194.79   472.9 2194.44
   493.1 2192.81   509.2 2193.82   537.5 2191.66     586 2202.67   602.2 2199.41
   613.4 2199.83   655.9 2199.55   666.8  2198.8   670.9  2200.1   691.1 2216.53
   712.5 2229.24   759.8 2251.13   864.8 2304.92     885 2313.26   925.1 2324.58
#Mann= 7 ,-1,0
       0      .1       0   274.4     .04       0   339.5      .1       0
     470     .08       0   613.4    .016       0   655.9      .1       0
   925.1      .1       0
#XS Ineff= 2 , 0
                          590.99         2214.17
Permanent Ineff=
       F       F
Bank Sta=274.4,339.5
XS Rating Curve= 0 ,0
Exp/Cntr(USF)=0,0
Exp/Cntr=0.3,0.1

Type RM Length L Ch R = 1 ,30875   ,282.3,279.1,274.5
BEGIN DESCRIPTION:
Sudden contraction in the floodplain, updated the coefficents to 0.3 and 0.5
END DESCRIPTION:
XS GIS Cut Line= 3
2244270.73113914439403.736528926 2244837.3674689439735.337210651
2244897.49286723439893.849624443
#Sta/Elev= 30
       0 2267.08    50.4 2255.59   151.2 2237.58   171.7 2234.96   186.3  2230.6
   205.6 2230.17   210.2  2228.8   227.2 2220.72   233.1 2219.81   240.4 2216.83
   265.8 2198.48   272.1 2194.75   284.4 2189.33   302.9 2188.16   332.5 2188.07
   367.8 2189.15   395.6  2192.4   420.2 2193.12   437.7  2199.6   455.9 2204.43
   469.8 2202.32   506.8 2200.95   548.6  2202.2   557.8 2201.67   613.2 2205.24
   642.4 2203.95   709.8 2218.98   748.3 2226.45   788.5 2231.73   826.1 2233.47
#Mann= 5 ,-1,0
       0      .1       0   284.4     .04       0   367.8      .1       0
   613.2    .016       0   642.4      .1       0
#XS Ineff= 2 , 0
                           456.9         2212.41
Permanent Ineff=
       F       F
Bank Sta=284.4,367.8
XS Rating Curve= 0 ,0
Exp/Cntr(USF)=0,0
Exp/Cntr=0.5,0.3

Type RM Length L Ch R = 1 ,30596   ,570,561.9,535.3
XS GIS Cut Line= 2
2244151.74124354 439678.375308812244993.75692503440104.645747565
#Sta/Elev= 30
       0 2259.97    22.9 2252.73    41.6 2249.01   100.6 2242.72     175 2231.34
   192.9  2231.3   206.7 2225.49   247.1 2193.12   258.6 2189.37     325  2187.8
   338.8 2187.99   344.7 2189.62   359.2 2192.58   399.5 2192.21   416.1 2199.68
   421.9  2200.3   440.2 2195.47   498.1 2197.45   637.1 2196.11   659.5 2197.58
   677.5 2201.67   708.9 2201.33   722.3 2200.18   726.8 2201.28   749.5 2217.79
   762.7 2222.44   816.5 2229.41   852.3 2237.54   883.5 2249.46   943.8 2277.02
#Mann= 5 ,-1,0
       0      .1       0   258.6     .04       0   344.7      .1       0
   677.5    .016       0   708.9      .1       0
#XS Ineff= 2 , 0
                           447.5         2218.97
Permanent Ineff=
       F       F
#Block Obstruct= 1 ,-1
  544.84  578.09 2216.92
Bank Sta=258.6,344.7
XS Rating Curve= 0 ,0
Exp/Cntr(USF)=0,0
Exp/Cntr=0.5,0.3

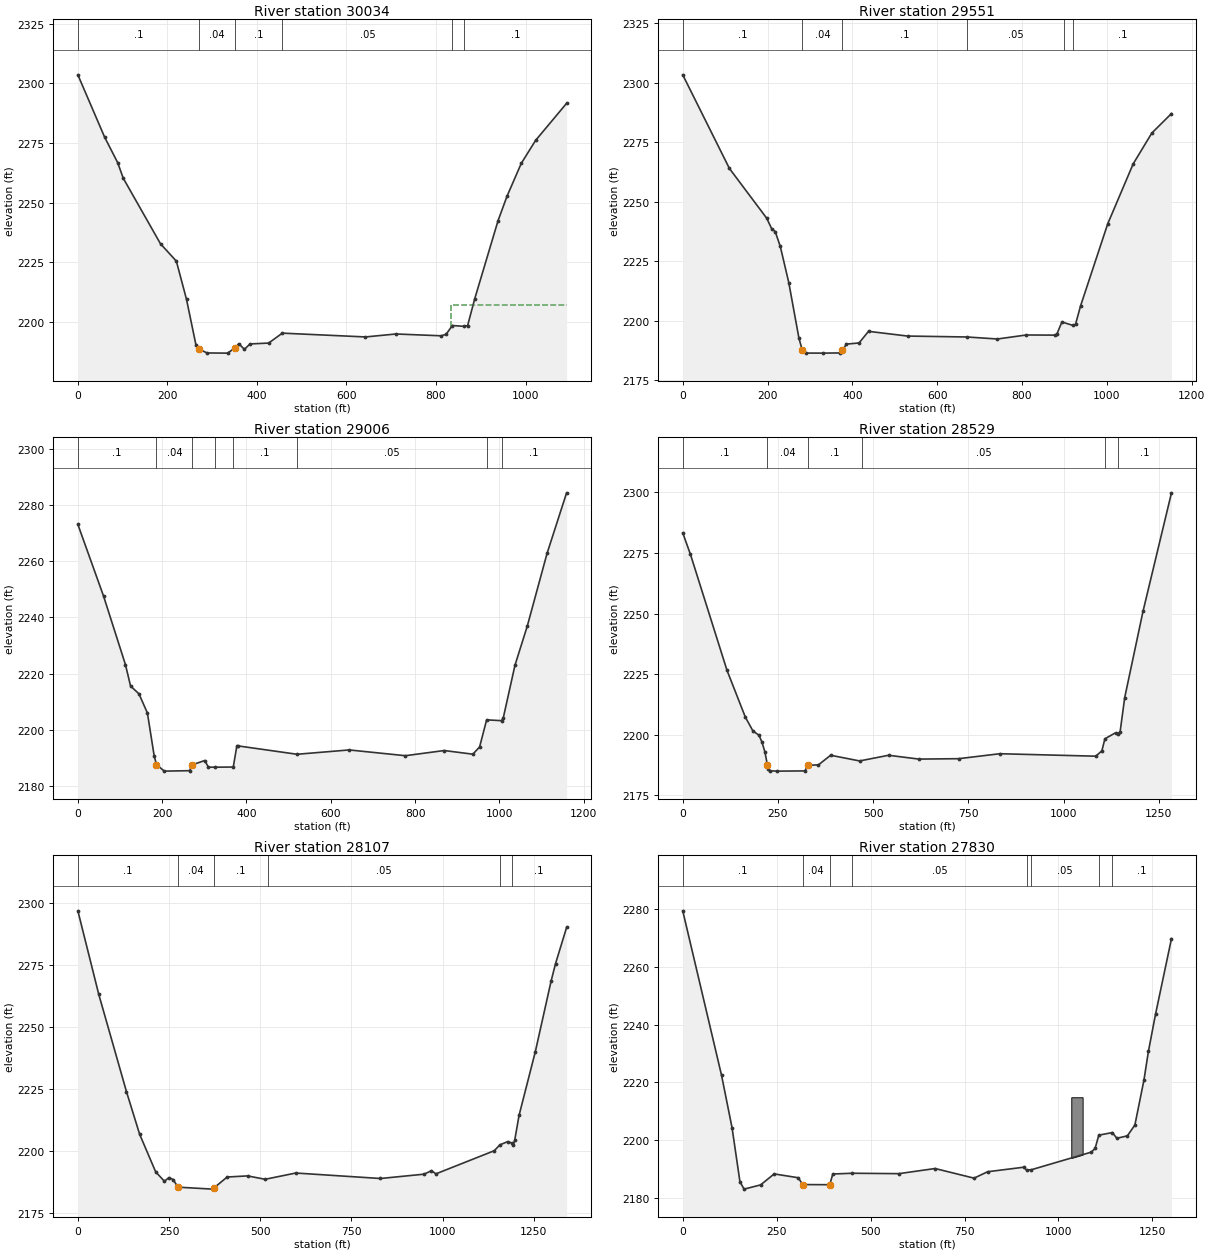
Type RM Length L Ch R = 1 ,30034   ,495.6,483.5,443.2
XS GIS Cut Line= 3
2243954.75256414440262.252193784 2244371.8206863440382.424364576
2245029.23315004440396.562267022
#Sta/Elev= 30
       0 2303.51    59.8  2277.4    88.9 2266.74   101.4  2260.2   184.6 2232.73
     220 2225.47   242.7 2209.44   263.7 2190.43   269.92188.676   288.7 2187.01
   334.5 2186.94   351.1 2189.14   359.5 2190.88     372 2188.53   384.5 2190.79
   426.1 2191.15   456.7 2195.31   642.4 2193.72   710.5 2194.96   811.8  2194.2
   822.5 2194.84   836.4  2198.5   862.5 2198.17   870.5 2198.45   886.5 2209.77
   938.5 2242.41   958.5 2252.65   990.5 2266.47  1022.5 2276.08  1091.6 2291.58
#Mann= 6 ,-1,0
       0      .1       0   269.9     .04       0   351.1      .1       0
   456.7     .05       0   836.4    .016       0   862.5      .1       0
#XS Ineff= 2 , 0
                          833.58         2207.09
Permanent Ineff=
       F       F
Bank Sta=269.9,351.1
XS Rating Curve= 0 ,0
Exp/Cntr(USF)=0,0
Exp/Cntr=0.3,0.1

Type RM Length L Ch R = 1 ,29551   ,545.4,544.9,541.1
XS GIS Cut Line= 2
2243898.20095435440831.3027672392245050.44000371440820.699340404
#Sta/Elev= 30
       0 2303.26     110 2263.95     198 2243.03     210  2238.5     218 2237.43
     230 2231.18     250 2216.01     274 2192.61     282 2187.53     290 2186.41
     330 2186.38     370 2186.46   376.6 2187.56     386 2190.17   415.7 2190.65
     438 2195.53     530 2193.55     670 2193.16     742 2192.32     810    2194
     878 2193.94     882 2194.36     894 2199.47   920.4 2197.99     926 2198.44
     938 2206.25    1002  2240.7    1062 2265.87    1106 2278.82  1152.3    2287
#Mann= 6 ,-1,0
       0      .1       0     282     .04       0   376.6      .1       0
     670     .05       0     900    .016       0   920.4      .1       0
Bank Sta=282,376.6
XS Rating Curve= 0 ,0
Exp/Cntr(USF)=0,0
Exp/Cntr=0.3,0.1

Type RM Length L Ch R = 1 ,29006   ,476.6,476.5,476.9
Node Name=J
XS GIS Cut Line= 2
2243951.21808852441375.612011413 2245110.5260891441354.405157744
#Sta/Elev= 30
       0 2273.13      61  2247.6     113 2223.18     125 2215.64     145 2212.81
     165 2206.02     181 2190.82   186.52187.655     205 2185.32     265 2185.48
   271.5 2187.58     301 2189.09   309.8 2186.73  325.54 2186.72   368.7 2186.78
     377 2194.09     381 2194.28   520.1 2191.32   643.7 2192.86   777.1 2190.81
   869.1 2192.65   937.1 2191.35   953.1 2193.93   969.8 2203.57  1005.1 2203.28
  1009.1 2204.15  1037.1 2223.05  1066.2 2236.92  1113.1 2262.79  1159.5 2284.37
#Mann= 8 ,-1,0
       0      .1       0   186.5     .04       0   271.5      .1       0
  325.54     .04       0   368.7      .1       0   520.1     .05       0
   969.8    .016       0  1005.1      .1       0
Bank Sta=186.5,271.5
XS Rating Curve= 0 ,0
Exp/Cntr(USF)=0,0
Exp/Cntr=0.3,0.1

Type RM Length L Ch R = 1 ,28529   ,423.9,422.1,432
XS GIS Cut Line= 2
2243915.87333241441852.7662189682245198.88797939441828.024889688
#Sta/Elev= 30
       0 2283.32    20.3  2274.4   116.3 2226.48   164.3 2207.22   184.3 2201.47
   200.1 2199.72   207.9 2196.93   215.8  2192.8   222.1 2187.54   224.3 2185.62
   228.3    2185   248.3 2184.88   320.4 2184.97   329.6 2187.29   356.4 2187.48
   388.4 2191.44   464.4 2189.09   540.4 2191.43   620.4 2189.85   724.4 2190.02
   832.5 2192.07  1084.5 2191.05  1100.5 2193.27  1108.5 2198.24  1136.5 2200.74
    1143 2200.15  1148.5 2201.23  1160.5 2215.28  1208.5 2250.88  1283.3 2299.86
#Mann= 6 ,-1,0
       0      .1       0   222.1     .04       0   329.6      .1       0
     470     .05       0  1108.5    .016       0    1143      .1       0
Bank Sta=222.1,329.6
XS Rating Curve= 0 ,0
Exp/Cntr(USF)=0,0
Exp/Cntr=0.3,0.1

Type RM Length L Ch R = 1 ,28107   ,290.1,277.4,279.8
XS GIS Cut Line= 2
2243862.85619824442269.834341128  2245202.422455442269.834341128
#Sta/Elev= 30
       0 2296.77    57.3 2263.05   133.3 2223.77   169.3  2206.6   213.3 2191.41
   237.3 2187.61   249.3 2189.07   261.3 2188.32   274.32185.236   369.3 2184.44
   373.3 2184.96   409.3 2189.33   465.3 2189.78   513.3 2188.41   597.3 2190.94
   829.3 2188.73   949.3 2190.48   969.3  2191.9   981.3  2190.6  1141.3 2199.94
  1156.7  2202.3    1178 2203.62  1189.3 2203.05  1193.3 2202.23  1197.3 2204.08
  1209.3 2214.22    1254 2239.99  1297.3 2268.53  1309.3 2275.47  1339.6 2290.06
#Mann= 6 ,-1,0
       0      .1       0   274.3     .04       0   373.3      .1       0
     520     .05       0  1156.7    .016       0  1189.3      .1       0
Bank Sta=274.3,373.3
XS Rating Curve= 0 ,0
Exp/Cntr(USF)=0,0
Exp/Cntr=0.3,0.1

Type RM Length L Ch R = 1 ,27830   ,140.5,384.1,498.4
XS GIS Cut Line= 2
2243816.90801529442549.0579144382245117.59504033442541.988963215
#Sta/Elev= 30
       0  2279.4   103.3 2222.39   131.3  2204.2   152.2 2185.55   163.3 2182.98
   207.3 2184.45   243.3 2188.25   307.3 2186.93   319.3 2184.56   391.3 2184.51
   399.3 2188.22   451.3 2188.48   575.3 2188.34   671.5 2190.12   775.3 2186.78
   811.3    2189   907.3 2190.57   915.3 2189.57   927.3 2189.68  1087.3  2195.8
  1097.4 2197.09  1107.3 2201.67  1143.3 2202.58  1155.3  2200.6  1183.3 2201.44
  1203.3  2205.2  1227.3 2220.68  1239.3  2230.7  1258.2 2243.57  1300.7 2269.78
#Mann= 8 ,-1,0
       0      .1       0   319.3     .04       0   391.3      .1       0
   451.3     .05       0   915.3    .045       0   927.3     .05       0
  1107.3    .016       0  1143.3      .1       0
#Block Obstruct= 1 ,-1
    1034 1064.21 2214.81
Bank Sta=319.3,391.3
XS Rating Curve= 0 ,0
Exp/Cntr(USF)=0,0
Exp/Cntr=0.3,0.1

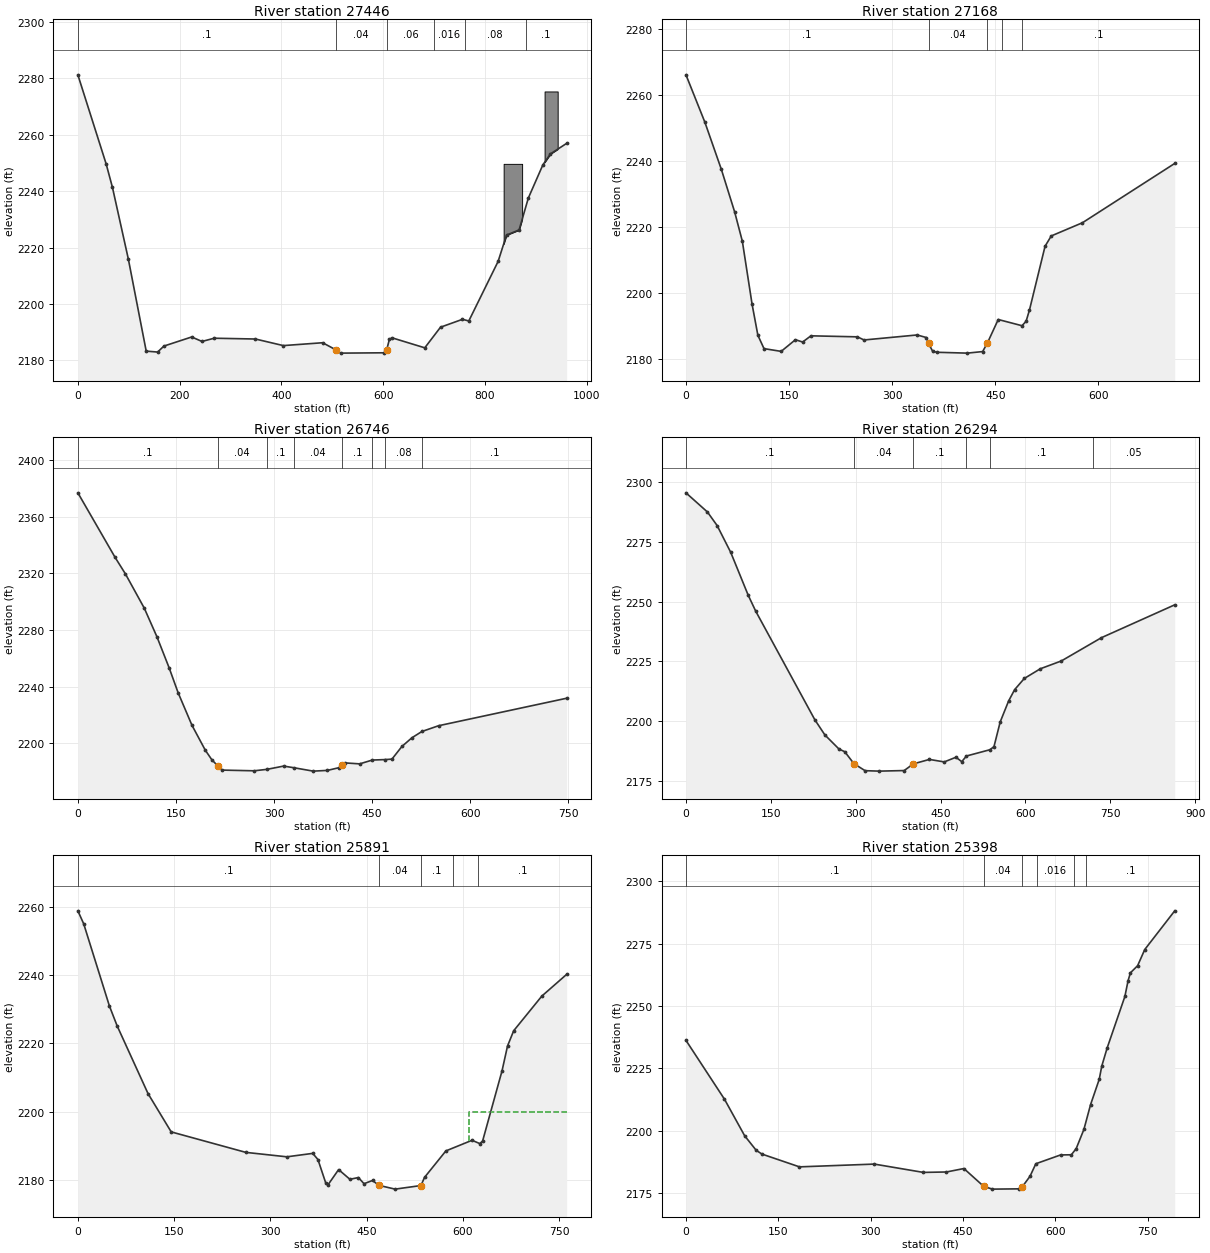
Type RM Length L Ch R = 1 ,27446   ,129.1,277.8,310.1
XS GIS Cut Line= 2
2243809.83906406442559.6613412732244541.47551565  443181.7290489
#Sta/Elev= 30
       0  2281.2    55.6 2249.63      68 2241.29    99.2 2215.93   134.3 2183.31
   156.7 2182.98   169.1  2185.1   223.6 2188.32   243.9 2186.74   267.9 2187.88
   348.9  2187.6   403.7 2185.27   480.9 2186.28   506.32183.833   516.4  2182.6
   601.6 2182.72   606.9 2183.85   612.1  2187.5   617.4 2188.02   681.6 2184.48
   712.5 2191.78   755.7 2194.58   768.1 2193.99   825.7  2215.1   842.2 2224.43
   866.9 2226.24   885.1 2237.56   913.6 2249.29   928.6  2253.2   960.3 2256.91
#Mann= 6 ,-1,0
       0      .1       0   506.3     .04       0   606.9     .06       0
     700    .016       0     760     .08       0     880      .1       0
#Block Obstruct= 2 ,-1
  836.55  872.87 2249.66  916.99  942.69 2275.31
Bank Sta=506.3,606.9
XS Rating Curve= 0 ,0
Exp/Cntr(USF)=0,0
Exp/Cntr=0.3,0.1

Type RM Length L Ch R = 1 ,27168   ,461.9,421.9,408.5
XS GIS Cut Line= 2
2243790.73421292442648.9198302532244126.67994654443275.403685809
#Sta/Elev= 30
       0 2266.21    27.5 2251.84    51.5 2237.51    70.8 2224.63      82 2215.73
    96.2 2196.57   104.6 2187.19   113.5 2183.15   138.5 2182.31   159.2 2185.85
   169.7 2185.15   181.8 2187.03   249.4 2186.72     259 2185.77   336.2 2187.29
   349.8  2186.5   352.8 2184.74   358.7 2182.38   364.7 2182.04     409 2181.78
   431.5 2182.25   438.5 2184.89   454.2 2191.98   488.7  2190.1   494.7 2191.43
   499.6 2194.85   522.3 2214.21   531.3 2217.33   576.7 2221.34   710.9 2239.33
#Mann= 5 ,-1,0
       0      .1       0   352.8     .04       0   438.5     .06       0
     460    .016       0   488.7      .1       0
Bank Sta=352.8,438.5
XS Rating Curve= 0 ,0
Exp/Cntr(USF)=0,0
Exp/Cntr=0.3,0.1

Type RM Length L Ch R = 1 ,26746   ,459,452.4,450.5
XS GIS Cut Line= 2
2243389.23646629442920.177853648 2243852.2527714 443506.90080516
#Sta/Elev= 30
       0 2376.93    56.9 2331.35    72.6 2319.75   101.6 2295.42     121 2275.13
   139.5 2253.38   153.3  2235.7   174.5 2212.67   194.9 2195.05     205 2188.23
   213.72184.135   220.4 2181.01   269.5 2180.51   288.8 2181.51   314.7 2183.84
   330.3 2182.68   359.9 2180.28   381.6 2180.79   398.7 2182.65   404.4 2184.28
   408.9 2186.08   430.9 2185.41   450.3 2188.11   470.1 2188.44   480.3 2188.77
   495.5  2197.7   510.8 2203.84   526.1 2208.29   551.6 2212.36   747.4 2231.78
#Mann= 8 ,-1,0
       0      .1       0   213.7     .04       0   288.8      .1       0
   330.3     .04       0   404.4      .1       0   450.3    .016       0
   470.1     .08       0   526.1      .1       0
Bank Sta=213.7,404.4
XS Rating Curve= 0 ,0
Exp/Cntr(USF)=0,0
Exp/Cntr=0.3,0.1

Type RM Length L Ch R = 1 ,26294   ,342.1,402.4,424.9
Node Name=I
XS GIS Cut Line= 2
2243031.82486816443204.0030517882243579.13506113443872.352998971
#Sta/Elev= 30
       0 2295.63      38 2287.59    55.1 2281.92    79.1 2270.71   110.1 2252.69
   123.3 2246.06   227.8 2200.57   245.5 2194.23   270.4 2188.33   280.7 2187.18
   296.92182.177   316.6 2179.25   341.5 2179.06   385.7  2179.3   401.9  2182.1
   430.3 2183.96   456.5 2182.92   477.2 2184.87   487.5 2183.02   495.7 2185.39
   537.2 2188.02   544.4 2189.31   555.4 2199.66   570.2  2208.4   580.9 2213.18
     598 2217.87   626.4 2221.94   663.5 2225.21   734.4 2234.96   863.9 2248.72
#Mann= 6 ,-1,0
       0      .1       0   296.9     .04       0   401.9      .1       0
   495.7    .016       0   537.2      .1       0     720     .05       0
Bank Sta=296.9,401.9
XS Rating Curve= 0 ,0
Exp/Cntr(USF)=0,0
Exp/Cntr=0.3,0.1

Type RM Length L Ch R = 1 ,25891   ,329.8,493.2,528.1
XS GIS Cut Line= 3
 2242869.6685514443224.1427562382242897.94435629443627.072975952
2243046.39233198443952.244732212
#Sta/Elev= 30
       0 2258.76     9.1 2254.96    49.2 2230.87    61.2 2225.07   109.3 2205.25
   145.4 2194.03   261.7 2188.03   325.6 2186.73   365.9 2187.74     374 2185.93
     386 2179.16     390 2178.62   406.2 2182.99   423.8 2180.15     437 2180.66
   445.8 2178.86     459  2179.8     4692178.371   494.2 2177.27   534.5 2178.32
     540  2180.7   573.3 2188.46     614 2191.57   626.1 2190.61   630.5 2191.35
   660.8 2211.92   669.3 2219.16   678.9 2223.64   722.8  2233.8   761.4 2240.15
#Mann= 5 ,-1,0
       0      .1       0     469     .04       0   534.5      .1       0
  583.92    .016       0  623.92      .1       0
#XS Ineff= 2 , 0
                           609.8         2199.95
Permanent Ineff=
       F       F
Bank Sta=469,534.5
XS Rating Curve= 0 ,0
Exp/Cntr(USF)=0,0
Exp/Cntr=0.3,0.1

Type RM Length L Ch R = 1 ,25398   ,367.9,491.1,514.3
XS GIS Cut Line= 2
2242743.32779189443195.7535938792242330.02179334443873.924659738
#Sta/Elev= 30
       0 2236.27    62.6 2212.68    95.4 2198.03   114.1 2192.22   123.5  2190.7
   184.4 2185.58   306.1 2186.69   385.8 2183.36   423.3 2183.53   451.6 2184.91
   483.82177.767     498 2176.66   540.4 2176.77   546.5 2177.61   559.1 2181.83
   568.5 2186.83   608.7 2190.36   626.2 2190.42   634.1  2192.9   646.6 2200.58
   657.5 2210.56   671.5 2220.65   675.7    2226   684.4 2233.23   713.2 2253.86
   718.4 2260.19   722.2 2263.33   733.9 2266.19   745.5 2272.67   794.2 2288.17
#Mann= 6 ,-1,0
       0      .1       0   483.8     .04       0   546.5      .1       0
     570    .016       0     630     .08       0     650      .1       0
Bank Sta=483.8,546.5
XS Rating Curve= 0 ,0
Exp/Cntr(USF)=0,0
Exp/Cntr=0.3,0.1

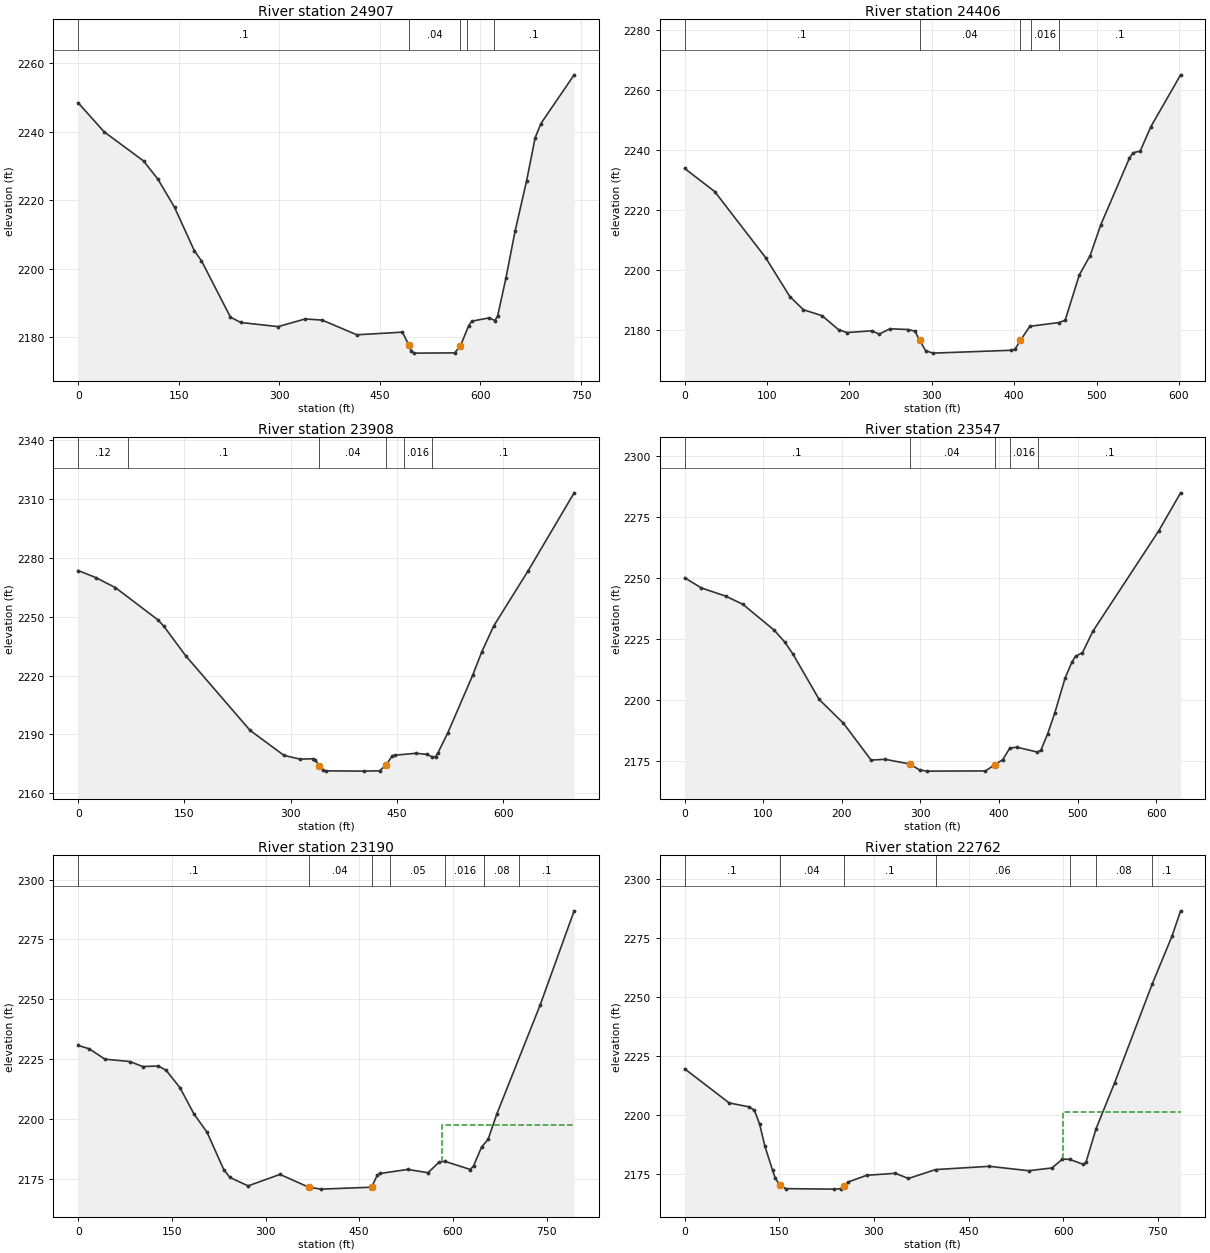
Type RM Length L Ch R = 1 ,24907   ,506,501.3,500.5
XS GIS Cut Line= 2
2242671.37954215443074.3226855852241981.97920293 443342.71518406
#Sta/Elev= 30
       0 2248.41    38.7 2239.93    97.4 2231.45     119 2226.08   143.7 2217.88
   173.3 2205.18   183.9 2202.25   227.1  2185.8   242.6 2184.24   298.2 2183.03
   338.6 2185.28     364 2184.94   415.5 2180.65   483.6 2181.41   493.12177.672
   497.1  2175.8   501.4 2175.29   561.5 2175.36   570.2  2177.4   582.4 2183.31
   587.2 2184.62     613 2185.59   621.6 2184.81   625.7 2186.16   638.1 2197.29
   651.6 2210.85   668.8 2225.57   681.6 2238.19   690.2 2242.36   739.8 2256.59
#Mann= 5 ,-1,0
       0      .1       0   493.1     .04       0   570.2      .1       0
     580    .016       0     620      .1       0
Bank Sta=493.1,570.2
XS Rating Curve= 0 ,0
Exp/Cntr(USF)=0,0
Exp/Cntr=0.3,0.1

Type RM Length L Ch R = 1 ,24406   ,499.5,498,497.2
XS GIS Cut Line= 2
2242321.82483161442662.161134007 2241766.9121606442895.436524367
#Sta/Elev= 30
       0 2233.84    36.5 2226.15    98.3  2204.2   127.6 2191.29   144.1 2186.91
   166.7 2184.92   186.9 2180.26     197 2179.31   227.4 2179.91   236.1  2178.8
   249.1 2180.57   270.8 2180.33   279.5 2179.79   285.22176.714   292.5 2173.32
   301.2 2172.48   396.6 2173.43     401 2173.77   407.52176.716     419 2181.39
   454.1 2182.63   461.8 2183.38   479.1 2198.51   492.1 2204.85   505.1 2215.13
   539.8 2237.24   544.2 2239.05   552.9  2239.6   565.9 2247.73     602 2264.95
#Mann= 5 ,-1,0
       0      .1       0   285.2     .04       0   407.5      .1       0
     420    .016       0   454.1      .1       0
Bank Sta=285.2,407.5
XS Rating Curve= 0 ,0
Exp/Cntr(USF)=0,0
Exp/Cntr=0.3,0.1

Type RM Length L Ch R = 1 ,23908   ,362.7,360.4,358.6
XS GIS Cut Line= 2
2242170.72865393 442180.235684162241528.69169679442459.153378654
#Sta/Elev= 30
       0 2273.56    24.6    2270    52.6 2264.83   112.1 2248.51   120.5 2245.33
   151.6 2230.15   242.6 2192.02   290.6 2179.25   313.6 2177.34     331 2177.57
   334.1 2177.09   340.32174.115   346.2 2171.74   349.3 2171.38   403.9 2171.25
   425.3 2171.42     434  2174.2   443.3 2179.01   446.5 2179.36     477 2180.36
   492.2 2179.78     500 2178.47   504.3 2178.63   507.4 2180.33   521.8 2190.88
   556.7 2220.11   569.7 2232.16   586.4 2245.24   635.2 2273.52     700 2313.19
#Mann= 6 ,-1,0
       0     .12       0      70      .1       0   340.3     .04       0
     434      .1       0     460    .016       0     500      .1       0
Bank Sta=340.3,434
XS Rating Curve= 0 ,0
Exp/Cntr(USF)=0,0
Exp/Cntr=0.3,0.1

Type RM Length L Ch R = 1 ,23547   ,358.8,357.4,365.5
Node Name=H
XS GIS Cut Line= 2
2241975.44622168441863.3696458032241402.86117262442128.455316667
#Sta/Elev= 30
       0 2250.15    21.2 2245.96      52 2242.64    74.1 2239.26   113.8 2228.73
   127.4 2223.81   137.6    2219   171.1 2200.35     202 2190.63   237.2 2175.56
   254.9 2175.88   286.12173.984   298.9 2171.53   308.1 2171.04   382.7 2171.12
   394.7 2173.71   404.6  2175.7   413.6 2180.41   422.4 2180.85   448.8 2178.83
   453.2 2179.58   461.8 2186.29   470.8 2194.75   484.1 2209.17   492.9 2215.78
   497.3 2218.02   506.1 2219.49   519.3 2228.22   603.1 2269.31     631 2284.87
#Mann= 5 ,-1,0
       0      .1       0   286.1     .04       0   394.7     .08       0
   413.6    .016       0     450      .1       0
Bank Sta=286.1,394.7
XS Rating Curve= 0 ,0
Exp/Cntr(USF)=0,0
Exp/Cntr=0.3,0.1

Type RM Length L Ch R = 1 ,23190   ,498.2,427.7,206.8
XS GIS Cut Line= 3
2241858.66371061441515.9678282992241268.55109938441803.283560407
2241220.23945991441932.417148379
#Sta/Elev= 30
       0 2230.69    17.7 2229.28    42.8 2224.95    82.8 2223.97   103.3 2221.87
   128.4 2222.11   140.7 2220.33   162.9 2213.07   185.5 2201.99   206.2 2194.49
   233.2 2178.75     243 2175.52   272.1 2172.02   323.1 2176.81   368.8 2171.51
   388.8 2170.66   469.9 2171.46   478.8 2176.45   483.3  2177.2   527.7 2178.89
   560.2 2177.51   578.4 2182.05   587.6 2182.24   628.1 2178.85   633.3  2180.5
   646.1 2188.33   656.3 2191.41   670.5 2202.15   739.5 2247.41   794.2 2286.93
#Mann= 7 ,-1,0
       0      .1       0   368.8     .04       0   469.9      .1       0
     500     .05       0   587.6    .016       0     650     .08       0
  706.34      .1       0
#XS Ineff= 2 , 0
                          582.76         2197.46
Permanent Ineff=
       F       F
Bank Sta=368.8,469.9
XS Rating Curve= 0 ,0
Exp/Cntr(USF)=0,0
Exp/Cntr=0.3,0.1

Type RM Length L Ch R = 1 ,22762   ,339,324.3,228.5
XS GIS Cut Line= 2
  2241335.706136441142.3366210532241134.24102614 441902.24887753
#Sta/Elev= 30
       0 2219.54    70.6 2205.05   102.3 2203.39   110.5 2201.96   118.8 2196.09
   127.1 2186.79   139.3 2176.52   143.6 2173.15   150.72170.338   160.2 2168.72
   237.5 2168.51   247.1 2168.69   252.4  2169.9   259.5 2171.57   288.5 2174.37
     334 2175.22   354.7 2173.02   397.7  2176.8     483 2178.19   545.2 2176.32
   582.3 2177.49   598.8 2181.25   610.3 2181.13   631.9 2179.03   636.1 2179.86
   652.2 2194.16   681.6 2213.63   741.2 2255.52   772.6 2275.85   786.2 2286.54
#Mann= 7 ,-1,0
       0      .1       0   150.7     .04       0   252.4      .1       0
   397.7     .06       0   610.3    .016       0   652.2     .08       0
   741.2      .1       0
#XS Ineff= 2 , 0
                          599.44         2201.33
Permanent Ineff=
       F       F
Bank Sta=150.7,252.4
XS Rating Curve= 0 ,0
Exp/Cntr(USF)=0,0
Exp/Cntr=0.3,0.1

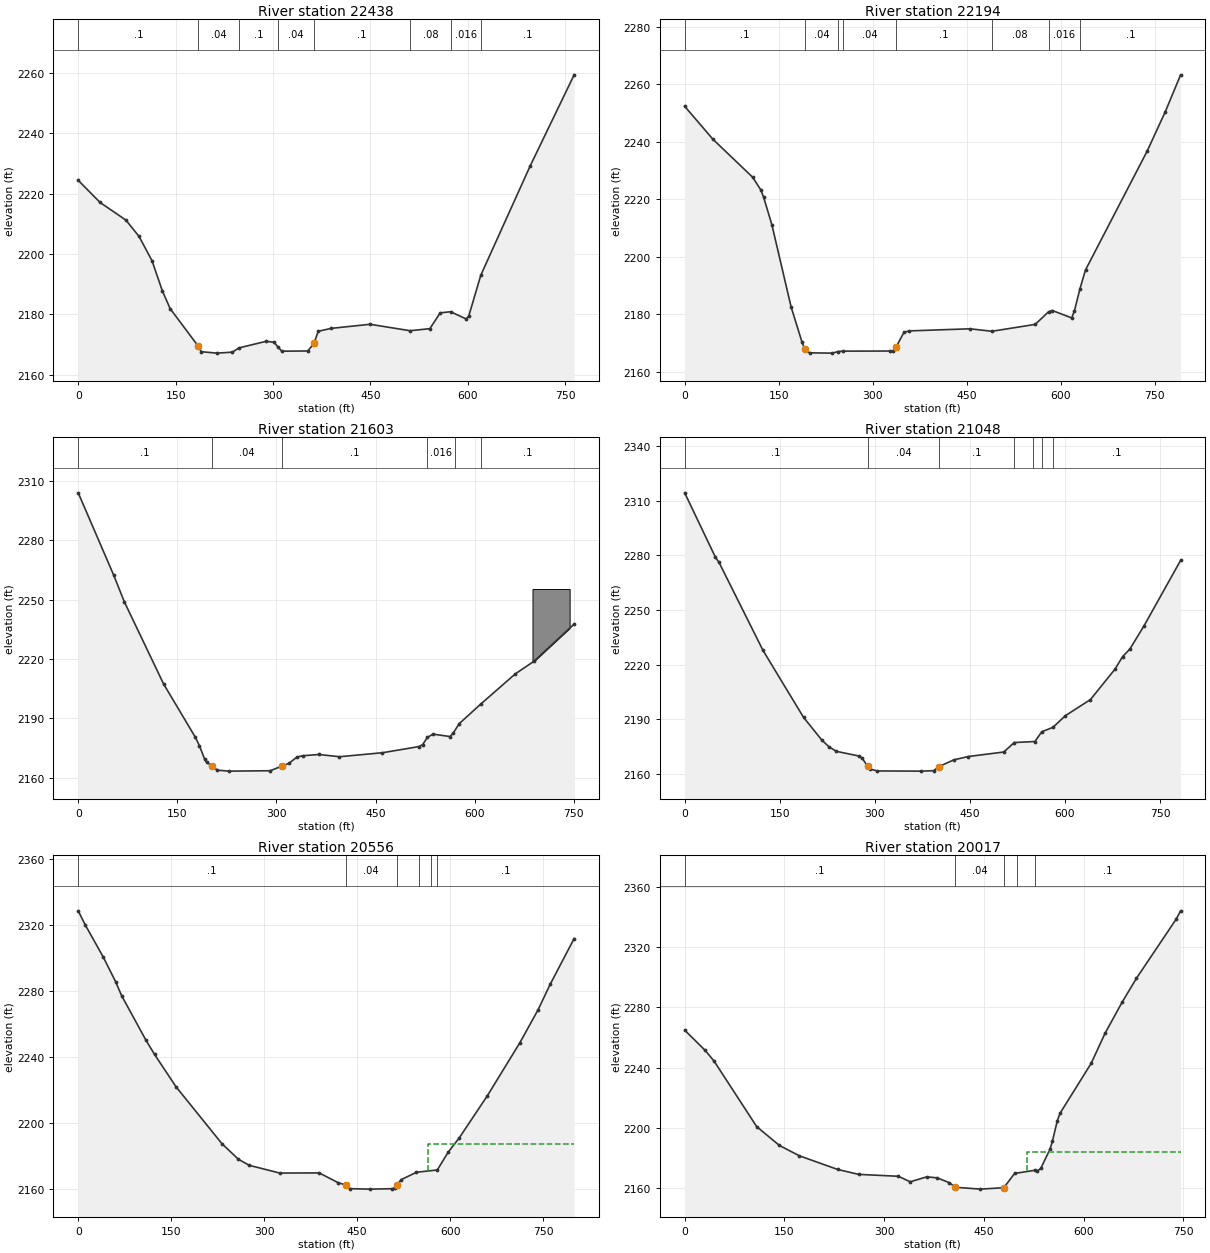
Type RM Length L Ch R = 1 ,22438   ,262.8,243.7,118
XS GIS Cut Line= 2
2240970.61258893441147.5977054582240969.40003783441911.504898441
#Sta/Elev= 30
       0 2224.44    33.6 2217.11    73.6 2211.22    93.6 2205.87   113.6 2197.83
   129.6  2187.8   141.6 2181.92     1852169.436   189.6 2167.64   213.6 2167.17
   237.6 2167.49   247.5  2168.9   289.6 2171.09   301.6 2170.77   307.6 2169.23
   313.6 2167.81   353.6 2167.88   363.4 2170.51   369.6  2174.4   389.6 2175.37
   449.6 2176.73   511.2 2174.59   541.6 2175.28   557.6 2180.51   573.6 2180.89
   597.6 2178.49   601.6 2179.49   620.1 2192.98   696.2 2229.22   763.9 2259.39
#Mann= 8 ,-1,0
       0      .1       0     185     .04       0   247.5      .1       0
   307.6     .04       0   363.4      .1       0   511.2     .08       0
   573.6    .016       0   620.1      .1       0
Bank Sta=185,363.4
XS Rating Curve= 0 ,0
Exp/Cntr(USF)=0,0
Exp/Cntr=0.3,0.1

Type RM Length L Ch R = 1 ,22194   ,613,590.8,512.2
XS GIS Cut Line= 2
2240639.41444053441202.4227064482240964.58619679441923.455731199
#Sta/Elev= 30
       0 2252.38      45 2240.91   108.5 2227.66   121.5 2223.24   125.9 2220.74
   139.1  2211.1   169.8 2182.48   187.3 2170.16   191.7 2167.82   199.2 2166.54
   235.6 2166.44   244.4 2166.99   253.1 2167.13   327.7 2167.17   332.1 2167.25
   337.32168.591   349.7 2173.67   358.4 2174.18     455 2174.91   490.1 2174.05
   559.1 2176.45   580.3 2180.82   586.3 2181.28   617.3 2178.69   621.7 2181.22
   630.5 2188.88   639.3  2195.4   737.5 2236.72   766.5 2250.45     791 2263.33
#Mann= 8 ,-1,0
       0      .1       0   191.7     .04       0   244.4      .1       0
   253.1     .04       0   337.3      .1       0   490.1     .08       0
   580.3    .016       0   630.5      .1       0
Bank Sta=191.7,337.3
XS Rating Curve= 0 ,0
Exp/Cntr(USF)=0,0
Exp/Cntr=0.3,0.1

Type RM Length L Ch R = 1 ,21603   ,554.5,555.7,559.3
XS GIS Cut Line= 2
2240084.50176952441598.2839749392240639.41444053442103.713987386
#Sta/Elev= 30
       0 2303.92    53.7 2262.37    69.6 2249.04   129.2 2207.45   177.4 2180.45
   183.5 2176.22   191.5 2169.34   194.3 2167.88   202.72165.971   210.6  2163.9
   228.3 2163.42   290.6 2163.62     308 2165.91   318.8 2167.32     331 2170.52
   340.4  2171.2   364.3 2171.82   395.4 2170.69   460.5 2172.71   515.2 2175.78
   521.1 2176.74   528.5 2180.46     537  2182.1   562.7 2180.88   567.7 2182.69
   576.6 2187.38   610.2 2197.56   661.6 2212.54   689.9 2218.91   750.6 2237.69
#Mann= 6 ,-1,0
       0      .1       0   202.7     .04       0     308      .1       0
   528.5    .016       0     570     .08       0   610.2      .1       0
#Block Obstruct= 1 ,-1
  687.54  743.76 2255.35
Bank Sta=202.7,308
XS Rating Curve= 0 ,0
Exp/Cntr(USF)=0,0
Exp/Cntr=0.3,0.1

Type RM Length L Ch R = 1 ,21048   ,467,491.7,508.3
XS GIS Cut Line= 2
2239660.36469614441951.7315360912240225.88079398442492.506304654
#Sta/Elev= 30
       0 2314.39    48.4  2279.1    54.2 2276.18   123.6 2227.86   187.6 2191.08
   216.2 2178.72   227.8 2174.91   239.4 2172.46   275.3 2169.85   279.9 2168.76
   288.62164.326   293.1  2162.7   303.6 2161.69   372.5 2161.59   392.7 2161.83
   401.4 2164.11   424.6 2167.78   447.7 2169.62   503.4 2172.08     520 2177.28
   552.6 2177.85   563.5 2183.22   580.9 2185.59   600.7 2192.03   640.3  2200.9
   679.3 2217.74   690.8 2224.41   702.4  2228.6   724.8 2241.39   782.5  2277.3
#Mann= 7 ,-1,0
       0      .1       0   288.6     .04       0   401.4      .1       0
     520    .016       0     550     .06       0   563.5     .03       0
   580.9      .1       0
Bank Sta=288.6,401.4
XS Rating Curve= 0 ,0
Exp/Cntr(USF)=0,0
Exp/Cntr=0.3,0.1

Type RM Length L Ch R = 1 ,20556   ,494,539.3,554.9
Node Name=G
XS GIS Cut Line= 2
2239276.84736451442136.0868099762239739.95598933442788.648963132
#Sta/Elev= 30
       0 2328.73    11.1 2320.36    40.5 2300.64    60.2 2285.85      70  2277.3
   109.2 2250.32   123.2 2241.64   157.8 2222.02   231.9  2187.5   258.5 2178.05
     276 2174.38   325.1 2169.69   388.8 2169.77   419.2 2163.89   431.42162.467
   439.2  2160.2   470.8 2159.94   506.5  2160.2     511 2160.77   513.8 2162.32
   521.3 2165.72   545.8 2170.16   579.4 2171.57     597 2182.39   614.5 2190.85
   660.2  2216.6   712.6 2248.71     742 2268.71   761.6 2284.23   800.2 2311.94
#Mann= 6 ,-1,0
       0      .1       0   431.4     .04       0   513.8     .03       0
     550    .016       0     570     .08       0   579.4      .1       0
#XS Ineff= 2 , 0
                          564.51         2187.24
Permanent Ineff=
       F       F
Bank Sta=431.4,513.8
XS Rating Curve= 0 ,0
Exp/Cntr(USF)=0,0
Exp/Cntr=0.3,0.1

Type RM Length L Ch R = 1 ,20017   ,447.5,454.5,457
XS GIS Cut Line= 2
2238918.12481772442347.5928045812239176.14153736443047.418975662
#Sta/Elev= 30
       0 2264.79    30.9 2251.33    44.3 2244.22   108.3 2200.84   142.4 2188.39
   172.2 2181.55   230.2 2172.43   261.7 2169.18   321.4 2167.93   339.2 2164.27
   363.9 2167.53   379.7  2166.9   398.2 2163.62   407.22160.635   444.9 2159.41
     480 2160.36   496.2 2169.81   526.3 2171.88   530.3 2171.43   535.5 2173.13
   549.4 2185.78     553 2191.06   560.4 2204.65   564.4 2209.59   611.3 2242.74
   632.6 2263.02   658.2 2283.53   679.5 2299.18   739.2 2338.35   745.9 2343.88
#Mann= 5 ,-1,0
       0      .1       0   407.2     .04       0     480      .1       0
     500    .016       0   526.3      .1       0
#XS Ineff= 2 , 0
                          515.15         2184.17
Permanent Ineff=
       F       F
Bank Sta=407.2,480
XS Rating Curve= 0 ,0
Exp/Cntr(USF)=0,0
Exp/Cntr=0.3,0.1