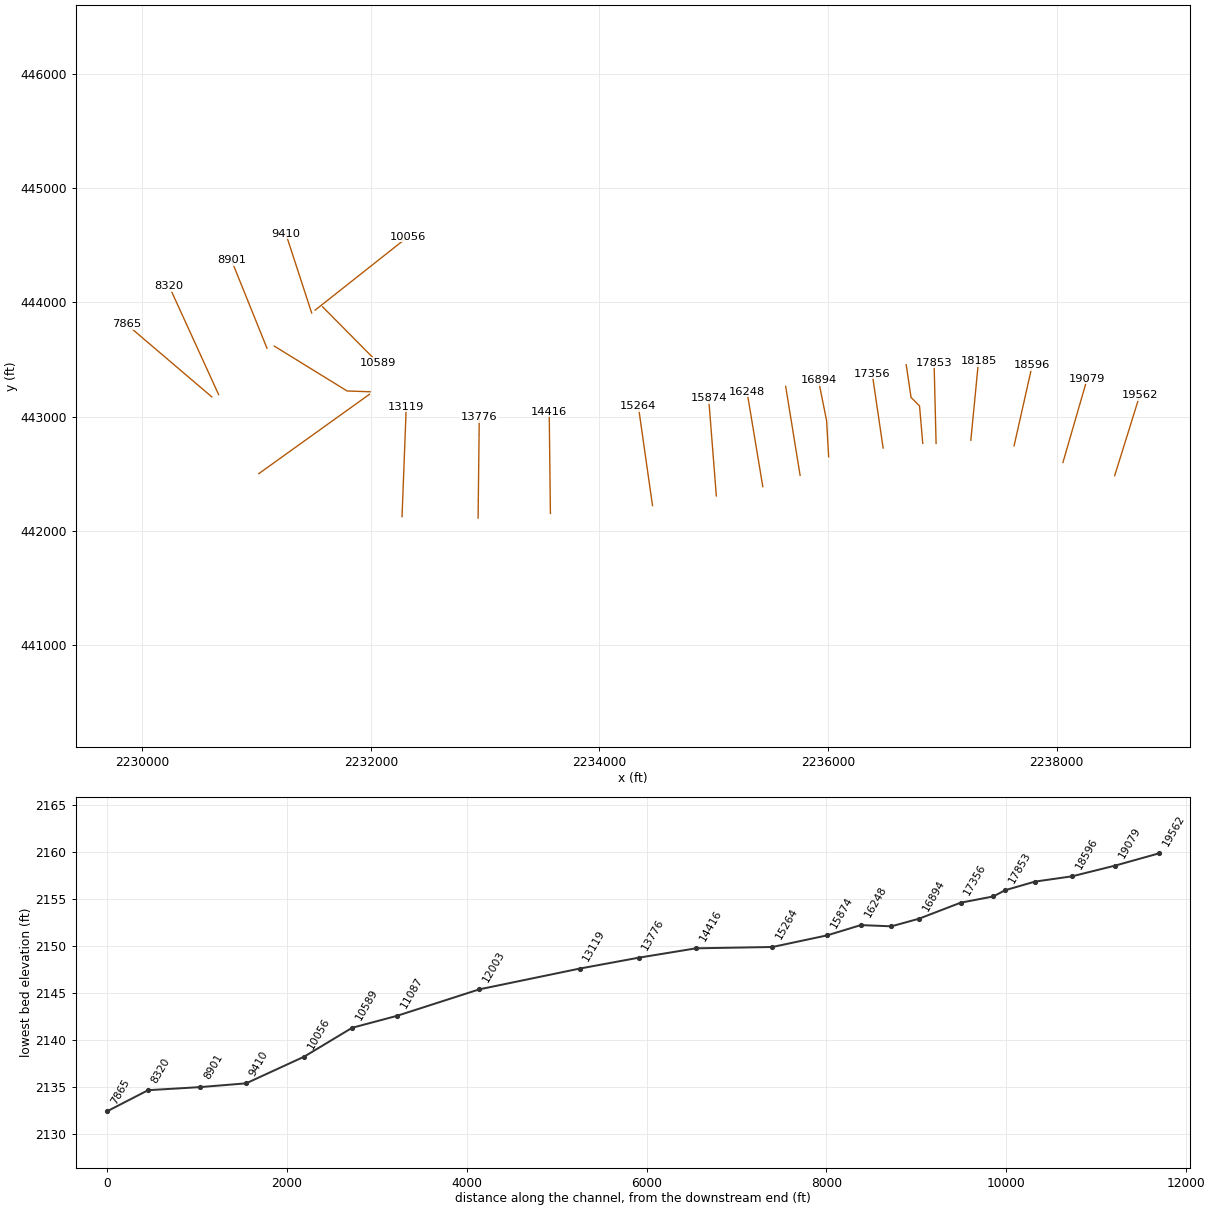
HEC-RAS study KNAPPCK.prj: KNAPPCK

--- KNAPPCK.g01 (geometry) --- (continued)

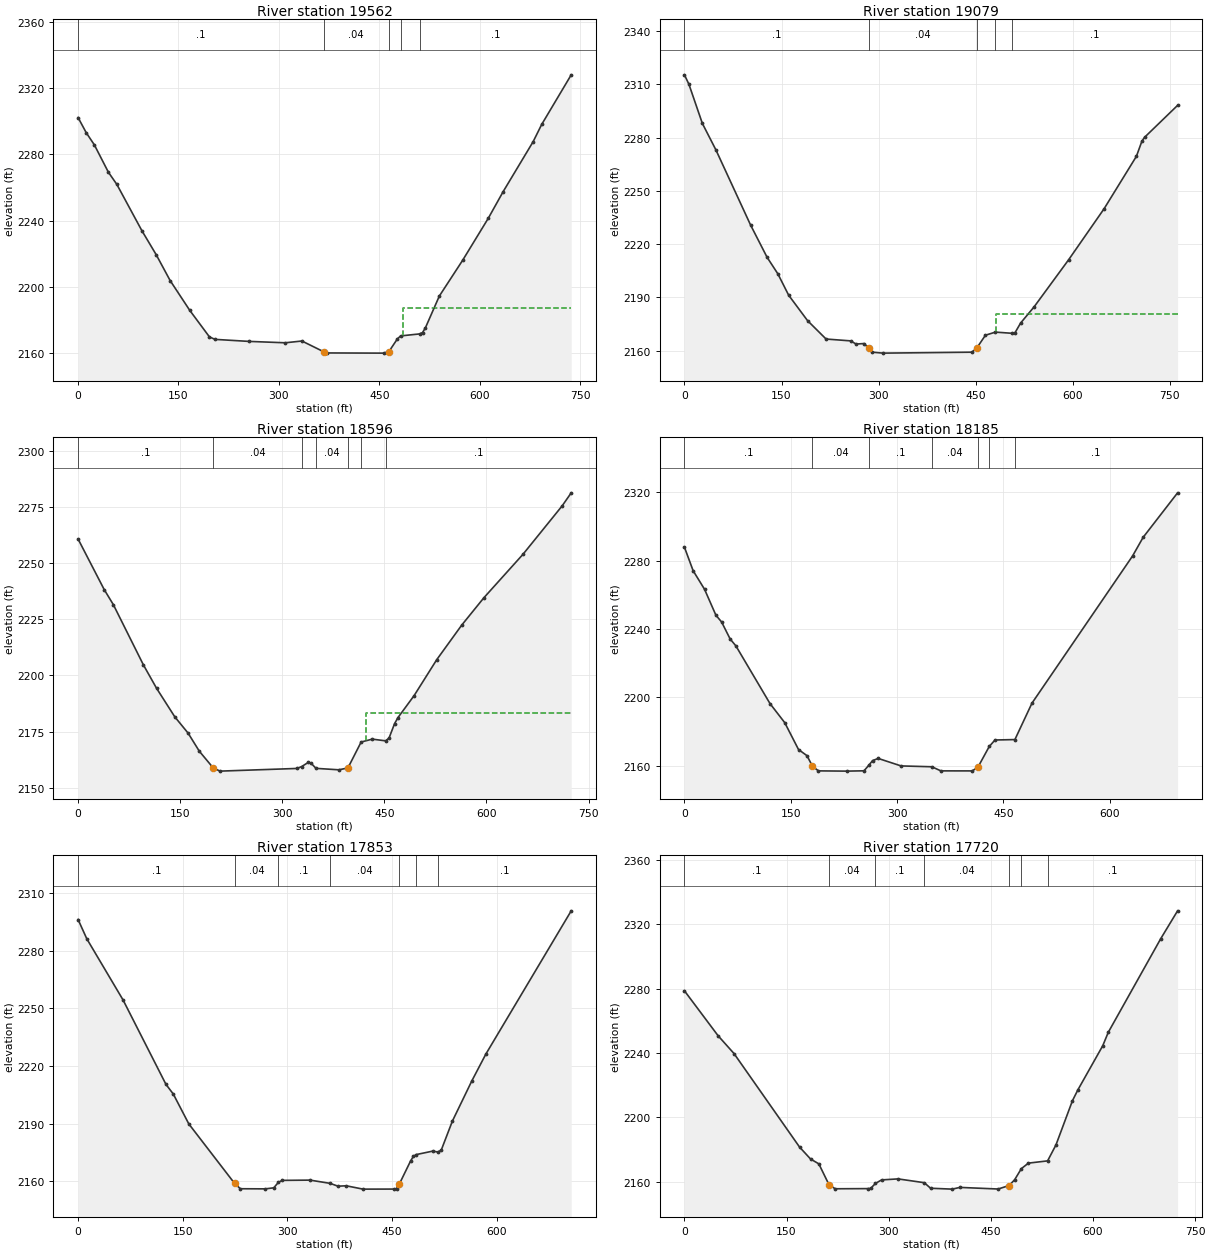
Type RM Length L Ch R = 1 ,19562   ,473.1,482.8,477.6
XS GIS Cut Line= 2
2238508.12564678442481.902877819 2238727.2631347443185.263524512
#Sta/Elev= 30
       0 2302.22    12.2 2293.07    24.4 2285.66    45.3 2269.18    57.9 2261.85
    95.3 2233.88   116.6 2219.43   137.5 2203.76   166.8 2185.75   196.2 2169.71
   204.5 2168.19   254.8 2166.98   309.5 2166.13   334.4  2167.2   366.8 2160.74
   372.1 2159.99   456.3 2159.88   464.3 2160.78   476.9 2168.42   481.8 2170.28
   510.4  2171.5   514.6 2172.33   518.8 2175.11   539.7 2194.39   574.5 2215.98
   612.8 2241.37   635.1 2257.52   679.9 2287.72   692.6 2298.07   736.7 2328.04
#Mann= 5 ,-1,0
       0      .1       0   366.8     .04       0   464.3      .1       0
   481.8    .016       0   510.4      .1       0
#XS Ineff= 2 , 0
                          485.86         2186.98
Permanent Ineff=
       F       F
Bank Sta=366.8,464.3
XS Rating Curve= 0 ,0
Exp/Cntr(USF)=0,0
Exp/Cntr=0.3,0.1

Type RM Length L Ch R = 1 ,19079   ,463.4,483,477.4
XS GIS Cut Line= 2
2238055.71276851442598.540572999 2238267.7813052443330.177024584
#Sta/Elev= 30
       0 2315.39     6.9  2310.1    27.7    2288    48.6 2273.11   102.2 2230.74
   127.7 2212.57   144.3 2203.28     161 2191.23   190.2 2176.89   218.8 2166.53
   256.8 2165.49   265.1 2163.71   277.6 2163.99   284.52161.325   290.1 2159.12
   306.8 2158.59   444.2 2159.12   451.8 2161.59     465 2168.68   480.4 2170.43
   506.7 2169.75   510.8 2170.18   519.3 2175.53     540 2184.59   593.4 2211.15
   648.3 2239.95   698.2 2269.48   706.6 2277.93   710.7 2280.15   761.8 2298.18
#Mann= 5 ,-1,0
       0      .1       0   284.5     .04       0   451.8      .1       0
   480.4    .016       0   506.7      .1       0
#XS Ineff= 2 , 0
                           480.9          2180.7
Permanent Ineff=
       F       F
Bank Sta=284.5,451.8
XS Rating Curve= 0 ,0
Exp/Cntr(USF)=0,0
Exp/Cntr=0.3,0.1

Type RM Length L Ch R = 1 ,18596   ,403.7,411.6,432.9
XS GIS Cut Line= 2
2237628.04121951442743.4540730722237787.09262203443450.349195376
#Sta/Elev= 30
       0 2260.68    38.4 2238.18    51.8  2231.5    96.1 2204.63   115.4 2194.25
   142.1 2181.59   161.7 2174.33   178.1 2166.32   198.3 2158.97   208.4 2157.44
   321.6 2158.63   328.6 2159.48     338 2161.28   342.1 2161.04   349.6 2158.67
   383.1 2158.03   396.5 2158.85   415.9 2170.38   432.3 2171.67   451.8 2170.91
   456.9 2172.14   465.1  2178.6   470.1 2181.28   493.8 2191.05     527 2207.01
   563.8 2222.42   596.3 2234.56   653.7 2253.87   711.3 2275.43   724.6 2281.22
#Mann= 7 ,-1,0
       0      .1       0   198.3     .04       0   328.6      .1       0
   349.6     .04       0   396.5      .1       0   415.9    .016       0
   451.8      .1       0
#XS Ineff= 2 , 0
                          422.76         2183.42
Permanent Ineff=
       F       F
Bank Sta=198.3,396.5
XS Rating Curve= 0 ,0
Exp/Cntr(USF)=0,0
Exp/Cntr=0.3,0.1

Type RM Length L Ch R = 1 ,18185   ,327,332.1,357.2
XS GIS Cut Line= 2
2237249.85232908442792.936731633 2237317.0073657443485.693951491
#Sta/Elev= 30
       0 2287.96    12.3 2274.16    28.4  2263.3    44.4 2248.16    52.5 2244.15
    64.5 2234.22    72.6  2230.2   120.8 2196.39   141.6 2185.23     161 2169.53
     173 2165.91   180.62159.805   189.1 2157.03   229.1 2156.88   253.4 2157.07
   260.2 2160.29   265.5 2163.04   273.5 2164.31   305.7 2159.93   349.2 2159.43
   361.9 2157.03   406.1 2157.01   414.2 2159.16   430.2 2171.31   438.3  2175.1
   466.4 2175.35   490.5 2196.67   632.5 2282.83   647.4 2293.73     696 2319.77
#Mann= 7 ,-1,0
       0      .1       0   180.6     .04       0   260.2      .1       0
   349.2     .04       0   414.2      .1       0   430.2    .016       0
   466.4      .1       0
Bank Sta=180.6,414.2
XS Rating Curve= 0 ,0
Exp/Cntr(USF)=0,0
Exp/Cntr=0.3,0.1

Type RM Length L Ch R = 1 ,17853   ,129.2,132.2,216
Node Name=F
XS GIS Cut Line= 2
2236945.88742649442764.6609267412236928.21504843443471.556049045
#Sta/Elev= 30
       0 2296.28    12.5 2286.25    64.5 2254.41     126  2210.5   136.6 2205.41
   158.8 2189.89   224.5  2158.9   232.7 2156.16   268.6  2156.1   280.6 2156.64
   287.1 2159.44   292.6 2160.51   332.6 2160.65   361.3 2158.97   372.6  2157.5
   384.6 2157.69   408.6 2155.96   452.7 2155.99   456.7 2156.24   460.7 2158.65
   476.7 2170.56   480.7 2172.95   484.7 2173.93   508.7 2175.76   515.9 2175.27
   520.7 2176.23   536.7 2191.36   564.7 2212.37   584.7 2226.25   707.1  2300.8
#Mann= 7 ,-1,0
       0      .1       0   224.5     .04       0   287.1      .1       0
   361.3     .04       0   460.7      .1       0   484.7    .016       0
   515.9      .1       0
Bank Sta=224.5,460.7
XS Rating Curve= 0 ,0
Exp/Cntr(USF)=0,0
Exp/Cntr=0.3,0.1

Type RM Length L Ch R = 1 ,17720   ,361.3,364,306.7
XS GIS Cut Line= 4
2236829.24973131442764.6609267412236800.97392642443093.367158612
2236726.74993858443167.5911464542236684.33623124443453.883670987
#Sta/Elev= 30
       0 2278.63    49.5 2250.64    72.8 2239.62   169.1 2181.44   185.2 2174.05
   197.4 2171.01   212.22158.154   221.3 2155.52   269.5 2155.62   273.5 2155.72
   280.5 2158.84   289.6 2161.03   313.7 2161.66   352.3  2159.3   361.5 2155.85
   393.3  2155.3   404.6 2156.37   460.8 2155.37   476.9 2157.55     485 2161.15
   494.9 2168.05   505.2 2171.47   533.4 2172.87   545.7 2182.81   569.9  2210.3
     578 2217.13   614.4 2244.47   622.5  2252.8   699.5 2310.99   724.3 2328.35
#Mann= 7 ,-1,0
       0      .1       0   212.2     .04       0   280.5      .1       0
   352.3     .04       0   476.9      .1       0   494.9    .016       0
   533.4      .1       0
Bank Sta=212.2,476.9
XS Rating Curve= 0 ,0
Exp/Cntr(USF)=0,0
Exp/Cntr=0.3,0.1

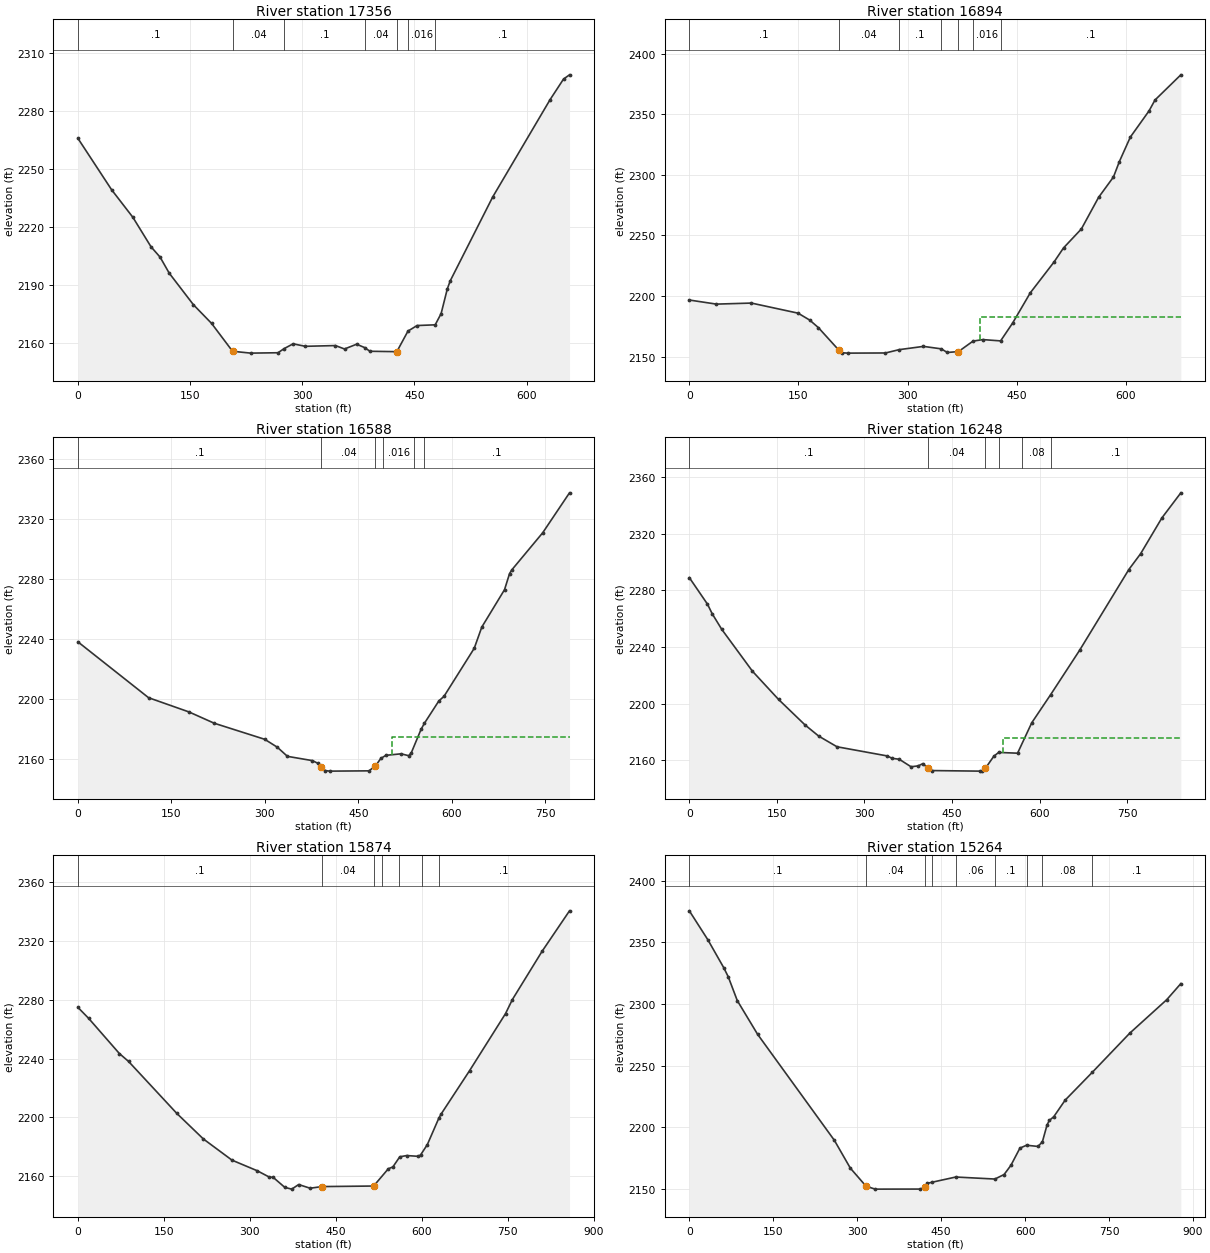
Type RM Length L Ch R = 1 ,17356   ,466.1,462.2,461.3
XS GIS Cut Line= 2
2236482.44418872442724.5123381132236387.01334721443374.855850633
#Sta/Elev= 30
       0 2265.88    44.9 2239.33    73.4 2225.02    97.7 2209.72   109.8 2204.38
     122 2196.08   154.3 2179.74   178.6 2170.06   206.7 2155.59   231.1 2154.63
   267.5 2154.83   275.6 2156.96   287.7 2159.46   303.9 2158.16   344.3 2158.55
   356.4 2156.78   372.6 2159.25   383.3 2157.51   390.4 2155.59  426.38 2155.39
   441.3 2166.06   453.5 2168.93   477.7  2169.3   485.6 2175.11   493.9 2187.95
   497.9 2192.18   554.5 2235.49   631.4 2286.05   649.3 2296.66   657.3 2298.86
#Mann= 7 ,-1,0
       0      .1       0   206.7     .04       0   275.6      .1       0
   383.3     .04       0  426.38      .1       0   441.3    .016       0
   477.7      .1       0
Bank Sta=206.7,426.38
XS Rating Curve= 0 ,0
Exp/Cntr(USF)=0,0
Exp/Cntr=0.3,0.1

Type RM Length L Ch R = 1 ,16894   ,293.9,306.6,303
XS GIS Cut Line= 3
2236005.71691383 442648.023231562235988.04453577442962.591560986
2235917.35502354443316.039122138
#Sta/Elev= 30
       0 2196.74    37.2 2193.37    85.3 2194.23   149.4 2185.91   165.4 2180.21
   177.4 2173.96   205.72155.255   209.5 2153.26   217.5 2152.93   269.6 2153.06
   288.2 2155.78   321.8 2158.49   346.3 2156.45   354.5 2153.47   369.9  2154.2
   389.9 2162.85   403.4 2164.09   427.8 2163.02   444.2 2177.63   468.6 2202.68
   501.3 2228.18   514.3 2239.75   538.8 2255.38   562.5 2281.48   582.9 2298.25
     591 2310.95   606.1 2331.18   631.8 2352.79     640 2361.77   675.5 2382.54
#Mann= 7 ,-1,0
       0      .1       0   205.7     .04       0   288.2      .1       0
   346.3     .04       0   369.9      .1       0   389.9    .016       0
   427.8      .1       0
#XS Ineff= 2 , 0
                           399.1         2182.66
Permanent Ineff=
       F       F
Bank Sta=205.7,369.9
XS Rating Curve= 0 ,0
Exp/Cntr(USF)=0,0
Exp/Cntr=0.3,0.1

Type RM Length L Ch R = 1 ,16588   ,340.5,340.2,341
XS GIS Cut Line= 2
2235756.09106547442485.3028626212235629.78871324   443264.167368
#Sta/Elev= 30
       0 2238.23   113.3 2201.05   178.2 2191.56   218.7 2184.04   299.8 2173.32
     320 2168.04   336.2 2161.97   376.4 2159.11   384.8 2157.39   390.42154.778
     397 2152.45   404.3 2152.12   467.1 2152.31   477.5 2155.58   486.1 2160.57
   494.2 2162.64   518.6 2163.66   530.7 2162.43   534.8 2164.11   550.7 2179.96
   556.2 2184.09   579.3 2198.92   587.5 2201.94   636.1 2234.01   648.2 2248.12
   684.7 2273.05   692.8 2283.81   696.4 2286.25     746 2310.99     789 2337.59
#Mann= 6 ,-1,0
       0      .1       0   390.4     .04       0   477.5     .08       0
     490    .016       0     540     .08       0   556.2      .1       0
#XS Ineff= 2 , 0
                          503.89         2174.87
Permanent Ineff=
       F       F
Bank Sta=390.4,477.5
XS Rating Curve= 0 ,0
Exp/Cntr(USF)=0,0
Exp/Cntr=0.3,0.1

Type RM Length L Ch R = 1 ,16248   ,384.5,373.4,368.5
XS GIS Cut Line= 2
2235429.59738915442386.472036308 2235291.7528403443217.073805015
#Sta/Elev= 30
       0 2288.91    31.1 2270.17    39.2 2263.38    55.5 2252.41   108.2 2222.78
   152.8  2202.9   198.3 2184.84   221.7 2176.97     253 2169.45   339.3 2162.96
   347.4 2161.29   359.6 2160.64   379.8 2155.34     392 2155.94   400.1 2157.56
   408.42154.394   416.3 2152.64   497.4 2152.25   501.5 2152.32   507.2 2154.27
   521.7 2162.81   529.9 2165.45   562.3 2164.92   586.6  2186.4   619.1 2206.34
   668.4 2237.48   752.9 2294.61   773.1 2305.79   809.6 2331.12     842 2348.79
#Mann= 6 ,-1,0
       0      .1       0   408.4     .04       0   507.2     .08       0
     530    .016       0     570     .08       0   619.1      .1       0
#XS Ineff= 2 , 0
                           536.9         2175.88
Permanent Ineff=
       F       F
Bank Sta=408.4,507.2
XS Rating Curve= 0 ,0
Exp/Cntr(USF)=0,0
Exp/Cntr=0.3,0.1

Type RM Length L Ch R = 1 ,15874   ,589.4,609.8,598.4
XS GIS Cut Line= 2
2235023.13269382442305.179097243 2234955.9776572443160.522195231
#Sta/Elev= 30
       0  2274.8    18.6 2267.39    72.2 2243.46    88.3 2238.06   172.5  2202.7
   218.8 2185.32   268.8 2170.89     313 2163.65     333 2159.55     341 2159.08
   361.1 2152.33   373.1 2151.16   385.2 2154.28   405.2 2151.78     4262152.893
   516.1 2153.27   541.7 2165.01   549.7 2166.28   561.7 2173.16   573.8 2174.01
   593.8 2173.49     598 2174.39   609.9 2181.53   629.9 2199.46   633.9 2202.28
   683.6 2231.81   746.3 2270.61   758.3  2280.2     810 2312.95     858 2340.57
#Mann= 7 ,-1,0
       0      .1       0     426     .04       0   516.1      .1       0
     530     .04       0     560    .016       0     600     .08       0
     630      .1       0
Bank Sta=426,516.1
XS Rating Curve= 0 ,0
Exp/Cntr(USF)=0,0
Exp/Cntr=0.3,0.1

Type RM Length L Ch R = 1 ,15264   ,858.1,848.7,826.9
XS GIS Cut Line= 2
 2234464.6855472442220.351682566 2234340.9789008443089.832683001
#Sta/Elev= 30
       0 2375.62    33.2 2352.09    61.6 2329.41    69.5 2322.19    85.7  2302.8
     122 2275.47   259.2 2189.47   287.7 2166.93   315.82152.265   332.1 2149.92
   412.9 2149.97     421 2151.68   425.1 2154.58   432.7 2155.41   476.1 2159.74
   545.9  2158.1   562.4 2161.76   574.6 2169.23   590.7  2183.2   602.5 2185.51
     623 2184.54   630.8 2188.28   639.2 2202.02   643.2 2205.58   651.3 2208.74
   671.5 2222.09     720 2244.67     787 2276.42     853 2303.55   878.2  2316.6
#Mann= 9 ,-1,0
       0      .1       0   315.8     .04       0     421     .07       0
   432.7      .1       0   476.1     .06       0   545.9      .1       0
   602.5    .016       0   630.8     .08       0     720      .1       0
Bank Sta=315.8,421
XS Rating Curve= 0 ,0
Exp/Cntr(USF)=0,0
Exp/Cntr=0.3,0.1

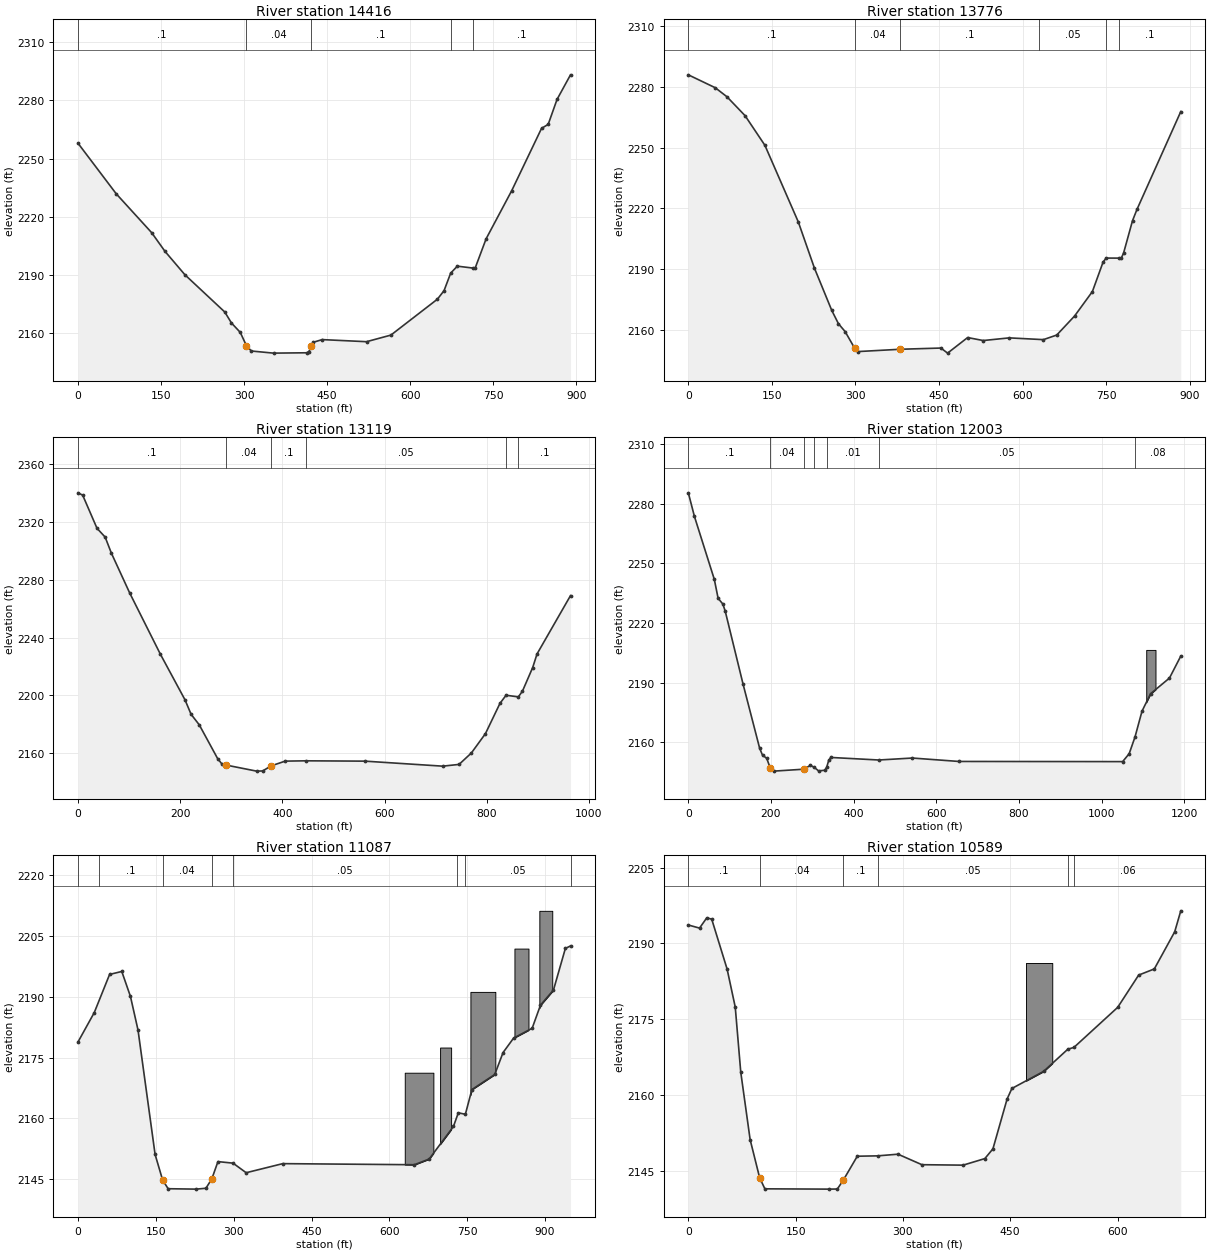
Type RM Length L Ch R = 1 ,14416   ,628.1,639.4,619.9
Node Name=E
XS GIS Cut Line= 2
2233571.33762789442152.1875272682233560.81243187443041.566590843
#Sta/Elev= 30
       0  2257.9      69 2231.86     133 2211.83     157 2202.23     193 2190.16
     265 2170.97   277.1 2165.31     293 2160.46     3042153.674     313 2150.87
     353 2149.78     413 2149.96     417 2150.61     421 2153.23     425 2155.39
     441 2156.75     521 2155.67     565 2159.07     649 2177.57     661 2181.96
     673 2191.01     685 2194.59     713 2193.61     717 2193.45     737  2208.7
   783.2 2233.47   837.1 2265.59   849.1 2267.65   865.1 2280.52   889.4 2293.17
#Mann= 5 ,-1,0
       0      .1       0     304     .04       0     421      .1       0
     673    .016       0     713      .1       0
Bank Sta=304,421
XS Rating Curve= 0 ,0
Exp/Cntr(USF)=0,0
Exp/Cntr=0.3,0.1

Type RM Length L Ch R = 1 ,13776   ,658.3,657.2,651.1
XS GIS Cut Line= 2
2232938.56008482442111.7366347752232949.08528084 442995.85310034
#Sta/Elev= 30
       0  2285.8    48.4 2279.44    69.4 2274.99   101.9 2265.69   137.5  2251.1
   197.5 2213.35   226.5 2190.58   257.5 2169.84   269.5 2163.28   281.5  2159.4
   298.62151.229   305.5 2149.56   380.92150.689   453.5 2151.28   465.5 2148.78
   501.5 2156.45   529.5 2154.98   576.2 2156.29   637.5 2155.42   661.5 2157.69
   693.5 2167.05   725.5  2179.1   744.7 2193.62   750.2 2195.58   773.5 2195.56
   777.5 2195.65   781.5 2198.07   797.5 2213.97   805.5 2219.52   884.2 2267.71
#Mann= 6 ,-1,0
       0      .1       0   298.6     .04       0   380.9      .1       0
     630     .05       0   750.2    .016       0   773.5      .1       0
Bank Sta=298.6,380.9
XS Rating Curve= 0 ,0
Exp/Cntr(USF)=0,0
Exp/Cntr=0.3,0.1

Type RM Length L Ch R = 1 ,13119   ,1164.2,1115.9,637.5
XS GIS Cut Line= 2
2232273.26818391442124.0681840072232310.10636997443087.123619712
#Sta/Elev= 30
       0 2340.24     9.1 2338.61    37.1 2315.69    53.1 2309.58    65.2 2298.52
   101.2 2270.85   161.2 2228.52   209.3 2196.99   221.3 2186.93   237.3 2179.63
   273.3 2156.23   281.3 2152.67   289.2 2151.85   349.4 2147.62   361.4 2147.74
   377.9 2151.26   405.4 2154.54   445.4 2154.76   561.5 2154.53   713.6 2151.06
   745.7 2152.27   769.7 2160.14   797.3 2173.56   825.7 2194.49   837.7 2200.15
   861.7    2199   869.7 2202.93   889.8 2219.34   898.3 2228.73   963.8  2269.1
#Mann= 6 ,-1,0
       0      .1       0   289.2     .04       0   377.9      .1       0
   445.4     .05       0   837.7    .016       0   861.7      .1       0
Bank Sta=289.2,377.9
XS Rating Curve= 0 ,0
Exp/Cntr(USF)=0,0
Exp/Cntr=0.3,0.1

Type RM Length L Ch R = 1 ,12003   ,968.8,915.9,355.6
Node Name=D
XS GIS Cut Line= 2
2231020.14401116442500.5430409382231988.46204487443195.205978168
#Sta/Elev= 30
       0 2285.53    14.8 2273.63    62.9 2241.96    72.1 2232.41    83.6 2229.53
    89.3 2225.95   132.3 2189.36   172.6 2156.93   179.5 2153.46   189.7 2151.86
   198.3 2146.92   206.8 2145.41   278.82146.373   295.4 2148.28   304.3 2147.39
   315.1 2145.55   330.1 2145.84   334.8 2147.34   339.7 2150.81   344.6  2152.3
   460.9 2151.01   542.2    2152   654.8 2150.28    1051  2150.2  1066.8 2154.18
  1081.1 2162.74  1097.8 2175.57  1118.4 2184.34  1164.3 2192.27  1191.7 2203.34
#Mann= 7 ,-1,0
       0      .1       0   198.3     .04       0   278.8      .1       0
   304.3    .045       0   334.8     .01       0   460.9     .05       0
  1081.1     .08       0
#Block Obstruct= 1 ,-1
 1108.06 1130.49 2206.44
Bank Sta=198.3,278.8
XS Rating Curve= 0 ,0
Exp/Cntr(USF)=0,0
Exp/Cntr=0.3,0.1

Type RM Length L Ch R = 1 ,11087   ,505.7,498.1,435
XS GIS Cut Line= 3
2231156.41637482443616.4695491172231792.62198489443224.142756238
2231994.08709475443217.073805015
#Sta/Elev= 30
       0 2178.86    31.3 2186.09    60.8 2195.48    84.3 2196.21     101 2190.06
   115.6 2181.77   148.5 2151.13   162.92144.863   173.6 2142.69   227.3 2142.59
   246.4  2142.8   257.8 2145.11   269.6 2149.37   298.7 2148.99     324 2146.63
   394.5 2148.87   648.2  2148.6   676.6    2150   723.4 2158.02   732.8 2161.39
   746.4 2161.03     759 2167.12     803 2170.83     819 2176.23   839.3 2179.79
   875.1 2182.22   891.1  2187.9   916.2 2191.65   939.1 2201.89     949  2202.5
#Mann= 8 ,-1,0
       0     .12       0      40      .1       0   162.9     .04       0
   257.8      .1       0   298.7     .05       0     730    .016       0
   746.4     .05       0     949     .03       0
#Block Obstruct= 5 ,-1
  629.58  684.75 2171.27  697.68  718.94 2177.47  756.12  804.12 2191.18
  840.95  868.02 2201.85  888.93  913.83 2211.15
Bank Sta=162.9,257.8
XS Rating Curve= 0 ,0
Exp/Cntr(USF)=0,0
Exp/Cntr=0.3,0.1

Type RM Length L Ch R = 1 ,10589   ,369.2,533.1,728.2
XS GIS Cut Line= 2
2231578.05371738443961.2805853452232062.21273423443471.858970478
#Sta/Elev= 30
       0 2193.64    15.7 2193.03    25.8 2195.06    32.7  2194.8    54.2 2184.92
    65.6 2177.38    73.3 2164.49    86.4 2151.13    99.7 2143.57     107 2141.38
   196.4 2141.32   208.3 2141.34   216.5 2143.07   236.2 2147.84   264.6 2147.91
   293.1 2148.24   326.5 2146.16   384.1 2146.07   414.5 2147.37   425.8  2149.3
   445.6 2159.17   452.3 2161.26   496.6 2164.64   530.5 2169.04     539 2169.39
   600.2 2177.33   629.5 2183.72   651.4 2184.94   679.9  2192.3   688.4 2196.45
#Mann= 6 ,-1,0
       0      .1       0    99.7     .04       0   216.5      .1       0
   264.6     .05       0   530.5    .016       0     539     .06       0
#Block Obstruct= 1 ,-1
     472  508.73 2186.12
Bank Sta=99.7,216.5
XS Rating Curve= 0 ,0
Exp/Cntr(USF)=0,0
Exp/Cntr=0.3,0.1

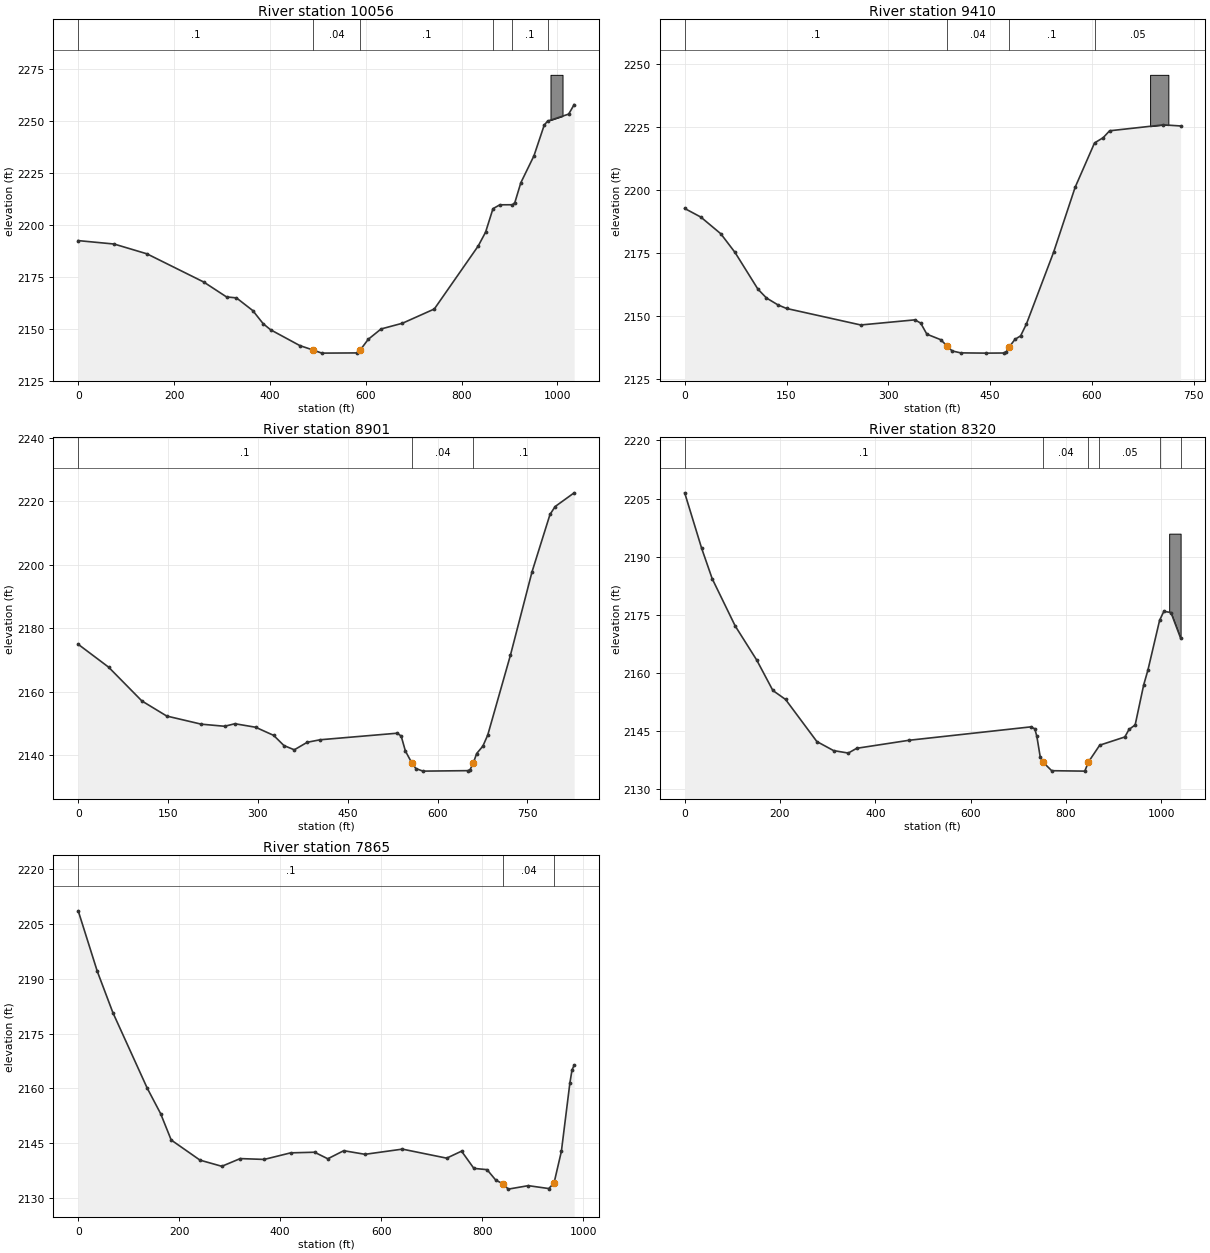
Type RM Length L Ch R = 1 ,10056   ,554.6,645.7,737.5
XS GIS Cut Line= 2
 2231513.4130249443932.1261611042232325.11185584 444574.16311824
#Sta/Elev= 30
       0  2192.5    74.9 2190.85   143.5 2186.12   261.8 2172.55   309.5 2165.35
   330.2 2164.88   364.4 2158.74     386 2152.43   401.4 2149.52   462.5 2141.88
   489.82139.768   508.4 2138.25   580.8 2138.35   588.4 2139.72   605.3 2144.93
     632  2149.9   676.7 2152.67   743.1 2159.53   834.8 2189.94   850.1 2196.59
   865.5 2207.89   879.8 2209.76   906.2 2209.79   911.1 2210.83   923.7 2220.44
     951 2233.37   972.5 2248.22   979.5 2250.11  1023.5  2253.5  1034.9 2258.09
#Mann= 6 ,-1,0
       0      .1       0   489.8     .04       0   588.4      .1       0
   865.5    .016       0   906.2      .1       0   979.5     .06       0
#Block Obstruct= 1 ,-1
  985.52 1010.63 2272.43
Bank Sta=489.8,588.4
XS Rating Curve= 0 ,0
Exp/Cntr(USF)=0,0
Exp/Cntr=0.3,0.1

Type RM Length L Ch R = 1 ,9410    ,527.3,509.5,513.6
Node Name=C
XS GIS Cut Line= 2
2231482.70110669443906.5805297082231256.40939229444601.243466938
#Sta/Elev= 30
       0  2192.7    23.8 2189.29    53.2 2182.68    74.2 2175.27   107.9 2160.75
   120.5 2157.24   137.3 2154.53     150  2153.1   259.4 2146.56   339.3 2148.59
   347.7 2147.29   356.8 2142.91   377.1 2140.74   386.42138.283     394 2136.27
   406.6 2135.51   444.5 2135.41   469.7 2135.46   473.9 2135.88   478.1 2137.84
   486.5 2140.85   494.9 2142.26   503.4 2146.92   543.5 2175.38   575.2 2201.08
   603.8 2218.65   616.5 2220.72     626 2223.46   705.2 2225.81   730.6 2225.37
#Mann= 4 ,-1,0
       0      .1       0   386.4     .04       0   478.1      .1       0
   603.8     .05       0
#Block Obstruct= 1 ,-1
  685.65  712.55 2245.62
Bank Sta=386.4,478.1
XS Rating Curve= 0 ,0
Exp/Cntr(USF)=0,0
Exp/Cntr=0.3,0.1

Type RM Length L Ch R = 1 ,8901    ,601.1,580.8,584.8
XS GIS Cut Line= 2
2231091.48674877443598.578993553  2230781.674689444366.563817784
#Sta/Elev= 30
       0 2174.93    50.6 2167.76   106.3  2157.1   147.8 2152.35   205.5 2149.79
   244.5 2149.13   261.6 2149.93   296.1 2148.83   326.3 2146.27   343.5 2143.06
   360.8 2141.72   382.4 2144.09   403.9 2144.88   532.8 2146.95   539.3 2146.03
   546.3 2141.35   557.52137.424   563.9 2135.82   575.5 2135.01   650.4 2135.16
   654.1  2135.4   659.82137.598   665.3 2140.54   675.7 2142.89   683.8 2146.36
   721.7  2171.5   757.8 2197.77   787.8 2215.82   796.4  2218.3   828.1 2222.61
#Mann= 3 ,0,0
       0      .1       0   557.5     .04       0   659.8      .1       0
Bank Sta=557.5,659.8
XS Rating Curve= 0 ,0
Exp/Cntr(USF)=0,0
Exp/Cntr=0.3,0.1

Type RM Length L Ch R = 1 ,8320    ,204,455,469.9
XS GIS Cut Line= 2
2230668.22238542443192.7688307482230236.23092179444139.659210625
#Sta/Elev= 30
       0 2206.47    35.6 2192.17    57.7 2184.33     106 2172.13   151.3 2163.31
   185.1 2155.48   211.7 2153.17   277.4 2142.31   312.6 2139.97   343.4 2139.34
     361 2140.57   470.9 2142.64   725.9 2146.09   734.7 2145.61   739.1 2143.64
   746.1 2138.39   752.1 2136.99   770.2 2134.79   839.7 2134.68  847.34 2137.04
     871 2141.37   923.7 2143.49   932.5 2145.43   945.4  2146.6   963.3 2156.93
   972.1 2160.71   996.7 2173.59  1005.7 2175.91  1020.5 2175.59  1040.8 2168.98
#Mann= 6 ,-1,0
       0      .1       0   752.1     .04       0  847.34      .1       0
     870     .05       0   996.7      .1       0  1040.8     .03       0
#Block Obstruct= 1 ,-1
 1016.78 1040.78 2195.94
Bank Sta=752.1,847.34
XS Rating Curve= 0 ,0
Exp/Cntr(USF)=0,0
Exp/Cntr=0.3,0.1

Type RM Length L Ch R = 1 ,7865    ,51.7,411.5,438.6
XS GIS Cut Line= 2
2230608.36525516443172.645641239 2229860.9646186443809.843054355
#Sta/Elev= 30
       0 2208.62    37.8 2192.05    68.6 2180.77   136.7 2160.07   163.2 2153.11
   184.2 2145.88   241.3 2140.37   284.4 2138.69   320.9  2140.8   368.2 2140.57
   420.8 2142.37   468.1 2142.54   494.3 2140.75   525.9 2142.96     568 2141.97
     642 2143.39   729.7 2140.92   759.2 2142.83   783.6 2138.12   809.7 2137.77
     827  2134.9   841.82133.854   851.7 2132.44   891.4 2133.39   931.8  2132.6
   942.32134.081   956.9 2142.77   973.7 2161.44   977.9 2165.01   982.2 2166.38
#Mann= 3 ,-1,0
       0      .1       0   841.8     .04       0   942.3      .1       0
Bank Sta=841.8,942.3
XS Rating Curve= 0 ,0
Exp/Cntr(USF)=0,0
Exp/Cntr=0.3,0.1