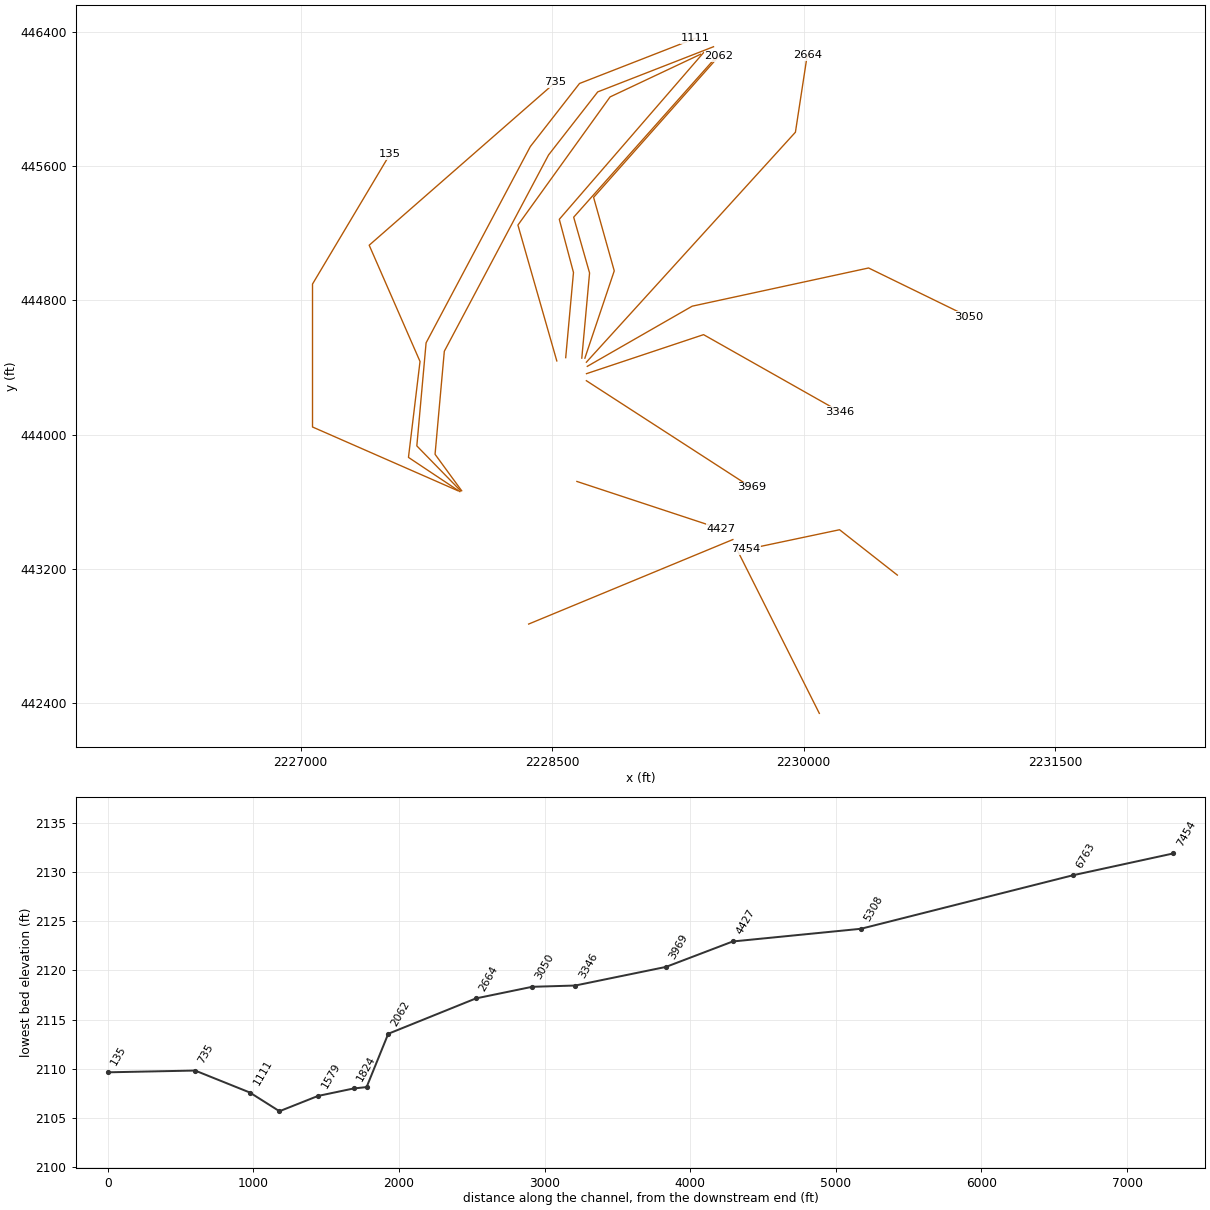
HEC-RAS study KNAPPCK.prj: KNAPPCK

--- KNAPPCK.g01 (geometry) --- (continued)

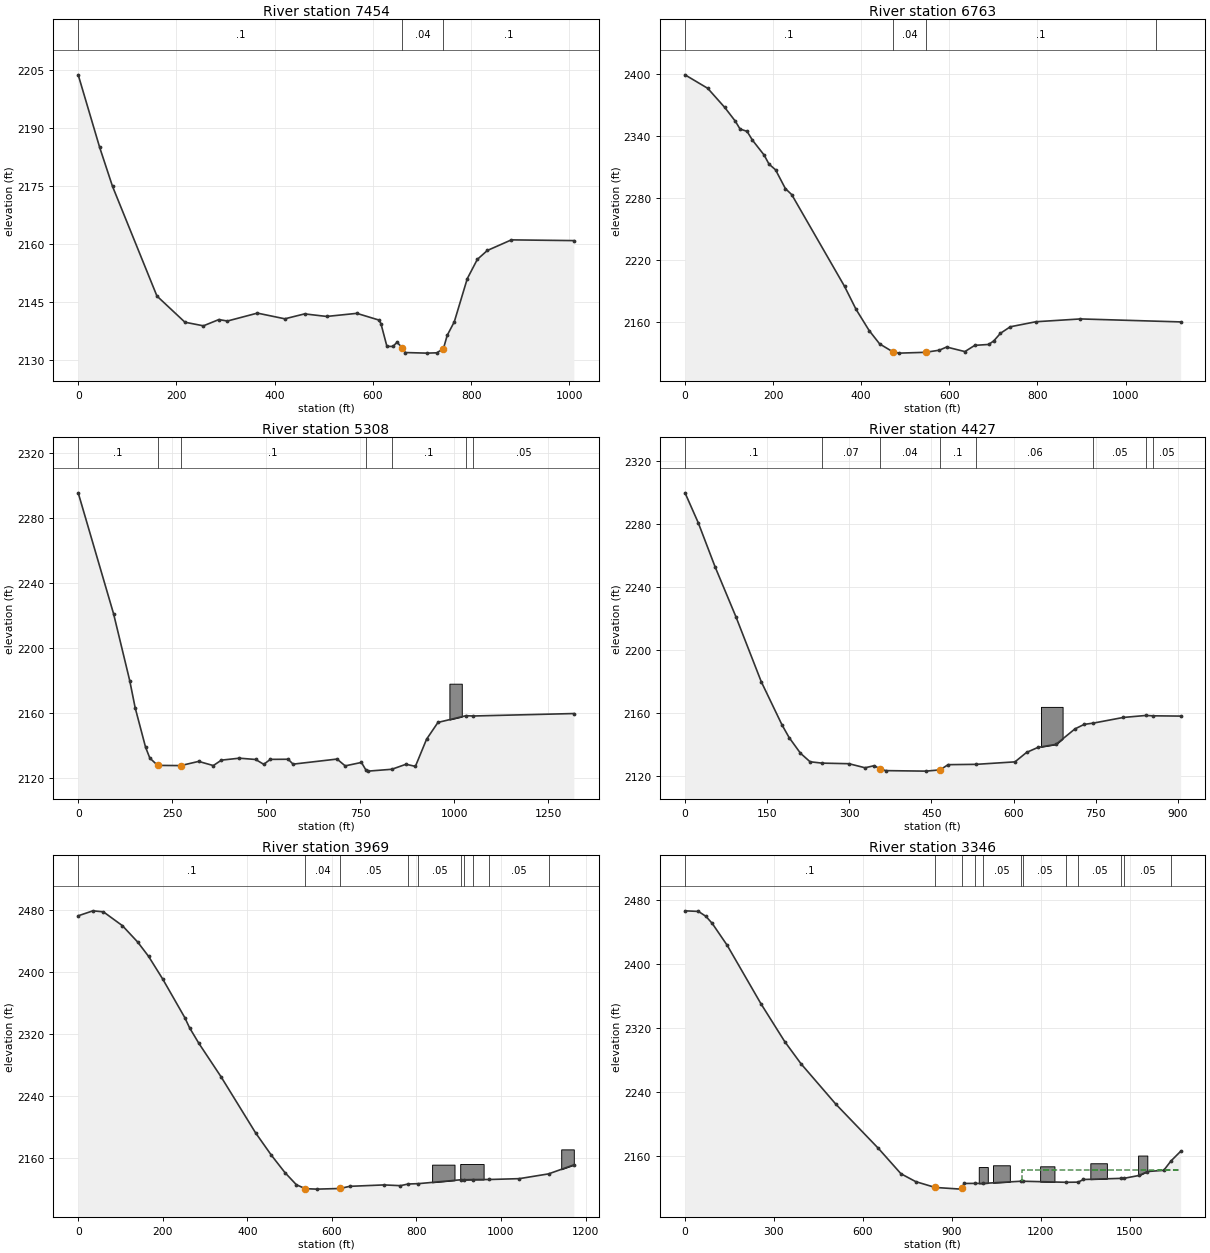
Type RM Length L Ch R = 1 ,7454    ,761.6,690.6,491.9
XS GIS Cut Line= 3
2230559.13363197443162.223979785 2230214.4131711443432.764088321
2229655.87875347443314.948234604
#Sta/Elev= 30
       0 2203.73    43.7    2185    69.9 2174.92   160.3 2146.62   217.3 2139.86
   254.9 2138.93   286.3 2140.54   303.8 2140.17   364.8 2142.21   420.7 2140.74
   460.9 2142.01   505.9 2141.35   567.2 2142.15   612.2 2140.42   616.3 2139.51
   628.5 2133.63   640.8  2133.6     649 2134.69   660.12133.228   665.9 2132.03
   709.8 2131.88   730.1 2131.96   743.6 2133.06   751.2 2136.46   765.7 2139.98
   792.1 2151.11   812.5 2156.07   832.9 2158.38   881.9 2161.12    1009 2160.93
#Mann= 3 ,0,0
       0      .1       0   660.1     .04       0   743.6      .1       0
Bank Sta=660.1,743.6
XS Rating Curve= 0 ,0
Exp/Cntr(USF)=0,0
Exp/Cntr=0.3,0.1

Type RM Length L Ch R = 1 ,6763    ,1510.7,1455.3,893.1
Node Name=B
XS GIS Cut Line= 2
2230093.77029989442337.5589642812229588.56089099 443342.71518406
#Sta/Elev= 30
       0 2399.01    51.6 2385.94    90.3 2367.39   114.1  2354.2   124.9 2346.58
   140.9 2344.27   152.9 2335.88   179.7 2321.29   190.6 2312.63   205.5 2307.08
   227.9 2288.85   242.2 2283.09   362.2 2194.22   388.2 2172.07     418 2151.51
   441.8 2138.59   472.6  2130.7   486.5 2129.66   545.92130.455   577.1 2132.48
   593.8 2135.57   635.3 2131.15   657.7 2137.18   689.4 2138.06   701.1 2141.61
   716.1 2148.89   738.3 2155.15   796.4 2160.03   897.7 2162.76    1125 2159.87
#Mann= 4 ,-1,0
       0      .1       0   472.6     .04       0   545.9      .1       0
    1070     .05       0
Bank Sta=472.6,545.9
XS Rating Curve= 0 ,0
Exp/Cntr(USF)=0,0
Exp/Cntr=0.3,0.1

Type RM Length L Ch R = 1 ,5308    ,819.6,880.5,363.5
XS GIS Cut Line= 2
2228360.18239141442870.2437895342229578.03569497443374.290772116
#Sta/Elev= 30
       0 2295.65    94.1 2221.13     137 2180.01   151.5 2163.26   179.2 2138.92
   190.5 2132.26   211.32127.763   272.7 2127.64   320.3 2130.22   359.3 2127.66
   380.9    2131   428.6  2132.2   471.9  2131.4   493.5 2128.41   510.8 2131.47
   558.4 2131.55   571.4 2128.53   688.3 2131.66     710 2127.47   753.2 2129.58
   764.6 2125.12   770.6 2124.23     834 2125.37   871.8 2128.47   896.7 2127.15
   926.4 2143.88   956.7 2154.23    1031 2158.35  1050.8 2158.19    1318  2159.7
#Mann= 7 ,-1,0
       0      .1       0   211.3     .04       0   272.7      .1       0
   764.6    .045       0     834      .1       0    1031    .016       0
  1050.8     .05       0
#Block Obstruct= 1 ,-1
  987.14 1020.05 2178.09
Bank Sta=211.3,272.7
XS Rating Curve= 0 ,0
Exp/Cntr(USF)=0,0
Exp/Cntr=0.3,0.1

Type RM Length L Ch R = 1 ,4427    ,471,458.1,388.9
XS GIS Cut Line= 2
2228647.89867167443720.7583974082229507.51804879443437.127638459
#Sta/Elev= 30
       0 2299.56    24.2 2280.55      55 2252.54      93  2220.9   139.3 2179.66
   177.2 2152.24   190.1 2144.28   210.9 2134.28   228.4 2128.89   250.1 2128.02
   299.4 2127.65   328.8 2125.07   345.7  2126.4   356.1 2124.33   366.7 2123.26
   440.1 2122.94   465.82123.733   480.5 2127.04     532 2127.25   602.6 2128.82
   623.8 2134.81   644.7 2138.01   677.6 2139.92   712.1 2149.72     729  2152.6
   745.8 2153.42   800.6 2157.01   841.2 2158.25     855 2158.04   905.2 2157.87
#Mann= 8 ,-1,0
       0      .1       0   250.1     .07       0   356.1     .04       0
   465.8      .1       0     532     .06       0   745.8     .05       0
   841.2    .016       0     855     .05       0
#Block Obstruct= 1 ,-1
   650.1   689.6 2163.71
Bank Sta=356.1,465.8
XS Rating Curve= 0 ,0
Exp/Cntr(USF)=0,0
Exp/Cntr=0.3,0.1

Type RM Length L Ch R = 1 ,3969    ,619.7,623,632.8
Node Name=A
XS GIS Cut Line= 2
2228704.44442543444321.5584137932229688.55025317443684.784054666
#Sta/Elev= 30
       0 2472.63    34.8 2479.04    59.6 2477.74   104.5 2459.94   140.6 2438.87
   166.4 2420.41   199.7  2391.3   252.2  2341.3   263.3 2328.42   285.5 2308.17
   337.9 2265.12   419.5 2192.95   457.1  2163.9   488.9 2141.74   516.1 2125.98
   537.22120.961   564.1 2120.36   619.1 2121.17   642.2 2123.97   723.2 2125.78
     762 2124.83   780.8 2126.98   804.2  2127.4   904.9 2132.41   911.3 2132.43
   934.4 2132.68   972.6 2132.77  1043.1 2133.86  1112.5 2140.01  1172.2  2151.6
#Mann= 10 ,-1,0
       0      .1       0   537.2     .04       0   619.1     .05       0
   780.8    .016       0   804.2     .05       0   904.9    .016       0
   911.3     .05       0   934.4    .016       0   972.6     .05       0
  1112.5      .1       0
#Block Obstruct= 3 ,-1
  837.04  890.02 2151.91  903.52  958.84 2152.69 1142.38 1172.15 2171.59
Bank Sta=537.2,619.1
XS Rating Curve= 0 ,0
Exp/Cntr(USF)=0,0
Exp/Cntr=0.3,0.1

Type RM Length L Ch R = 1 ,3346    ,228.7,296.1,482.6
XS GIS Cut Line= 3
2228705.10966236444363.6547843592229403.27768439444596.377458369
2230217.80704342444135.780499391
#Sta/Elev= 30
       0  2466.4    45.4 2465.66    70.7 2459.44    91.8 2450.67   142.4 2423.22
   256.2 2350.19   336.3 2302.95   391.1 2275.27   509.2 2224.51   652.6 2169.29
   728.4 2137.68   778.3 2127.82   843.72120.573     930 2118.47   934.6 2120.33
   941.5 2125.56   978.1 2125.64  1003.5 2125.59  1131.7  2128.3  1141.1 2128.32
  1283.8 2127.03    1326 2127.19  1343.8 2130.51  1469.8 2131.91  1481.4 2132.05
  1531.5 2135.54  1559.5 2140.47  1614.7 2141.94  1639.3 2153.75  1671.7 2165.72
#Mann= 12 ,-1,0
       0      .1       0   843.7     .04       0   934.6     .05       0
   978.1    .016       0  1003.5     .05       0  1131.7    .016       0
  1141.1     .05       0  1283.8    .016       0    1326     .05       0
  1469.8    .016       0  1481.4     .05       0  1639.3      .1       0
#XS Ineff= 2 , 0
                         1137.06          2142.2
Permanent Ineff=
       F       F
#Block Obstruct= 5 ,-1
  990.77 1021.25 2146.06 1038.85 1095.66 2148.28 1197.82 1246.06 2146.99
 1367.14 1422.92  2150.8 1528.21 1559.29 2160.44
Bank Sta=843.7,934.6
XS Rating Curve= 0 ,0
Exp/Cntr(USF)=0,0
Exp/Cntr=0.3,0.1

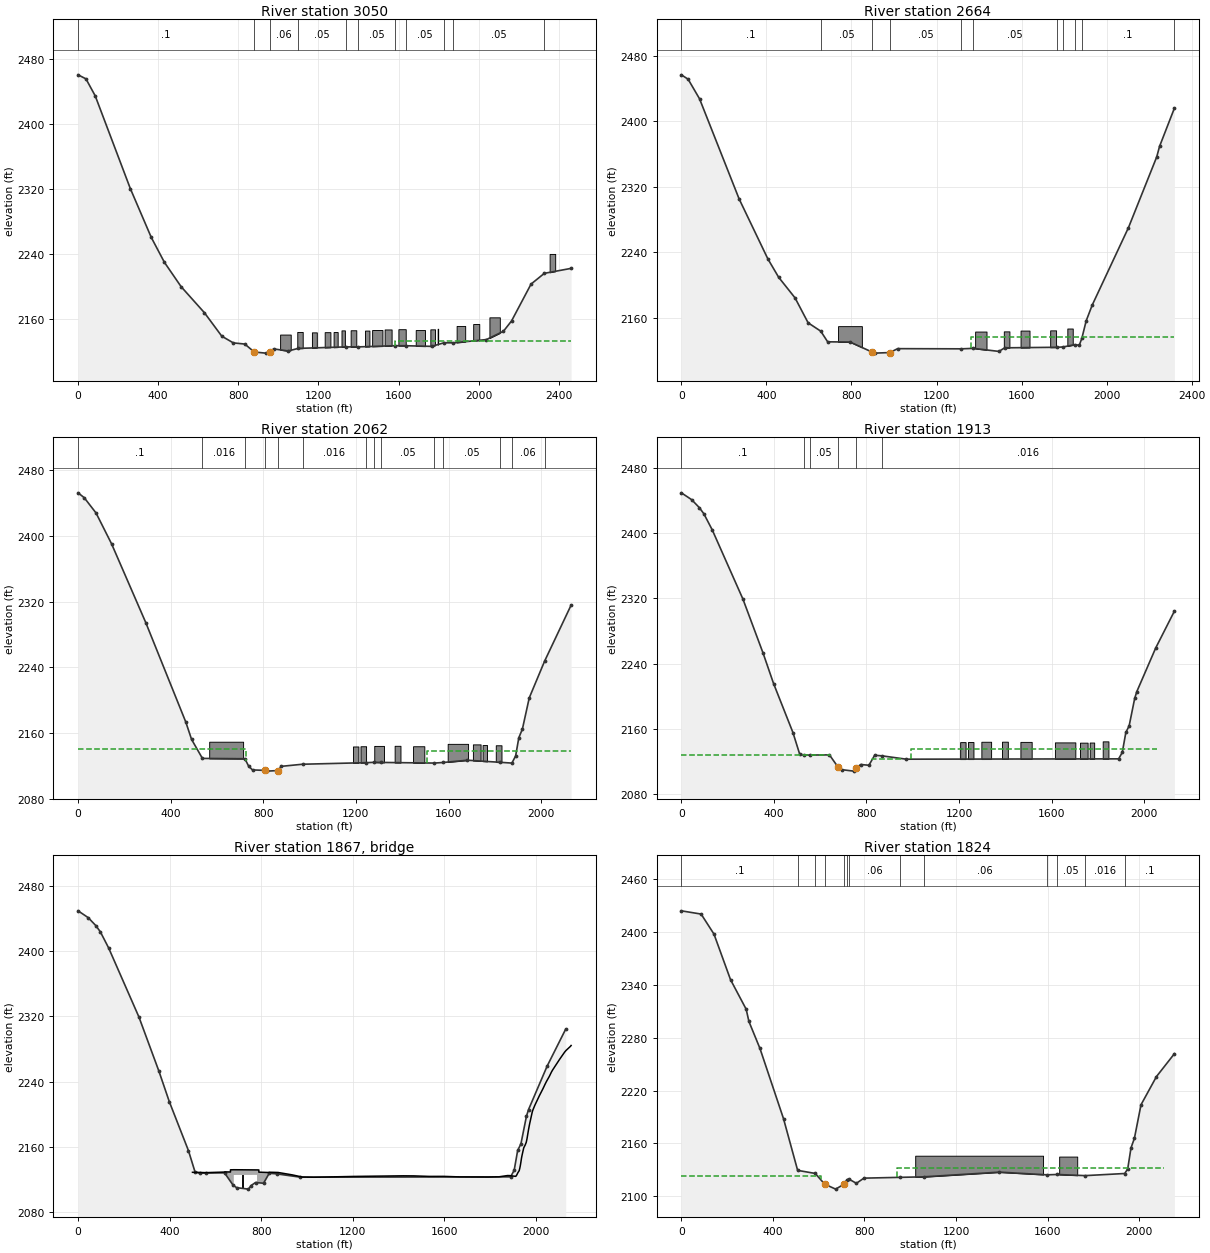
Type RM Length L Ch R = 1 ,3050    ,349.6,386.5,599.6
XS GIS Cut Line= 4
2228709.95805141444407.2902857362229335.40023781444766.071074834
2230387.50065989444993.9453598022230983.85251204 444703.04201729
#Sta/Elev= 30
       0  2460.7    39.4 2455.73    85.6 2434.83   260.8 2320.79   365.5 2260.64
   430.8 2230.12   514.4 2200.09   630.8 2168.02   717.3 2139.21     775 2130.93
   832.3  2129.5   879.42119.719   936.2 2118.34   959.2 2119.51   975.6 2123.54
  1049.3 2120.98  1098.4 2124.16  1339.8 2126.03  1397.1    2126  1581.3 2127.49
  1637.5 2127.43  1765.5 2126.66  1826.7 2131.08  1873.9 2130.95  2038.6 2135.02
  2123.2 2145.22  2163.6 2157.88  2261.1 2203.26  2327.4  2216.5  2461.1  2222.6
#Mann= 11 ,-1,0
       0      .1       0   879.4     .04       0   959.2     .06       0
  1098.4     .05       0  1339.8    .016       0  1397.1     .05       0
  1581.3      .1       0  1637.5     .05       0  1826.7    .016       0
  1873.9     .05       0  2327.4      .1       0
#XS Ineff= 2 , 0
                         1581.43         2133.85
Permanent Ineff=
       F       F
#Block Obstruct= 18 ,-1
 1008.53  1061.5 2141.18 1094.16 1121.31 2144.39 1167.32 1191.71 2143.88
 1230.99  1259.6 2144.12 1275.51 1295.79 2144.26 1314.92 1331.87 2146.32
 1360.62 1388.73 2146.47 1432.23 1454.33 2146.09 1467.79 1519.19 2146.77
 1530.28 1565.06 2147.46 1598.93  1635.5 2147.78 1685.46 1731.89 2146.71
 1758.47  1781.8  2147.6 1794.89 1797.54 2148.31 1889.61 1932.34 2151.78
 1972.25 2002.52 2154.14  2053.3 2105.18 2162.37 2353.79 2381.62 2240.37
Bank Sta=879.4,959.2
XS Rating Curve= 0 ,0
Exp/Cntr(USF)=0,0
Exp/Cntr=0.3,0.1

Type RM Length L Ch R = 1 ,2664    ,517.1,601.7,821.2
XS GIS Cut Line= 3
2228704.44442543444432.0729719892229951.14564612445803.626329794
 2230021.6550571446263.404255155
#Sta/Elev= 30
       0 2456.61    31.7 2451.28    85.5 2427.38   271.8 2305.14   406.9 2232.04
   457.5  2209.7   534.8 2184.47   596.1 2154.13   655.6 2143.93     688 2130.95
   793.5 2130.69   898.2 2118.31   909.5 2117.16   980.3 2117.85  1017.2 2122.62
  1317.3  2122.4  1373.3 2122.97  1493.4 2119.25  1520.4 2123.62  1767.5  2124.3
  1796.1 2124.71  1849.1 2127.46  1871.2 2126.78  1883.4 2135.24  1903.6 2156.47
  1931.9 2175.65  2102.7 2270.32  2235.5 2356.54  2248.7 2369.28  2318.6 2415.96
#Mann= 11 ,-1,0
       0      .1       0   655.6     .05       0   898.2     .04       0
   980.3     .05       0  1317.3    .016       0  1373.3     .05       0
  1767.5    .016       0  1796.1     .05       0  1849.1    .016       0
  1883.4      .1       0  2318.6      .1       0
#XS Ineff= 2 , 0
                         1364.03         2136.52
Permanent Ineff=
       F       F
#Block Obstruct= 6 ,-1
  736.87  848.85 2150.07  1381.5 1434.99 2143.47 1516.34 1542.76 2143.68
 1595.15 1637.22 2144.67 1734.38 1762.11 2144.92 1815.08 1840.52 2147.19
Bank Sta=898.2,980.3
XS Rating Curve= 0 ,0
Exp/Cntr(USF)=0,0
Exp/Cntr=0.3,0.1

Type RM Length L Ch R = 1 ,2062    ,146.1,148.5,164.1
BEGIN DESCRIPTION:
structure xs 4
END DESCRIPTION:
XS GIS Cut Line= 4
2228695.44336084444456.0893317222228870.65438585444976.826804595
 2228747.4913418445415.1120304032229494.06706536446256.382098416
#Sta/Elev= 30
       0 2452.29    26.5 2446.39    77.6 2427.77   144.6 2390.25   292.4 2294.34
   465.4 2173.22   490.3 2152.13   537.1 2129.04   720.4 2128.66   736.8 2119.58
   753.4 2115.03   807.72114.466   817.7 2113.57   863.1  2114.3     878  2119.4
   969.4 2121.96  1242.8 2123.86  1280.2 2124.27    1307 2124.16  1539.3 2123.38
  1578.2 2124.12  1681.3 2126.85  1822.7 2124.32  1873.7 2123.35  1889.9 2132.11
  1903.6 2154.22    1919 2164.68  1948.7 2202.77  2015.3 2247.64  2129.5 2315.63
#Mann= 14 ,-1,0
       0      .1       0   537.1    .016       0   720.4      .1       0
   807.7     .04       0   863.1     .06       0   969.4    .016       0
  1242.8     .05       0  1280.2    .016       0    1307     .05       0
  1539.3    .016       0  1578.2     .05       0  1822.7    .016       0
  1873.7     .06       0  2015.3      .1       0
#XS Ineff= 2 , 0
          725.22 2139.93 1506.02         2137.94
Permanent Ineff=
       F       F
#Block Obstruct= 10 ,-1
  566.34  712.81 2149.37 1187.22 1210.78 2143.58 1219.85 1243.88 2143.85
 1279.23 1321.23 2144.25 1367.28 1392.46 2144.39 1446.81 1495.47 2143.85
 1596.37 1684.44 2146.76 1705.33 1738.47 2146.13 1747.15 1766.39  2145.3
  1804.1 1828.78 2145.04
Bank Sta=807.7,863.1
XS Rating Curve= 0 ,0
Exp/Cntr(USF)=0,0
Exp/Cntr=0.5,0.3

Type RM Length L Ch R = 1 ,1913    ,90.9,89.4,92.9
BEGIN DESCRIPTION:
Structure XS 3 - channel burned within banks
END DESCRIPTION:
XS GIS Cut Line= 4
2228677.09678156444456.2340684992228723.47617053444964.088377768
2228628.65608641445296.7316620222229476.13794954446249.428536252
#Sta/Elev= 30
       0 2449.56    44.2 2441.23    77.3 2431.53    97.3 2423.85   133.5 2404.08
     266 2319.29   353.4 2252.79   398.6 2215.56   482.2 2155.53   511.1  2129.3
   531.9 2127.76   556.9 2127.89     640 2128.11   677.5 2112.98  692.86 2109.97
  744.77 2108.16   756.3 2112.59   775.7 2116.29   810.6 2115.35   835.5 2127.62
   867.2 2126.91     972 2122.81    1890 2123.21  1905.8  2131.2  1921.1 2155.61
  1935.3 2163.62  1959.3 2197.32  1968.5 2205.71  2050.3 2259.31    2131 2304.43
#Mann= 6 ,-1,0
       0      .1       0   531.9    .016       0   556.9     .05       0
   677.5     .04       0   756.3     .06       0   867.2    .016       0
#XS Ineff= 3 ,-1
       0     642 2128.41     824     950 2122.75  994.45 2057.322135.051
Permanent Ineff=
       F       F       F
#Block Obstruct= 9 ,-1
 1205.03 1228.43 2143.74 1238.74 1262.46 2143.86 1296.67  1338.8 2144.19
 1385.86 1411.03 2144.28 1465.42 1514.08 2144.02  1614.6  1702.8  2143.4
 1722.78  1755.8 2143.09 1764.92 1784.19 2143.23 1821.08 1845.88 2144.67
Bank Sta=677.5,756.3
XS Rating Curve= 0 ,0
Exp/Cntr(USF)=0,0
Exp/Cntr=0.5,0.3

Type RM Length L Ch R = 3 ,1867    ,,,
BEGIN DESCRIPTION:
Route 39/2 5th Ave
Bridge data: 54075KNA020
Width: 12.2' (measured on orthoimagery)
Railing height: 2.7'
Circular Pier width: 3.5', two identical piers on either side of the deck at the same stationing
Structure bounding sections incorporate channel data from survey.
Deck from Lidar with survey data incorporated.
END DESCRIPTION:
Bridge Culvert--1,0,-1,-1, 0
Deck Dist Width WeirC Skew NumUp NumDn MinLoCord MaxHiCord MaxSubmerge Is_Ogee
46,12.2,2.6,0, 60, 42, , , 0.98, 0, 0,0,,
     500  559.31  639.08     640     666     666  680.61   782.2     790     790
  829.48  844.16  873.94  936.44 978.8231029.9921205.1181419.9321467.2941534.814
1597.8281668.7441791.213 1839.631876.648  1885.21912.3221913.6811916.5291922.225
1927.6051928.3221930.769  1932.71934.7811937.7941939.3141942.8881947.6991954.159
1958.172 1959.251962.0981968.4621973.161 1984.811987.648 1996.162015.7322031.489
2041.9932047.2272059.5712068.2542073.507 2105.022126.0292132.3642152.1532154.696
  2128.8  2128.4 2129.09 2129.37 2129.17 2131.87 2131.96 2131.74 2131.68 2128.98
 2128.59 2128.83 2128.61 2125.632123.0492122.7262123.7432124.4912124.4062123.774
2123.8192123.1652122.9412123.2852124.8122124.7662123.8172124.0852125.2512128.408
2130.7372131.4072134.2732137.0532140.4512146.0572148.3112153.0012158.8592162.425
2165.2422166.404 2170.252181.0172187.9492202.8032205.2532211.0242222.6182231.285
 2237.49 2240.372246.5142251.5342254.171 2267.692276.1192278.2462283.4232284.387
                                                 2125.52 2125.65
                                                                                
                                                                                
                                                                                
                                                                                
                                                                                
     490  491.12  495.03  498.39  507.49  515.68  532.05  565.63  579.08     580
     606     606  620.61   722.2     730     730   768.1  769.48  784.16  790.88
  795.01  800.01  801.29  809.29  814.22  835.12  855.78  881.96 930.494 942.058
 957.198 978.823 998.5181029.9921055.3331095.3761153.4681205.118  1307.71344.529
1367.198 1416.29
 2130.75  2129.8 2128.53 2128.41 2128.64 2128.47 2128.59 2129.14 2129.09 2129.37
 2129.17 2131.87 2131.96 2131.74 2131.68 2128.98 2128.69 2128.59 2128.83  2128.8
 2128.69  2128.7 2128.77 2128.73  2128.6  2127.7  2126.7 2125.292124.8462124.308
 2123.722123.0492122.8172122.7262122.8212123.1372123.3342123.7432124.023 2124.21
2124.1882124.462
                                                                                
                 2125.52 2125.65
                                                                                
                                                                                
                
Pier Skew, UpSta & Num, DnSta & Num=  ,717.74, 2 ,660.94, 2 , 0 , 0 , 0 ,,
     3.5     3.5
 2112.85 2125.65
     3.5     3.5
 2108.72 2125.65
Pier Skew, UpSta & Num, DnSta & Num=  ,717.74, 2 ,660.94, 2 , 0 , 0 , 0 ,,
     3.5     3.5
 2112.85 2125.65
     3.5     3.5
 2108.72 2125.65
BR Coef=-1 ,-1 , 0 ,0.95, 0 ,,,0.8,-1,1.2,0,
WSPro=,,,, 1 ,,,, 0 ,,,, 0 ,,,,-1 ,-1 ,-1 , 0 , 0 , 0 , 0 , 0
BR U #Sta/Elev= 30
       0 2449.56    44.2 2441.23    77.3 2431.53    97.3 2423.85   133.5 2404.08
     266 2319.29   353.4 2252.79   398.6 2215.56   482.2 2155.53   511.1  2129.3
   531.9 2127.76   556.9 2127.89     640 2128.11   677.5 2112.98  692.86 2109.97
  744.77 2108.16   756.3 2112.59   775.7 2116.29   810.6 2115.35   835.5 2127.62
   867.2 2126.91     972 2122.81    1890 2123.21  1905.8  2131.2  1921.1 2155.61
  1935.3 2163.62  1959.3 2197.32  1968.5 2205.71  2050.3 2259.31    2131 2304.43
BR U #Mann= 6
       0      .1   531.9    .016   556.9     .05   677.5    .035   756.3     .06
   867.2    .016
BR D #Sta/Elev= 30
       0 2424.26   86.39 2420.57  142.63 2397.78  214.93    2346  283.21 2312.46
  295.26 2298.51  343.46 2267.87  446.36 2188.09  508.14 2129.33  584.95 2125.85
   626.12113.735  674.07 2108.02   710.62113.564  723.64 2118.62  731.62 2119.52
  764.74 2114.63  797.85  2120.5  955.91 2121.41 1058.14 2121.97  1390.2 2127.32
 1598.03 2124.26 1642.31 2124.66 1764.25 2123.36 1937.23 2125.76  1950.4  2130.9
 1964.79 2154.82 1979.77 2165.82 2008.59 2203.89 2076.18 2235.94 2154.53 2261.92
BR D #Mann= 13
       0      .1  508.14    .016  584.95     .08   626.1    .035   710.6     .06
  723.64    .016  731.62     .06  955.91    .016 1058.14     .06 1598.03    .016
 1642.31     .05 1764.25    .016 1937.23      .1
BC Design=,, 0 ,, 0 ,,,,,,
BC Use User HTab Curves=0
BC User HTab FreeFlow(D)= 0

Type RM Length L Ch R = 1 ,1824    ,245.2,244.7,244.7
BEGIN DESCRIPTION:
Structure XS 2 - channel burned within banks
END DESCRIPTION:
XS GIS Cut Line= 4
2228581.10130757444459.1431186512228627.48069654 444966.99742792
 2228542.9671433 445284.180915852229404.33546186446279.534135894
#Sta/Elev= 30
       0 2424.26   86.39 2420.57  142.63 2397.78  214.93    2346  283.21 2312.46
  295.26 2298.51  343.46 2267.87  446.36 2188.09  508.14 2129.33  584.95 2125.85
   626.12113.735  674.07 2108.02   710.62113.564  723.64 2118.62  731.62 2119.52
  764.74 2114.63  797.85  2120.5  955.91 2121.41 1058.14 2121.97  1390.2 2127.32
 1598.03 2124.26 1642.31 2124.66 1764.25 2123.36 1937.23 2125.76  1950.4  2130.9
 1964.79 2154.82 1979.77 2165.82 2008.59 2203.89 2076.18 2235.94 2154.53 2261.92
#Mann= 13 ,-1,0
       0      .1       0  508.14    .016       0  584.95     .08       0
   626.1     .04       0   710.6     .06       0  723.64    .016       0
  731.62     .06       0  955.91    .016       0 1058.14     .06       0
 1598.03    .016       0 1642.31     .05       0 1764.25    .016       0
 1937.23      .1       0
#XS Ineff= 3 ,-1
       0     610  2122.8  731.74  929.742119.418  941.49 2107.292132.364
Permanent Ineff=
       F       F       F
#Block Obstruct= 2 ,-1
 1021.86 1580.56    2146 1650.96 1729.82 2145.01
Bank Sta=626.1,710.6
XS Rating Curve= 0 ,0
Exp/Cntr(USF)=0,0
Exp/Cntr=0.5,0.3

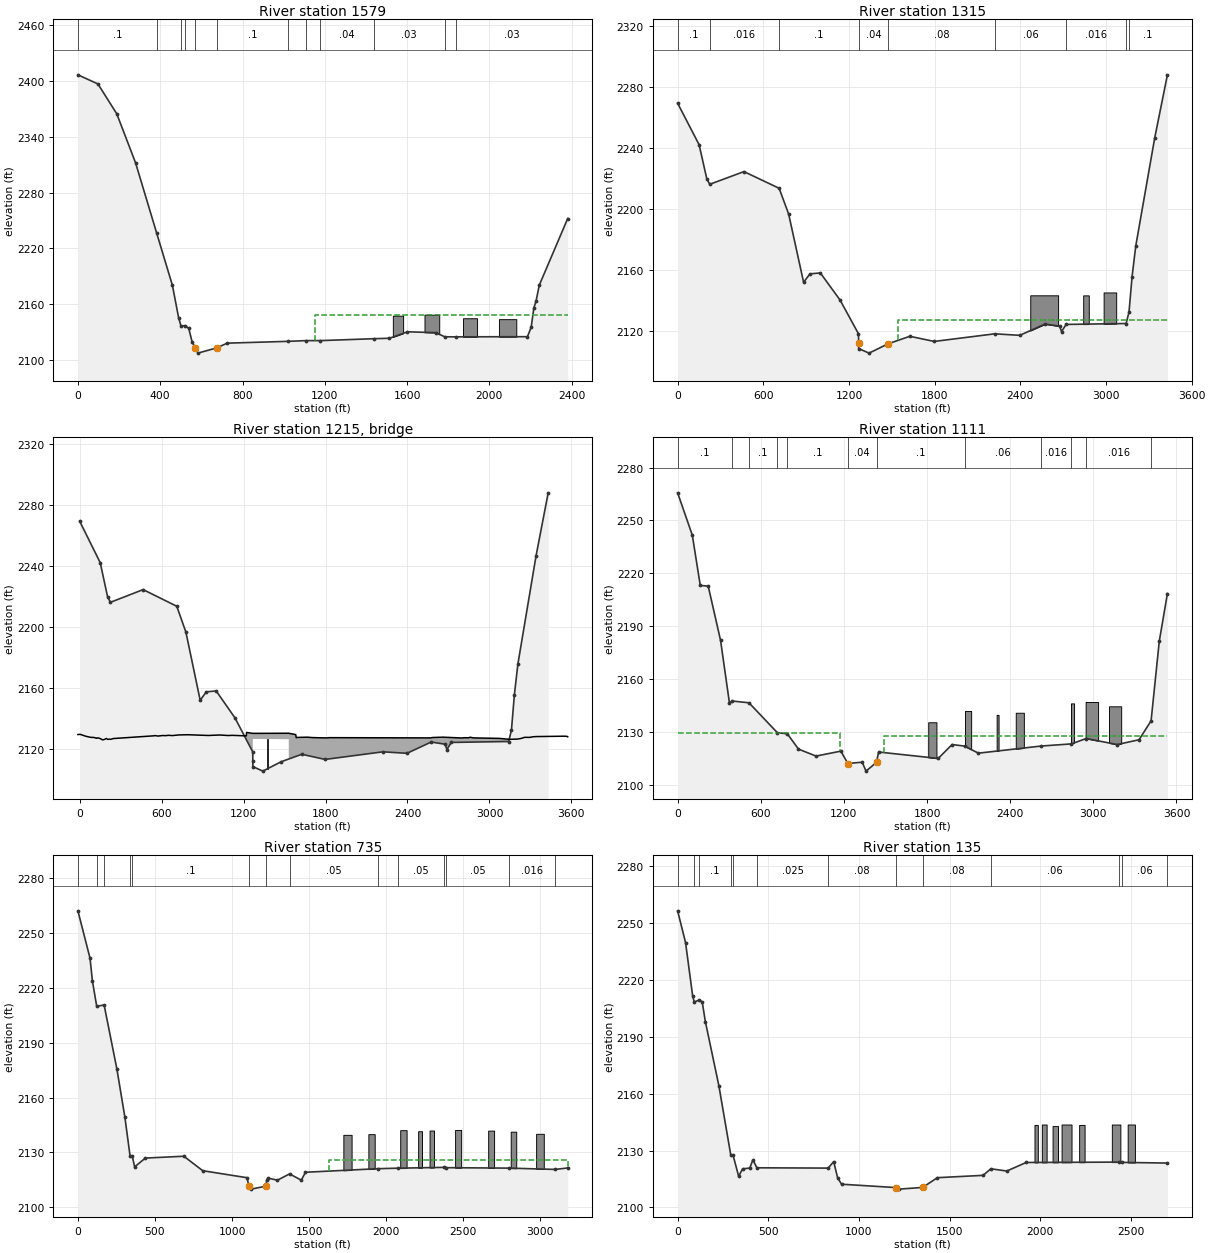
Type RM Length L Ch R = 1 ,1579    ,369.9,264.3,211.1
BEGIN DESCRIPTION:
structure xs 4
Invert burned , interpolated between structures
END DESCRIPTION:
XS GIS Cut Line= 4
2228527.99080952444439.5436688512228296.09386464 445249.75151328
2228845.77551175446014.1525537832229385.17152732446268.408372236
#Sta/Elev= 30
       0 2406.73    97.4  2396.9   188.9 2364.78   280.5 2311.86   382.9 2236.38
   459.4 2180.15   489.6 2145.18     501 2136.56     522 2136.76   538.9 2133.79
   555.1 2119.28   569.9 2113.08  583.46 2107.26   675.7    2113   725.6    2118
  1022.9 2119.95  1108.1 2120.72  1177.7 2120.72  1438.2 2122.78  1514.3 2123.26
  1601.9 2130.22  1739.4 2129.28  1783.1 2124.83  1836.4 2124.79  2184.9 2124.95
  2203.1  2135.1  2215.9 2155.66  2227.1 2163.55  2242.4 2180.36  2380.6 2252.12
#Mann= 12 ,-1,0
       0      .1       0   382.9     .05       0     501    .016       0
     522     .05       0   569.9     .04       0   675.7      .1       0
  1022.9     .05       0  1108.1      .1       0  1177.7     .04       0
  1438.2     .03       0  1783.1    .016       0  1836.4     .03       0
#XS Ineff= 2 , 0
                         1153.18         2148.66
Permanent Ineff=
       F       F
#Block Obstruct= 4 ,-1
 1530.66  1580.7 2147.54 1684.47 1756.24 2148.63 1871.73  1940.1 2144.79
 2046.32 2130.73  2143.8
Bank Sta=569.9,675.7
XS Rating Curve= 0 ,0
Exp/Cntr(USF)=0,0
Exp/Cntr=0.7,0.5

Type RM Length L Ch R = 1 ,1315    ,406.7,203.5,179.2
BEGIN DESCRIPTION:
Structure XS 3 - channel burned within banks
END DESCRIPTION:
XS GIS Cut Line= 6
2227960.78512195443665.2145577092227801.95675647443882.740362605
2227857.20140534444497.3370812022228478.70370504445667.833078978
2228772.19090212446044.187249355 2229462.7490129 446313.50491256
#Sta/Elev= 30
       0 2269.64   150.3 2242.47   204.5    2220   224.9 2216.45   464.6 2224.79
   710.9 2213.85   777.8 2196.86   882.2  2152.2     927  2157.7   999.5 2158.32
    1137 2140.62  1266.7 2118.39 1267.86 2112.51 1268.02 2108.68 1340.99 2105.71
  1474.2 2111.84  1626.3 2116.75  1796.9 2113.38  2220.6 2118.37  2396.2 2117.39
  2573.5 2124.79    2675 2123.36  2688.9 2119.85  2720.6 2124.53  3140.7 2125.14
  3161.2 2132.61  3182.7 2155.89  3208.4 2175.96  3341.4 2246.96  3430.2 2288.27
#Mann= 9 ,-1,0
       0      .1       0   224.9    .016       0   710.9      .1       0
 1267.86     .04       0  1474.2     .08       0  2220.6     .06       0
  2720.6    .016       0  3140.7     .05       0  3161.2      .1       0
#XS Ineff= 2 , 0
            1167    2129    1545          2127.5
Permanent Ineff=
       F       F
#Block Obstruct= 3 ,-1
 2469.59 2664.61 2143.64 2840.39 2879.44  2143.6 2983.36 3071.42 2145.51
Bank Sta=1267.86,1474.2
XS Rating Curve= 0 ,0
Exp/Cntr(USF)=0,0
Exp/Cntr=0.5,0.3

Type RM Length L Ch R = 3 ,1215    ,,,
BEGIN DESCRIPTION:
Greenbrier River Trail
Bridge data: 54075KNA010
Width: 17' (measured on orthoimagery)
A wooden railing exists within the truss bridge but hasn't been modeled since a railing height was not provided.
Rectangular Pier width: 10'
Structure bounding sections incorporate channel data from survey.
Deck from Lidar with survey data incorporated.
END DESCRIPTION:
Bridge Culvert--1,0,-1,-1, 0
Deck Dist Width WeirC Skew NumUp NumDn MinLoCord MaxHiCord MaxSubmerge Is_Ogee
100,17,2.6,0, 60, 60, , , 0.98, 0, 0,0,,
     -13    2.82   45.77   79.61   104.8  123.91  127.51  135.73  151.01  165.26
  171.17  177.47  195.63  204.71  218.59  227.42  245.59  546.27  549.86  572.85
  607.18  628.97  649.42  679.18  725.45  793.03  941.86 1026.78 1085.35 1119.83
 1220.06    1222 1267.63 1530.76 1581.71 1585.49 1594.31  1667.7 1702.64 1805.51
 1827.832567.5232584.4612658.6462796.3842820.5042844.9142859.1842881.913 3074.16
3149.4383206.2323230.5913258.592 3294.113319.6063342.5413547.4473567.5883573.065
 2129.69 2129.85 2128.57 2127.88 2127.79 2127.26  2127.5 2127.47 2127.03 2126.31
 2126.29 2126.37 2127.12 2126.51 2126.71 2126.56 2127.08 2128.89 2129.06 2128.71
 2129.06 2128.98  2129.2 2129.03 2129.45 2129.58  2129.1 2129.41 2129.07 2129.18
 2128.83 2131.09 2130.48 2130.56 2129.67 2127.65 2127.83 2127.98 2127.72 2127.49
 2127.662127.5092127.7732127.9862127.4562127.6432127.5552127.9352127.5132127.173
2126.5682126.7442127.1182127.8912127.838 2128.252128.3722128.6252128.528 2128.24
                                                                                
                                                                                
                                                                                
                 2126.84 2126.64
                                                                                
                                                                                
     -80  -64.18  -21.24   12.61    37.8   56.91   60.51   68.73   84.01   98.26
  104.17  110.47  128.63  137.71  151.59  160.42  178.59  479.27  482.86  505.85
  540.18  561.97  582.42  612.18  658.45  726.03  874.86  959.78 1018.35 1052.83
 1153.06    1155 1200.63 1463.76 1514.71 1518.49 1527.31  1600.7 1635.64 1738.51
 1760.832525.5232542.4612616.6462754.3842778.5042802.9142817.1842839.913 3032.16
3107.4383164.2323188.5913216.592 3252.113277.6063300.5413505.4473525.5883531.065
 2129.69 2129.85 2128.57 2127.88 2127.79 2127.26  2127.5 2127.47 2127.03 2126.31
 2126.29 2126.37 2127.12 2126.51 2126.71 2126.56 2127.08 2128.89 2129.06 2128.71
 2129.06 2128.98  2129.2 2129.03 2129.45 2129.58  2129.1 2129.41 2129.07 2129.18
 2128.83 2131.09 2130.48 2130.56 2129.67 2127.65 2127.83 2127.98 2127.72 2127.49
 2127.662127.5092127.7732127.9862127.4562127.6432127.5552127.9352127.5132127.173
2126.5682126.7442127.1182127.8912127.838 2128.252128.3722128.6252128.528 2128.24
                                                                                
                                                                                
                                                                                
                 2126.84 2126.64
                                                                                
                                                                                
Pier Skew, UpSta & Num, DnSta & Num=  ,1377, 2 ,1350, 2 , 0 , 0 , 0 ,,
      10      10
 2109.58 2126.84
      10      10
 2109.58 2126.84
BR Coef=-1 ,-1 , 0 ,1.25, 0 ,,,0.8,0,2,0,
WSPro=,,,, 1 ,,,, 0 ,,,, 0 ,,,,-1 ,-1 ,-1 , 0 , 0 , 0 , 0 , 0
BC Design=,, 0 ,, 0 ,,,,,,
BC Use User HTab Curves=0
BC User HTab FreeFlow(D)= 0

Type RM Length L Ch R = 1 ,1111    ,96,375.8,452.2
BEGIN DESCRIPTION:
Structure XS 2 - channel burned within banks
There is only a single survey point within banks.
END DESCRIPTION:
XS GIS Cut Line= 6
2227954.28877219443665.1902806492227693.19385402443932.805825637
2227748.43850289444547.4025442332228369.94080259 445717.89854201
2228663.42799967446094.2527123862229353.98611046446363.570375591
#Sta/Elev= 30
       0 2265.63   106.1 2241.56   163.4 2213.02   220.7 2212.67   309.8  2181.9
   373.9 2146.34   394.3 2147.41   514.8 2146.42   719.6 2129.44   791.9  2128.8
   872.3 2120.11   998.9 2116.16    1178 2118.96  1228.5 2111.93  1332.3 2112.69
 1359.44 2107.61  1435.62112.598  1450.4 2118.46  1880.6 2114.81  1980.8 2122.71
  2070.8 2121.82  2170.5 2117.81  2624.7 2121.87  2841.5 2123.07  2948.8 2126.13
  3172.1  2122.7    3330 2125.43  3416.8 2136.16  3475.9 2181.36  3534.7 2208.44
#Mann= 12 ,-1,0
       0      .1       0   394.3    .016       0   514.8      .1       0
   719.6    .016       0   791.9      .1       0  1228.5     .04       0
  1435.6      .1       0  2070.8     .06       0  2624.7    .016       0
  2841.5     .05       0  2948.8    .016       0  3416.8      .1       0
#XS Ineff= 2 , 0
            1175    2129    1489          2127.5
Permanent Ineff=
       F       F
#Block Obstruct= 7 ,-1
 1808.52 1867.89 2135.36 2073.67 2118.35 2141.79 2302.29 2316.22 2139.54
 2440.06 2498.58 2140.76 2838.75 2861.07 2146.07 2944.52  3034.4 2146.84
 3113.21 3201.17 2144.41
Bank Sta=1228.5,1435.6
XS Rating Curve= 0 ,0
Exp/Cntr(USF)=0,0
Exp/Cntr=0.5,0.3

Type RM Length L Ch R = 1 ,735     ,686.7,600.5,500.1
BEGIN DESCRIPTION:
structure xs 1
END DESCRIPTION:
XS GIS Cut Line= 5
2227949.72126396443660.2502951382227643.31246219443864.270713047
2227712.25867408444436.3030472182227409.09699102445129.707055264
2228520.66890749446101.958479691
#Sta/Elev= 30
       0 2262.23    78.7 2236.26    94.1 2223.82     122 2209.96   170.1 2210.66
   252.8 2175.66   304.7 2149.29   338.2 2128.12   352.7 2127.88   368.1 2122.04
   437.5 2126.84   687.3 2127.85   809.9 2119.93  1096.9 2116.09  1109.82111.432
  1124.2 2109.84  1220.3 2111.47  1224.6 2114.76  1233.6 2115.87  1294.5 2114.73
  1373.1 2118.18  1449.3 2114.76  1476.6 2119.08  1944.3 2121.03  2077.2 2121.31
  2374.7 2121.75  2386.8 2121.59    2800 2121.34  3097.6 2120.63  3177.8 2121.45
#Mann= 14 ,-1,0
       0      .1       0     122    .016       0   170.1      .1       0
   338.2    .016       0   352.7      .1       0  1109.8     .04       0
  1220.3      .1       0  1373.1     .05       0  1944.3    .016       0
  2077.2     .05       0  2374.7    .016       0  2386.8     .05       0
    2800    .016       0  3097.6     .05       0
#XS Ineff= 2 , 0
                         1626.72         2125.97
Permanent Ineff=
       F       F
#Block Obstruct= 9 ,-1
 1722.24 1775.69 2139.57 1884.51 1925.59 2139.94 2091.17  2132.6 2142.13
 2207.48 2232.58 2141.54 2281.43 2310.38 2141.93 2447.21 2486.53 2142.25
 2661.83 2700.25 2141.88 2808.06 2843.86  2141.3 2972.92  3022.6 2140.14
Bank Sta=1109.8,1220.3
XS Rating Curve= 0 ,0
Exp/Cntr(USF)=0,0
Exp/Cntr=0.3,0.1

Type RM Length L Ch R = 1 ,135     ,,,
XS GIS Cut Line= 4
 2227936.3968784443666.2370545142227071.06788773444045.617745005
2227071.06788773444898.1586225152227533.78669047445674.145591278
#Sta/Elev= 30
       0 2256.42    43.9  2239.6    83.2 2211.34      92 2208.34   118.2 2209.41
   135.6 2208.41   153.1 2197.93   227.4 2164.23   292.9 2127.74     306 2127.44
   336.5 2116.45   358.4 2120.37   397.7 2120.76   415.2  2125.1     437 2120.91
   830.1 2120.75   860.6 2124.17   882.5 2115.55   904.3 2112.25  1204.4 2110.47
  1220.4 2109.66  1351.3 2110.55  1432.4  2115.7  1684.4 2116.92  1727.3 2120.39
  1815.2  2119.2    1922 2123.71  2433.5 2123.91  2447.8 2123.77  2700.9  2123.4
#Mann= 13 ,-1,0
       0      .1       0      92    .016       0   118.2      .1       0
   292.9    .016       0     306     .06       0     437    .025       0
   830.1     .08       0  1204.4     .04       0  1351.3     .08       0
  1727.3     .06       0  2433.5    .016       0  2447.8     .06       0
  2700.9     .03       0
#Block Obstruct= 7 ,-1
 1967.89 1986.17 2143.53 2008.27 2034.81 2143.74 2067.58 2097.79  2142.9
 2117.25 2172.14 2143.74 2214.14 2244.18 2143.52 2394.35  2441.5 2143.73
  2481.7 2521.68 2143.74
Bank Sta=1204.4,1351.3
XS Rating Curve= 0 ,0
Exp/Cntr(USF)=0,0
Exp/Cntr=0.3,0.1
LCMann Table=0

Chan Stop Cuts=-1
Use User Specified Reach Order=0
Composite Channel Slope=5